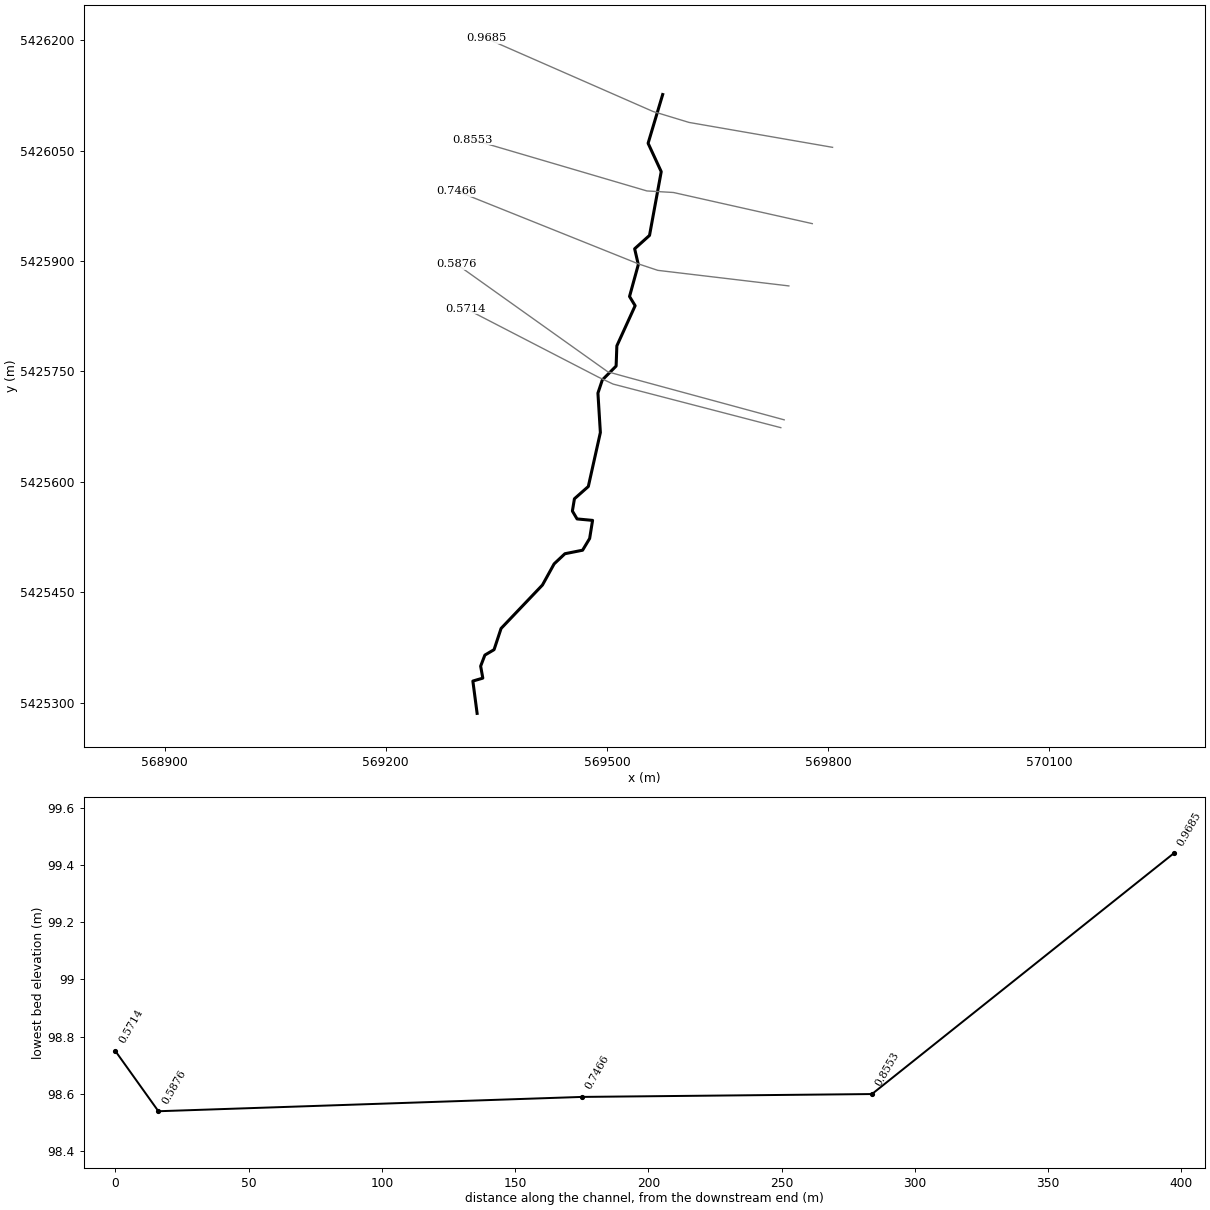
HEC-RAS study Exploits_FMM.prj: Exploits_FMM

--- Exploits_FMM.f01 (steady flow) ---

Flow Title=2021_02_09_SteadyFlows
Program Version=5.06
BEGIN FILE DESCRIPTION:
Flow Data to be used for tributary runs
END FILE DESCRIPTION:
Number of Profiles= 8
Profile Names=1:20 CC - Exploits,1:20 CLC - Exploits,1:100 CC - Exploits,1:100 CLC - Exploits,1:20 CC - Tribs,1:20 CLC - Tribs,1:100 CC - Tribs,1:100 CLC - Tribs
River Rch & RM=B1,B1              ,0.9685
     .01     .01     .01     .01     5.4     6.4       7     8.1
River Rch & RM=Badger Brk,Badger Brk      ,1.9217
     .01     .01     .01     .01     257281.0938     325344.2635
River Rch & RM=BF1,BF1             ,1.2199
     .01     .01     .01     .01     .01     .01     .01     .01
River Rch & RM=BF1,BF1             ,.3504
     .01     .01     .01     .01      .3      .3      .4      .4
River Rch & RM=BF2,BF2             ,1.2490
     .01     .01     .01     .013.0143543.5669863.8684214.471292
River Rch & RM=BF2,BF2             ,0.8133
     .01     .01     .01     .014.8229675.7071776.1894747.154067
River Rch & RM=BF3,BF3             ,2.1832
     .01     .01     .01     .01     7.6     8.5      10      11
River Rch & RM=BF3,BF3             ,0.8646
     .01     .01     .01     .01     7.6     8.6    10.2    11.2
River Rch & RM=BF4,BF4             ,0.9422
     .01     .01     .01     .011.0942281.2563361.3779171.580552
River Rch & RM=BF4,BF4             ,0.6155
     .01     .01     .01     .011.4014931.6091221.7648432.024379
River Rch & RM=Corduroy Brk,Corduroy Brk    ,3.8918
     .01     .01     .01     .01     4.6       5     5.6     6.3
River Rch & RM=Corduroy Brk,Corduroy Brk    ,3.2308
     .01     .01     .01     .01     3.6     3.6     3.6     3.6
River Rch & RM=Corduroy Brk,Corduroy Brk    ,2.5346
     .01     .01     .01     .01       4     4.3     4.9     5.6
River Rch & RM=Corduroy Brk,Corduroy Brk    ,1.7767
     .01     .01     .01     .01     6.1     6.7     7.2     8.1
River Rch & RM=Corduroy Brk,Corduroy Brk    ,1.3922
     .01     .01     .01     .01       7     7.4     7.8     8.2
River Rch & RM=Corduroy Brk,Corduroy Brk    ,0.7838
     .01     .01     .01     .01    10.2    10.9    11.5    12.3
River Rch & RM=Exploits River,Mill to LRI     ,127.9419
    13401468.405    16501747.339     .01     .01     .01     .01
River Rch & RM=Exploits River,Mill to LRI     ,98.9083
    13401468.405    16501747.339     .01     .01     .01     .01
River Rch & RM=Exploits River,LRI to Badger   ,75.6731
    14001535.016    1715 1816.68     .01     .01     .01     .01
River Rch & RM=Exploits River,Badger to Wigwam,75.2189
    14181553.786    17301832.852     .01     .01     .01     .01
River Rch & RM=Exploits River,Badger to Wigwam,54.2773
    14301563.804    1740 1839.12     .01     .01     .01     .01
River Rch & RM=Exploits River,Wigwam to RP    ,49.8124
    14301563.804    1740 1839.12     .01     .01     .01     .01
River Rch & RM=Exploits River,RP to CB        ,48.3493
    14301563.804    1740 1839.12     .01     .01     .01     .01
River Rch & RM=Exploits River,RP to CB        ,46.8155
    14981638.733    18181922.646     .01     .01     .01     .01
River Rch & RM=Exploits River,CB to BF4       ,43.6571
    14981638.733    18181922.646     .01     .01     .01     .01
River Rch & RM=Exploits River,CB to BF4       ,43.2587
    15001641.405    18201924.198     .01     .01     .01     .01
River Rch & RM=Exploits River,BF4 to BF3      ,28.6539
    15001641.405    18201924.198     .01     .01     .01     .01
River Rch & RM=Exploits River,BF3 to BF2      ,25.6408
    15001641.405    18201924.198     .01     .01     .01     .01
River Rch & RM=Exploits River,BF3 to BF2      ,23.7672
    22202435.927    28102975.312     .01     .01     .01     .01
River Rch & RM=Exploits River,BF2 to BF1      ,23.3904
    22202435.927    28102975.312     .01     .01     .01     .01
River Rch & RM=Exploits River,BF1 to Outlet   ,20.2457
    22202435.927    28102975.312     .01     .01     .01     .01
River Rch & RM=GF1,GF1             ,3.9291
     .01     .01     .01     .01       1     1.2     1.3     1.5
River Rch & RM=GF1,GF1             ,3.1868
     .01     .01     .01     .01     1.5   1.775   1.925    2.25
River Rch & RM=GF1,GF1             ,1.9833
     .01     .01     .01     .01       6     7.1     7.7       9
River Rch & RM=GF1,GF1             ,1.0726
     .01     .01     .01     .01    13.9    15.9    17.9      20
River Rch & RM=Little Red Ind,LRI to B1       ,1.4448
     .01     .01     .01     .01    77.5 85.4754     101107.5051
River Rch & RM=Little Red Ind,B1 to Expl      ,1.2620
     .01     .01     .01     .01    82.991.87539     108115.6051
River Rch & RM=Little Rushy Pd,Little Rushy Pd ,0.5608
     .01     .01     .01     .01     1.9     2.1     2.4     2.7
River Rch & RM=Mullens Pond,Mullens Pond    ,0.4097
     .01     .01     .01     .01     1.7       2     2.1     2.5
River Rch & RM=Rushy Pond,Rushy Pond      ,1.605
     .01     .01     .01     .01    22.8    25.7    29.6    32.7
River Rch & RM=Wigwam Brook,Wigwam Brook    ,4.6443
     .01     .01     .01     .01    18.8    21.3    24.4      27
River Rch & RM=Wigwam Brook,Wigwam Brook    ,3.5404
     .01     .01     .01     .01    26.2    29.8    33.9    37.8
Boundary for River Rch & Prof#=B1,B1              , 1
Up Type= 3
Up Slope=1.911504E-03
Dn Type= 0
Boundary for River Rch & Prof#=B1,B1              , 2
Up Type= 3
Up Slope=1.911504E-03
Dn Type= 0
Boundary for River Rch & Prof#=B1,B1              , 3
Up Type= 3
Up Slope=1.911504E-03
Dn Type= 0
Boundary for River Rch & Prof#=B1,B1              , 4
Up Type= 3
Up Slope=1.911504E-03
Dn Type= 0
Boundary for River Rch & Prof#=B1,B1              , 5
Up Type= 3
Up Slope=1.911504E-03
Dn Type= 0
Boundary for River Rch & Prof#=B1,B1              , 6
Up Type= 3
Up Slope=1.911504E-03
Dn Type= 0
Boundary for River Rch & Prof#=B1,B1              , 7
Up Type= 3
Up Slope=1.911504E-03
Dn Type= 0
Boundary for River Rch & Prof#=B1,B1              , 8
Up Type= 3
Up Slope=1.911504E-03
Dn Type= 0
Boundary for River Rch & Prof#=Badger Brk,Badger Brk      , 1
Up Type= 3
Up Slope=0.00004
Dn Type= 0
Boundary for River Rch & Prof#=Badger Brk,Badger Brk      , 2
Up Type= 3
Up Slope=0.00004
Dn Type= 0
Boundary for River Rch & Prof#=Badger Brk,Badger Brk      , 3
Up Type= 3
Up Slope=0.00004
Dn Type= 0
Boundary for River Rch & Prof#=Badger Brk,Badger Brk      , 4
Up Type= 3
Up Slope=0.00004
Dn Type= 0
Boundary for River Rch & Prof#=Badger Brk,Badger Brk      , 5
Up Type= 3
Up Slope=0.00004
Dn Type= 0
Boundary for River Rch & Prof#=Badger Brk,Badger Brk      , 6
Up Type= 3
Up Slope=0.00004
Dn Type= 0
Boundary for River Rch & Prof#=Badger Brk,Badger Brk      , 7
Up Type= 3
Up Slope=0.00004
Dn Type= 0
Boundary for River Rch & Prof#=Badger Brk,Badger Brk      , 8
Up Type= 3
Up Slope=0.00004
Dn Type= 0
Boundary for River Rch & Prof#=BF1,BF1             , 1
Up Type= 3
Up Slope=5.857143E-03
Dn Type= 0
Boundary for River Rch & Prof#=BF1,BF1             , 2
Up Type= 3
Up Slope=5.857143E-03
Dn Type= 0
Boundary for River Rch & Prof#=BF1,BF1             , 3
Up Type= 3
Up Slope=5.857143E-03
Dn Type= 0
Boundary for River Rch & Prof#=BF1,BF1             , 4
Up Type= 3
Up Slope=5.857143E-03
Dn Type= 0
Boundary for River Rch & Prof#=BF1,BF1             , 5
Up Type= 3
Up Slope=5.857143E-03
Dn Type= 0
Boundary for River Rch & Prof#=BF1,BF1             , 6
Up Type= 3
Up Slope=5.857143E-03
Dn Type= 0
Boundary for River Rch & Prof#=BF1,BF1             , 7
Up Type= 3
Up Slope=5.857143E-03
Dn Type= 0
Boundary for River Rch & Prof#=BF1,BF1             , 8
Up Type= 3
Up Slope=5.857143E-03
Dn Type= 0
Boundary for River Rch & Prof#=BF2,BF2             , 1
Up Type= 3
Up Slope=1.396614E-02
Dn Type= 0
Boundary for River Rch & Prof#=BF2,BF2             , 2
Up Type= 3
Up Slope=1.396614E-02
Dn Type= 0
Boundary for River Rch & Prof#=BF2,BF2             , 3
Up Type= 3
Up Slope=1.396614E-02
Dn Type= 0
Boundary for River Rch & Prof#=BF2,BF2             , 4
Up Type= 3
Up Slope=1.396614E-02
Dn Type= 0
Boundary for River Rch & Prof#=BF2,BF2             , 5
Up Type= 3
Up Slope=1.396614E-02
Dn Type= 0
Boundary for River Rch & Prof#=BF2,BF2             , 6
Up Type= 3
Up Slope=1.396614E-02
Dn Type= 0
Boundary for River Rch & Prof#=BF2,BF2             , 7
Up Type= 3
Up Slope=1.396614E-02
Dn Type= 0
Boundary for River Rch & Prof#=BF2,BF2             , 8
Up Type= 3
Up Slope=1.396614E-02
Dn Type= 0
Boundary for River Rch & Prof#=BF3,BF3             , 1
Up Type= 3
Up Slope=2.193798E-03
Dn Type= 0
Boundary for River Rch & Prof#=BF3,BF3             , 2
Up Type= 3
Up Slope=2.193798E-03
Dn Type= 0
Boundary for River Rch & Prof#=BF3,BF3             , 3
Up Type= 3
Up Slope=2.193798E-03
Dn Type= 0
Boundary for River Rch & Prof#=BF3,BF3             , 4
Up Type= 3
Up Slope=2.193798E-03
Dn Type= 0
Boundary for River Rch & Prof#=BF3,BF3             , 5
Up Type= 3
Up Slope=2.193798E-03
Dn Type= 0
Boundary for River Rch & Prof#=BF3,BF3             , 6
Up Type= 3
Up Slope=2.193798E-03
Dn Type= 0
Boundary for River Rch & Prof#=BF3,BF3             , 7
Up Type= 3
Up Slope=2.193798E-03
Dn Type= 0
Boundary for River Rch & Prof#=BF3,BF3             , 8
Up Type= 3
Up Slope=2.193798E-03
Dn Type= 0
Boundary for River Rch & Prof#=BF4,BF4             , 1
Up Type= 3
Up Slope=4.040541E-03
Dn Type= 0
Boundary for River Rch & Prof#=BF4,BF4             , 2
Up Type= 3
Up Slope=4.040541E-03
Dn Type= 0
Boundary for River Rch & Prof#=BF4,BF4             , 3
Up Type= 3
Up Slope=4.040541E-03
Dn Type= 0
Boundary for River Rch & Prof#=BF4,BF4             , 4
Up Type= 3
Up Slope=4.040541E-03
Dn Type= 0
Boundary for River Rch & Prof#=BF4,BF4             , 5
Up Type= 3
Up Slope=4.040541E-03
Dn Type= 0
Boundary for River Rch & Prof#=BF4,BF4             , 6
Up Type= 3
Up Slope=4.040541E-03
Dn Type= 0
Boundary for River Rch & Prof#=BF4,BF4             , 7
Up Type= 3
Up Slope=4.040541E-03
Dn Type= 0
Boundary for River Rch & Prof#=BF4,BF4             , 8
Up Type= 3
Up Slope=4.040541E-03
Dn Type= 0
Boundary for River Rch & Prof#=Corduroy Brk,Corduroy Brk    , 1
Up Type= 3
Up Slope=3.948357E-03
Dn Type= 0
Boundary for River Rch & Prof#=Corduroy Brk,Corduroy Brk    , 2
Up Type= 3
Up Slope=3.948357E-03
Dn Type= 0
Boundary for River Rch & Prof#=Corduroy Brk,Corduroy Brk    , 3
Up Type= 3
Up Slope=3.948357E-03
Dn Type= 0
Boundary for River Rch & Prof#=Corduroy Brk,Corduroy Brk    , 4
Up Type= 3
Up Slope=3.948357E-03
Dn Type= 0
Boundary for River Rch & Prof#=Corduroy Brk,Corduroy Brk    , 5
Up Type= 3
Up Slope=3.948357E-03
Dn Type= 0
Boundary for River Rch & Prof#=Corduroy Brk,Corduroy Brk    , 6
Up Type= 3
Up Slope=3.948357E-03
Dn Type= 0
Boundary for River Rch & Prof#=Corduroy Brk,Corduroy Brk    , 7
Up Type= 3
Up Slope=3.948357E-03
Dn Type= 0
Boundary for River Rch & Prof#=Corduroy Brk,Corduroy Brk    , 8
Up Type= 3
Up Slope=3.948357E-03
Dn Type= 0
Boundary for River Rch & Prof#=Exploits River,Mill to LRI     , 1
Up Type= 1
Up Known WS=146.6381
Dn Type= 0
Boundary for River Rch & Prof#=Exploits River,Mill to LRI     , 2
Up Type= 1
Up Known WS=146.6381
Dn Type= 0
Boundary for River Rch & Prof#=Exploits River,Mill to LRI     , 3
Up Type= 1
Up Known WS=146.6381
Dn Type= 0
Boundary for River Rch & Prof#=Exploits River,Mill to LRI     , 4
Up Type= 1
Up Known WS=146.6381
Dn Type= 0
Boundary for River Rch & Prof#=Exploits River,Mill to LRI     , 5
Up Type= 1
Up Known WS=146.6381
Dn Type= 0
Boundary for River Rch & Prof#=Exploits River,Mill to LRI     , 6
Up Type= 1
Up Known WS=146.6381
Dn Type= 0
Boundary for River Rch & Prof#=Exploits River,Mill to LRI     , 7
Up Type= 1
Up Known WS=146.6381
Dn Type= 0
Boundary for River Rch & Prof#=Exploits River,Mill to LRI     , 8
Up Type= 1
Up Known WS=146.6381
Dn Type= 0
Boundary for River Rch & Prof#=Exploits River,LRI to Badger   , 1
Up Type= 0
Dn Type= 0
Boundary for River Rch & Prof#=Exploits River,LRI to Badger   , 2
Up Type= 0
Dn Type= 0
Boundary for River Rch & Prof#=Exploits River,LRI to Badger   , 3
Up Type= 0
Dn Type= 0
Boundary for River Rch & Prof#=Exploits River,LRI to Badger   , 4
Up Type= 0
Dn Type= 0
Boundary for River Rch & Prof#=Exploits River,LRI to Badger   , 5
Up Type= 0
Dn Type= 0
Boundary for River Rch & Prof#=Exploits River,LRI to Badger   , 6
Up Type= 0
Dn Type= 0
Boundary for River Rch & Prof#=Exploits River,LRI to Badger   , 7
Up Type= 0
Dn Type= 0
Boundary for River Rch & Prof#=Exploits River,LRI to Badger   , 8
Up Type= 0
Dn Type= 0
Boundary for River Rch & Prof#=Exploits River,Badger to Wigwam, 1
Up Type= 0
Dn Type= 0
Boundary for River Rch & Prof#=Exploits River,Badger to Wigwam, 2
Up Type= 0
Dn Type= 0
Boundary for River Rch & Prof#=Exploits River,Badger to Wigwam, 3
Up Type= 0
Dn Type= 0
Boundary for River Rch & Prof#=Exploits River,Badger to Wigwam, 4
Up Type= 0
Dn Type= 0
Boundary for River Rch & Prof#=Exploits River,Badger to Wigwam, 5
Up Type= 0
Dn Type= 0
Boundary for River Rch & Prof#=Exploits River,Badger to Wigwam, 6
Up Type= 0
Dn Type= 0
Boundary for River Rch & Prof#=Exploits River,Badger to Wigwam, 7
Up Type= 0
Dn Type= 0
Boundary for River Rch & Prof#=Exploits River,Badger to Wigwam, 8
Up Type= 0
Dn Type= 0
Boundary for River Rch & Prof#=Exploits River,Wigwam to RP    , 1
Up Type= 0
Dn Type= 0
Boundary for River Rch & Prof#=Exploits River,Wigwam to RP    , 2
Up Type= 0
Dn Type= 0
Boundary for River Rch & Prof#=Exploits River,Wigwam to RP    , 3
Up Type= 0
Dn Type= 0
Boundary for River Rch & Prof#=Exploits River,Wigwam to RP    , 4
Up Type= 0
Dn Type= 0
Boundary for River Rch & Prof#=Exploits River,Wigwam to RP    , 5
Up Type= 0
Dn Type= 0
Boundary for River Rch & Prof#=Exploits River,Wigwam to RP    , 6
Up Type= 0
Dn Type= 0
Boundary for River Rch & Prof#=Exploits River,Wigwam to RP    , 7
Up Type= 0
Dn Type= 0
Boundary for River Rch & Prof#=Exploits River,Wigwam to RP    , 8
Up Type= 0
Dn Type= 0
Boundary for River Rch & Prof#=Exploits River,RP to CB        , 1
Up Type= 0
Dn Type= 0
Boundary for River Rch & Prof#=Exploits River,RP to CB        , 2
Up Type= 0
Dn Type= 0
Boundary for River Rch & Prof#=Exploits River,RP to CB        , 3
Up Type= 0
Dn Type= 0
Boundary for River Rch & Prof#=Exploits River,RP to CB        , 4
Up Type= 0
Dn Type= 0
Boundary for River Rch & Prof#=Exploits River,RP to CB        , 5
Up Type= 0
Dn Type= 0
Boundary for River Rch & Prof#=Exploits River,RP to CB        , 6
Up Type= 0
Dn Type= 0
Boundary for River Rch & Prof#=Exploits River,RP to CB        , 7
Up Type= 0
Dn Type= 0
Boundary for River Rch & Prof#=Exploits River,RP to CB        , 8
Up Type= 0
Dn Type= 0
Boundary for River Rch & Prof#=Exploits River,CB to BF4       , 1
Up Type= 0
Dn Type= 0
Boundary for River Rch & Prof#=Exploits River,CB to BF4       , 2
Up Type= 0
Dn Type= 0
Boundary for River Rch & Prof#=Exploits River,CB to BF4       , 3
Up Type= 0
Dn Type= 0
Boundary for River Rch & Prof#=Exploits River,CB to BF4       , 4
Up Type= 0
Dn Type= 0
Boundary for River Rch & Prof#=Exploits River,CB to BF4       , 5
Up Type= 0
Dn Type= 0
Boundary for River Rch & Prof#=Exploits River,CB to BF4       , 6
Up Type= 0
Dn Type= 0
Boundary for River Rch & Prof#=Exploits River,CB to BF4       , 7
Up Type= 0
Dn Type= 0
Boundary for River Rch & Prof#=Exploits River,CB to BF4       , 8
Up Type= 0
Dn Type= 0
Boundary for River Rch & Prof#=Exploits River,BF4 to BF3      , 1
Up Type= 0
Dn Type= 0
Boundary for River Rch & Prof#=Exploits River,BF4 to BF3      , 2
Up Type= 0
Dn Type= 0
Boundary for River Rch & Prof#=Exploits River,BF4 to BF3      , 3
Up Type= 0
Dn Type= 0
Boundary for River Rch & Prof#=Exploits River,BF4 to BF3      , 4
Up Type= 0
Dn Type= 0
Boundary for River Rch & Prof#=Exploits River,BF4 to BF3      , 5
Up Type= 0
Dn Type= 0
Boundary for River Rch & Prof#=Exploits River,BF4 to BF3      , 6
Up Type= 0
Dn Type= 0
Boundary for River Rch & Prof#=Exploits River,BF4 to BF3      , 7
Up Type= 0
Dn Type= 0
Boundary for River Rch & Prof#=Exploits River,BF4 to BF3      , 8
Up Type= 0
Dn Type= 0
Boundary for River Rch & Prof#=Exploits River,BF3 to BF2      , 1
Up Type= 0
Dn Type= 0
Boundary for River Rch & Prof#=Exploits River,BF3 to BF2      , 2
Up Type= 0
Dn Type= 0
Boundary for River Rch & Prof#=Exploits River,BF3 to BF2      , 3
Up Type= 0
Dn Type= 0
Boundary for River Rch & Prof#=Exploits River,BF3 to BF2      , 4
Up Type= 0
Dn Type= 0
Boundary for River Rch & Prof#=Exploits River,BF3 to BF2      , 5
Up Type= 0
Dn Type= 0
Boundary for River Rch & Prof#=Exploits River,BF3 to BF2      , 6
Up Type= 0
Dn Type= 0
Boundary for River Rch & Prof#=Exploits River,BF3 to BF2      , 7
Up Type= 0
Dn Type= 0
Boundary for River Rch & Prof#=Exploits River,BF3 to BF2      , 8
Up Type= 0
Dn Type= 0
Boundary for River Rch & Prof#=Exploits River,BF2 to BF1      , 1
Up Type= 0
Dn Type= 0
Boundary for River Rch & Prof#=Exploits River,BF2 to BF1      , 2
Up Type= 0
Dn Type= 0
Boundary for River Rch & Prof#=Exploits River,BF2 to BF1      , 3
Up Type= 0
Dn Type= 0
Boundary for River Rch & Prof#=Exploits River,BF2 to BF1      , 4
Up Type= 0
Dn Type= 0
Boundary for River Rch & Prof#=Exploits River,BF2 to BF1      , 5
Up Type= 0
Dn Type= 0
Boundary for River Rch & Prof#=Exploits River,BF2 to BF1      , 6
Up Type= 0
Dn Type= 0
Boundary for River Rch & Prof#=Exploits River,BF2 to BF1      , 7
Up Type= 0
Dn Type= 0
Boundary for River Rch & Prof#=Exploits River,BF2 to BF1      , 8
Up Type= 0
Dn Type= 0
Boundary for River Rch & Prof#=Exploits River,BF1 to Outlet   , 1
Up Type= 0
Dn Type= 1
Dn Known WS=0.4
Boundary for River Rch & Prof#=Exploits River,BF1 to Outlet   , 2
Up Type= 0
Dn Type= 1
Dn Known WS=1.3
Boundary for River Rch & Prof#=Exploits River,BF1 to Outlet   , 3
Up Type= 0
Dn Type= 1
Dn Known WS=0.4
Boundary for River Rch & Prof#=Exploits River,BF1 to Outlet   , 4
Up Type= 0
Dn Type= 1
Dn Known WS=1.3
Boundary for River Rch & Prof#=Exploits River,BF1 to Outlet   , 5
Up Type= 0
Dn Type= 1
Dn Known WS=0.4
Boundary for River Rch & Prof#=Exploits River,BF1 to Outlet   , 6
Up Type= 0
Dn Type= 1
Dn Known WS=0.4
Boundary for River Rch & Prof#=Exploits River,BF1 to Outlet   , 7
Up Type= 0
Dn Type= 1
Dn Known WS=0.4
Boundary for River Rch & Prof#=Exploits River,BF1 to Outlet   , 8
Up Type= 0
Dn Type= 1
Dn Known WS=0.4
Boundary for River Rch & Prof#=GF1,GF1             , 1
Up Type= 3
Up Slope=0.0180531
Dn Type= 3
Dn Slope=2.026667E-02
Boundary for River Rch & Prof#=GF1,GF1             , 2
Up Type= 3
Up Slope=0.0180531
Dn Type= 3
Dn Slope=2.026667E-02
Boundary for River Rch & Prof#=GF1,GF1             , 3
Up Type= 3
Up Slope=0.0180531
Dn Type= 3
Dn Slope=2.026667E-02
Boundary for River Rch & Prof#=GF1,GF1             , 4
Up Type= 3
Up Slope=0.0180531
Dn Type= 3
Dn Slope=2.026667E-02
Boundary for River Rch & Prof#=GF1,GF1             , 5
Up Type= 3
Up Slope=0.0180531
Dn Type= 3
Dn Slope=2.026667E-02
Boundary for River Rch & Prof#=GF1,GF1             , 6
Up Type= 3
Up Slope=0.0180531
Dn Type= 3
Dn Slope=2.026667E-02
Boundary for River Rch & Prof#=GF1,GF1             , 7
Up Type= 3
Up Slope=0.0180531
Dn Type= 3
Dn Slope=2.026667E-02
Boundary for River Rch & Prof#=GF1,GF1             , 8
Up Type= 3
Up Slope=0.0180531
Dn Type= 3
Dn Slope=2.026667E-02
Boundary for River Rch & Prof#=Little Red Ind,LRI to B1       , 1
Up Type= 3
Up Slope=0.001464
Dn Type= 0
Boundary for River Rch & Prof#=Little Red Ind,LRI to B1       , 2
Up Type= 3
Up Slope=0.001464
Dn Type= 0
Boundary for River Rch & Prof#=Little Red Ind,LRI to B1       , 3
Up Type= 3
Up Slope=0.001464
Dn Type= 0
Boundary for River Rch & Prof#=Little Red Ind,LRI to B1       , 4
Up Type= 3
Up Slope=0.001464
Dn Type= 0
Boundary for River Rch & Prof#=Little Red Ind,LRI to B1       , 5
Up Type= 3
Up Slope=0.001464
Dn Type= 0
Boundary for River Rch & Prof#=Little Red Ind,LRI to B1       , 6
Up Type= 3
Up Slope=0.001464
Dn Type= 0
Boundary for River Rch & Prof#=Little Red Ind,LRI to B1       , 7
Up Type= 3
Up Slope=0.001464
Dn Type= 0
Boundary for River Rch & Prof#=Little Red Ind,LRI to B1       , 8
Up Type= 3
Up Slope=0.001464
Dn Type= 0
Boundary for River Rch & Prof#=Little Red Ind,B1 to Expl      , 1
Up Type= 0
Dn Type= 0
Boundary for River Rch & Prof#=Little Red Ind,B1 to Expl      , 2
Up Type= 0
Dn Type= 0
Boundary for River Rch & Prof#=Little Red Ind,B1 to Expl      , 3
Up Type= 0
Dn Type= 0
Boundary for River Rch & Prof#=Little Red Ind,B1 to Expl      , 4
Up Type= 0
Dn Type= 0
Boundary for River Rch & Prof#=Little Red Ind,B1 to Expl      , 5
Up Type= 0
Dn Type= 0
Boundary for River Rch & Prof#=Little Red Ind,B1 to Expl      , 6
Up Type= 0
Dn Type= 0
Boundary for River Rch & Prof#=Little Red Ind,B1 to Expl      , 7
Up Type= 0
Dn Type= 0
Boundary for River Rch & Prof#=Little Red Ind,B1 to Expl      , 8
Up Type= 0
Dn Type= 0
Boundary for River Rch & Prof#=Little Rushy Pd,Little Rushy Pd , 1
Up Type= 3
Up Slope=4.474684E-03
Dn Type= 0
Boundary for River Rch & Prof#=Little Rushy Pd,Little Rushy Pd , 2
Up Type= 3
Up Slope=4.474684E-03
Dn Type= 0
Boundary for River Rch & Prof#=Little Rushy Pd,Little Rushy Pd , 3
Up Type= 3
Up Slope=4.474684E-03
Dn Type= 0
Boundary for River Rch & Prof#=Little Rushy Pd,Little Rushy Pd , 4
Up Type= 3
Up Slope=4.474684E-03
Dn Type= 0
Boundary for River Rch & Prof#=Little Rushy Pd,Little Rushy Pd , 5
Up Type= 3
Up Slope=4.474684E-03
Dn Type= 0
Boundary for River Rch & Prof#=Little Rushy Pd,Little Rushy Pd , 6
Up Type= 3
Up Slope=4.474684E-03
Dn Type= 0
Boundary for River Rch & Prof#=Little Rushy Pd,Little Rushy Pd , 7
Up Type= 3
Up Slope=4.474684E-03
Dn Type= 0
Boundary for River Rch & Prof#=Little Rushy Pd,Little Rushy Pd , 8
Up Type= 3
Up Slope=4.474684E-03
Dn Type= 0
Boundary for River Rch & Prof#=Mullens Pond,Mullens Pond    , 1
Up Type= 3
Up Slope=2.605769E-03
Dn Type= 4
Dn Rating Curve # Pts= 21
       0    72.7      .2   73.15      .4   73.37      .6   73.56      .8   73.74
       1    73.9     1.2   73.95     1.4   73.99     1.6   74.01     1.8   74.03
       2   74.04     2.2   74.06     2.4   74.07     2.6   74.08     2.8   74.09
       3    74.1     3.2    74.1     3.4   74.11     3.6   74.12     3.8   74.12
       4   74.13
Boundary for River Rch & Prof#=Mullens Pond,Mullens Pond    , 2
Up Type= 3
Up Slope=2.605769E-03
Dn Type= 3
Dn Slope=0.02
Boundary for River Rch & Prof#=Mullens Pond,Mullens Pond    , 3
Up Type= 3
Up Slope=2.605769E-03
Dn Type= 3
Dn Slope=0.02
Boundary for River Rch & Prof#=Mullens Pond,Mullens Pond    , 4
Up Type= 3
Up Slope=2.605769E-03
Dn Type= 3
Dn Slope=0.02
Boundary for River Rch & Prof#=Mullens Pond,Mullens Pond    , 5
Up Type= 3
Up Slope=2.605769E-03
Dn Type= 3
Dn Slope=0.02
Boundary for River Rch & Prof#=Mullens Pond,Mullens Pond    , 6
Up Type= 3
Up Slope=2.605769E-03
Dn Type= 3
Dn Slope=0.02
Boundary for River Rch & Prof#=Mullens Pond,Mullens Pond    , 7
Up Type= 3
Up Slope=2.605769E-03
Dn Type= 3
Dn Slope=0.02
Boundary for River Rch & Prof#=Mullens Pond,Mullens Pond    , 8
Up Type= 3
Up Slope=2.605769E-03
Dn Type= 3
Dn Slope=0.02
Boundary for River Rch & Prof#=Rushy Pond,Rushy Pond      , 1
Up Type= 0
Dn Type= 0
Boundary for River Rch & Prof#=Rushy Pond,Rushy Pond      , 2
Up Type= 0
Dn Type= 0
Boundary for River Rch & Prof#=Rushy Pond,Rushy Pond      , 3
Up Type= 0
Dn Type= 0
Boundary for River Rch & Prof#=Rushy Pond,Rushy Pond      , 4
Up Type= 0
Dn Type= 0
Boundary for River Rch & Prof#=Rushy Pond,Rushy Pond      , 5
Up Type= 0
Dn Type= 0
Boundary for River Rch & Prof#=Rushy Pond,Rushy Pond      , 6
Up Type= 0
Dn Type= 0
Boundary for River Rch & Prof#=Rushy Pond,Rushy Pond      , 7
Up Type= 0
Dn Type= 0
Boundary for River Rch & Prof#=Rushy Pond,Rushy Pond      , 8
Up Type= 0
Dn Type= 0
Boundary for River Rch & Prof#=Wigwam Brook,Wigwam Brook    , 1
Up Type= 3
Up Slope=2.93038E-03
Dn Type= 0
Boundary for River Rch & Prof#=Wigwam Brook,Wigwam Brook    , 2
Up Type= 3
Up Slope=2.93038E-03
Dn Type= 0
Boundary for River Rch & Prof#=Wigwam Brook,Wigwam Brook    , 3
Up Type= 3
Up Slope=2.93038E-03
Dn Type= 0
Boundary for River Rch & Prof#=Wigwam Brook,Wigwam Brook    , 4
Up Type= 3
Up Slope=2.93038E-03
Dn Type= 0
Boundary for River Rch & Prof#=Wigwam Brook,Wigwam Brook    , 5
Up Type= 3
Up Slope=2.93038E-03
Dn Type= 0
Boundary for River Rch & Prof#=Wigwam Brook,Wigwam Brook    , 6
Up Type= 3
Up Slope=2.93038E-03
Dn Type= 0
Boundary for River Rch & Prof#=Wigwam Brook,Wigwam Brook    , 7
Up Type= 3
Up Slope=2.93038E-03
Dn Type= 0
Boundary for River Rch & Prof#=Wigwam Brook,Wigwam Brook    , 8
Up Type= 3
Up Slope=2.93038E-03
Dn Type= 0
Gate Openings=Exploits River  ,CB to BF4       ,43.309  ,Gate #1                         ,
    3.66      17    3.66      17    3.66      17    3.66      17    3.66      17
    3.66      17    3.66      17    3.66      17
Gate Openings=Exploits River  ,CB to BF4       ,43.2577 ,Outside Gate                    ,
  3.9624       1  3.9624       1  3.9624       1  3.9624       1  3.9624       1
  3.9624       1  3.9624       1  3.9624       1
Gate Openings=Exploits River  ,CB to BF4       ,43.2577 ,Obermeyer                       ,
     1.5       1     1.5       1     1.5       1     1.5       1     1.5       1
     1.5       1     1.5       1     1.5       1
Gate Openings=Exploits River  ,CB to BF4       ,43.231  ,Inside Gate                     ,
  2.1336       1  2.1336       1  2.1336       1  2.1336       1  2.1336       1
  2.1336       1  2.1336       1  2.1336       1
Gate Openings=Exploits River  ,CB to BF4       ,43.231  ,RCC Fboards                     ,
      .9       1      .9       1      .9       1      .9       1      .9       1
      .9       1      .9       1      .9       1
Gate Openings=Exploits River  ,BF3 to BF2      ,23.7635 ,BF Gates                        ,
   4.328       9   4.328       9   4.328       9   4.328       9   4.328       9
   4.328       9   4.328       9   4.328       9
Gate Openings=Exploits River  ,BF3 to BF2      ,23.7635 ,BF Fboards                      ,
    1.22       1    1.22       1    1.22       1    1.22       1    1.22       1
    1.22       1    1.22       1    1.22       1
DSS Import StartDate=01jun2019
DSS Import StartTime=24:00
DSS Import EndDate=08jun2019
DSS Import EndTime=00:00
DSS Import GetInterval= 0
DSS Import Interval=1DAY
DSS Import GetPeak= 1
DSS Import FillOption= 1
TSRecord= 1
TSRecord Loc=B1              ,B1              ,0.9685
TSRecord DssFilename=dss
TSRecord DssPathname=//SUBSTR1TOLITREDIND/FLOW/01JUN2019/1HOUR/RUN:100YEAR_SPILL_OPEN/
TSRecord End
TSRecord= 2
TSRecord Loc=Badger Brk      ,Badger Brk      ,1.9217
TSRecord DssFilename=dss
TSRecord DssPathname=//BADGER1/FLOW/01JUN2019/1HOUR/RUN:100YEAR_SPILL_OPEN/
TSRecord End
TSRecord= 3
TSRecord Loc=BF1             ,BF1             ,1.2372
TSRecord DssFilename=dss
TSRecord DssPathname=//SUBSTREAM5TOEXPL/FLOW/01JUN2019/1HOUR/RUN:100YEAR_SPILL_OPEN/
TSRecord End
TSRecord= 4
TSRecord Loc=BF2             ,BF2             ,1.2490
TSRecord DssFilename=dss
TSRecord DssPathname=//SUBSTREAM4RURAL/FLOW/01JUN2019/1HOUR/RUN:100YEAR_SPILL_OPEN/
TSRecord End
TSRecord= 5
TSRecord Loc=BF2             ,BF2             ,0.3773
TSRecord DssFilename=dss
TSRecord DssPathname=//SUBSTREAM4URBAN/FLOW/01JUN2019/1HOUR/RUN:100YEAR_SPILL_OPEN/
TSRecord End
TSRecord= 6
TSRecord Loc=BF3             ,BF3             ,2.1832
TSRecord DssFilename=dss
TSRecord DssPathname=//SUBSTREAM3RURAL/FLOW/01JUN2019/1HOUR/RUN:100YEAR_SPILL_OPEN/
TSRecord End
TSRecord= 7
TSRecord Loc=BF3             ,BF3             ,0.8646
TSRecord DssFilename=dss
TSRecord DssPathname=//SUBSTREAM3URBAN/FLOW/01JUN2019/1HOUR/RUN:100YEAR_SPILL_OPEN/
TSRecord End
TSRecord= 8
TSRecord Loc=BF4             ,BF4             ,0.9422
TSRecord DssFilename=dss
TSRecord DssPathname=//SUBSTREAM2RURAL/FLOW/01JUN2019/1HOUR/RUN:100YEAR_SPILL_OPEN/
TSRecord End
TSRecord= 9
TSRecord Loc=BF4             ,BF4             ,0.8648
TSRecord DssFilename=dss
TSRecord DssPathname=//SUBSTREAM2URBAN/FLOW/01JUN2019/1HOUR/RUN:100YEAR_SPILL_OPEN/
TSRecord End
TSRecord= 10
TSRecord Loc=Corduroy Brk    ,Corduroy Brk    ,3.8918
TSRecord DssFilename=dss
TSRecord DssPathname=//SUBCORDBROOK5RURAL/FLOW/01JUN2019/1HOUR/RUN:100YEAR_SPILL_OPEN/
TSRecord End
TSRecord= 11
TSRecord Loc=Corduroy Brk    ,Corduroy Brk    ,3.3476
TSRecord DssFilename=dss
TSRecord DssPathname=//SUBCORDUROYBROOK4/FLOW/01JUN2019/1HOUR/RUN:100YEAR_SPILL_OPEN/
TSRecord End
TSRecord= 12
TSRecord Loc=Corduroy Brk    ,Corduroy Brk    ,1.8184
TSRecord DssFilename=dss
TSRecord DssPathname=//SUBCORDUROYBROOK3/FLOW/01JUN2019/1HOUR/RUN:100YEAR_SPILL_OPEN/
TSRecord End
TSRecord= 13
TSRecord Loc=Corduroy Brk    ,Corduroy Brk    ,1.2395
TSRecord DssFilename=dss
TSRecord DssPathname=//SUBCORD2TONEWGAUGE/FLOW/01JUN2019/1HOUR/RUN:100YEAR_SPILL_OPEN/
TSRecord End
TSRecord= 14
TSRecord Loc=Exploits River  ,Mill to LRI     ,127.9419
TSRecord DssFilename=dss
TSRecord DssPathname=//EXPLOITSRIVER24/FLOW/01JUN2019/1HOUR/RUN:100YEAR_SPILL_OPEN/
TSRecord End
TSRecord= 15
TSRecord Loc=Exploits River  ,Mill to LRI     ,98.9083
TSRecord DssFilename=dss
TSRecord DssPathname=//SUBEXPLMILLTONOEL/FLOW/01JUN2019/1HOUR/RUN:100YEAR_SPILL_OPEN/
TSRecord End
TSRecord= 16
TSRecord Loc=Exploits River  ,Mill to LRI     ,75.9221
TSRecord DssFilename=dss
TSRecord DssPathname=//SUBEXPLNOELTOBAD/FLOW/01JUN2019/1HOUR/RUN:100YEAR_SPILL_OPEN/
TSRecord End
TSRecord= 17
TSRecord Loc=Exploits River  ,Badger to Wigwam,53.6747
TSRecord DssFilename=dss
TSRecord DssPathname=//SUBEXPLBAGERTOCHAR/FLOW/01JUN2019/1HOUR/RUN:100YEAR_SPILL_OPEN/
TSRecord End
TSRecord= 18
TSRecord Loc=Exploits River  ,Badger to Wigwam,51.6126
TSRecord DssFilename=dss
TSRecord DssPathname=//SUBSANDYBRKDAMTOEXPL/FLOW/01JUN2019/1HOUR/RUN:100YEAR_SPILL_OPEN/
TSRecord End
TSRecord= 19
TSRecord Loc=Exploits River  ,Badger to Wigwam,50.7343
TSRecord DssFilename=dss
TSRecord DssPathname=//SANDYBROOK1/FLOW/01JUN2019/1HOUR/RUN:100YEAR_SPILL_OPEN/
TSRecord End
TSRecord= 20
TSRecord Loc=Exploits River  ,RP to CB        ,46.8401
TSRecord DssFilename=dss
TSRecord DssPathname=//SUBEXPLCHARTOGOOD/FLOW/01JUN2019/1HOUR/RUN:100YEAR_SPILL_OPEN/
TSRecord End
TSRecord= 21
TSRecord Loc=Exploits River  ,CB to BF4       ,43.2587
TSRecord DssFilename=dss
TSRecord DssPathname=//SUBEXPLGOODTOGRAND/FLOW/01JUN2019/1HOUR/RUN:100YEAR_SPILL_OPEN/
TSRecord End
TSRecord= 22
TSRecord Loc=Exploits River  ,CB to BF4       ,41.6238
TSRecord DssFilename=dss
TSRecord DssPathname=//SUBEXPLGRFALLSTOST/FLOW/01JUN2019/1HOUR/RUN:100YEAR_SPILL_OPEN/
TSRecord End
TSRecord= 23
TSRecord Loc=Exploits River  ,CB to BF4       ,33.2970
TSRecord DssFilename=dss
TSRecord DssPathname=//SUBEXPLSTONYTOGRRATT/FLOW/01JUN2019/1HOUR/RUN:100YEAR_SPILL_OPEN/
TSRecord End
TSRecord= 24
TSRecord Loc=Exploits River  ,CB to BF4       ,31.6595
TSRecord DssFilename=dss
TSRecord DssPathname=//GREATRATTLINGBROOK1/FLOW/01JUN2019/1HOUR/RUN:100YEAR_SPILL_OPEN/
TSRecord End
TSRecord= 25
TSRecord Loc=Exploits River  ,CB to BF4       ,30.6038
TSRecord DssFilename=dss
TSRecord DssPathname=//SUBGRRATTTOEXPL/FLOW/01JUN2019/1HOUR/RUN:100YEAR_SPILL_OPEN/
TSRecord End
TSRecord= 26
TSRecord Loc=Exploits River  ,BF3 to BF2      ,23.7697
TSRecord DssFilename=dss
TSRecord DssPathname=//SUBEXPLGRRATTTOBISH/FLOW/01JUN2019/1HOUR/RUN:100YEAR_SPILL_OPEN/
TSRecord End
TSRecord= 27
TSRecord Loc=Exploits River  ,BF2 to BF1      ,21.7690
TSRecord DssFilename=dss
TSRecord DssPathname=//SUBEXPLBISHTOGAUGE/FLOW/01JUN2019/1HOUR/RUN:100YEAR_SPILL_OPEN/
TSRecord End
TSRecord= 28
TSRecord Loc=Exploits River  ,BF1 to Outlet   ,18.0852
TSRecord DssFilename=dss
TSRecord DssPathname=//SUBJUMPERSBROOK/FLOW/01JUN2019/1HOUR/RUN:100YEAR_SPILL_OPEN/
TSRecord End
TSRecord= 29
TSRecord Loc=Exploits River  ,BF1 to Outlet   ,9.3990
TSRecord DssFilename=dss
TSRecord DssPathname=//SUBEXPLNEWGAUTOOUT/FLOW/01JUN2019/1HOUR/RUN:100YEAR_SPILL_OPEN/
TSRecord End
TSRecord= 30
TSRecord Loc=Exploits River  ,BF1 to Outlet   ,8.4354
TSRecord DssFilename=dss
TSRecord DssPathname=//SUBEASTERN/FLOW/01JUN2019/1HOUR/RUN:100YEAR_SPILL_OPEN/
TSRecord End
TSRecord= 31
TSRecord Loc=Exploits River  ,BF1 to Outlet   ,3.1711
TSRecord DssFilename=dss
TSRecord DssPathname=//SUBOUTLET1/FLOW/01JUN2019/1HOUR/RUN:100YEAR_SPILL_OPEN/
TSRecord End
TSRecord= 32
TSRecord Loc=Exploits River  ,BF1 to Outlet   ,0.0989
TSRecord DssFilename=dss
TSRecord DssPathname=//SUBOUTLET2/FLOW/01JUN2019/1HOUR/RUN:100YEAR_SPILL_OPEN/
TSRecord End
TSRecord= 33
TSRecord Loc=GF1             ,GF1             ,4.002117
TSRecord DssFilename=dss
TSRecord DssPathname=//SUBPETERS4/FLOW/01JUN2019/1HOUR/RUN:100YEAR_SPILL_OPEN/
TSRecord End
TSRecord= 34
TSRecord Loc=GF1             ,GF1             ,3.1868
TSRecord DssFilename=dss
TSRecord DssPathname=//SUBPETERS3/FLOW/01JUN2019/1HOUR/RUN:100YEAR_SPILL_OPEN/
TSRecord End
TSRecord= 35
TSRecord Loc=GF1             ,GF1             ,1.3701
TSRecord DssFilename=dss
TSRecord DssPathname=//SUBPETERS2/FLOW/01JUN2019/1HOUR/RUN:100YEAR_SPILL_OPEN/
TSRecord End
TSRecord= 36
TSRecord Loc=GF1             ,GF1             ,0.0107
TSRecord DssFilename=dss
TSRecord DssPathname=//SUBPETERSRIV1TOOUTL/FLOW/01JUN2019/1HOUR/RUN:100YEAR_SPILL_OPEN/
TSRecord End
TSRecord= 37
TSRecord Loc=Little Red Ind  ,LRI to B1       ,1.4448
TSRecord DssFilename=dss
TSRecord DssPathname=//SUBLITTLEREDINDIAN/FLOW/01JUN2019/1HOUR/RUN:100YEAR_SPILL_OPEN/
TSRecord End
TSRecord= 38
TSRecord Loc=Little Rushy Pd ,Little Rushy Pd ,0.5608
TSRecord DssFilename=dss
TSRecord DssPathname=//SUBLITTLERUSHYPOND/FLOW/01JUN2019/1HOUR/RUN:100YEAR_SPILL_OPEN/
TSRecord End
TSRecord= 39
TSRecord Loc=Mullens Pond    ,Mullens Pond    ,0.4097
TSRecord DssFilename=dss
TSRecord DssPathname=//SUBSTREAM6TOSEWER/FLOW/01JUN2019/1HOUR/RUN:100YEAR_SPILL_OPEN/
TSRecord End
TSRecord= 40
TSRecord Loc=Rushy Pond      ,Rushy Pond      ,1.605
TSRecord DssFilename=dss
TSRecord DssPathname=//SUBTORUSHYATTCHBR/FLOW/01JUN2019/1HOUR/RUN:100YEAR_SPILL_OPEN/
TSRecord End
TSRecord= 41
TSRecord Loc=Wigwam Brook    ,Wigwam Brook    ,4.6443
TSRecord DssFilename=dss
TSRecord DssPathname=//SUBTOWIGWAMBRKCUL3/FLOW/01JUN2019/1HOUR/RUN:100YEAR_SPILL_OPEN/
TSRecord End
TSRecord= 42
TSRecord Loc=Wigwam Brook    ,Wigwam Brook    ,4.0688
TSRecord DssFilename=dss
TSRecord DssPathname=//SUBWIGWAMBRKCUL1TO3/FLOW/01JUN2019/1HOUR/RUN:100YEAR_SPILL_OPEN/
TSRecord End
DSS File=C:\Users\neuf58278\Desktop\Exploits\HECRAS\FloodMappingModel_temp\FloodMapModel\100Year_Spill_Open.dss
Storage Area Elev=Power Canal     , 8
  60.706  60.706  60.706  60.706  60.706  60.706  60.706  60.706
Storage Area Elev=Rushy Pond      , 8
      71      71      71      71      71      71      71      71

--- Exploits_FMM.g01 (geometry) ---

Geom Title=25b_CheckRoadEl_BF4_CR_3
Program Version=5.06

Junct Name=3
Junct Desc=, 0 , 0 , 0 ,0
Up River,Reach=Badger Brk      ,Badger Brk
Up River,Reach=Exploits River  ,LRI to Badger
Dn River,Reach=Exploits River  ,Badger to Wigwam
Junc L&A=393,
Junc L&A=208,0

Junct Name=2
Junct Desc=, 0 , 0 , 0 ,0
Up River,Reach=Little Red Ind  ,B1 to Expl
Up River,Reach=Exploits River  ,Mill to LRI
Dn River,Reach=Exploits River  ,LRI to Badger
Junc L&A=325,
Junc L&A=365,0

Junct Name=Wigwam
Junct Desc=, 0 , 0 , 0 ,0
Up River,Reach=Wigwam Brook    ,Wigwam Brook
Up River,Reach=Exploits River  ,Badger to Wigwam
Dn River,Reach=Exploits River  ,Wigwam to RP
Junc L&A=1215,
Junc L&A=280.45,0

Junct Name=RP
Junct Desc=, 0 , 0 , 0 ,0
Up River,Reach=Rushy Pond      ,Rushy Pond
Up River,Reach=Exploits River  ,Wigwam to RP
Dn River,Reach=Exploits River  ,RP to CB
Junc L&A=805,
Junc L&A=939.38,0

Junct Name=B1
Junct Desc=, 0 , 0 , 0 ,0
Up River,Reach=B1              ,B1
Up River,Reach=Little Red Ind  ,LRI to B1
Dn River,Reach=Little Red Ind  ,B1 to Expl
Junc L&A=145,
Junc L&A=97,0

Junct Name=CB
Junct Desc=, 0 , 0 , 0 ,0
Up River,Reach=Corduroy Brk    ,Corduroy Brk
Up River,Reach=Exploits River  ,RP to CB
Dn River,Reach=Exploits River  ,CB to BF4
Junc L&A=347,
Junc L&A=138.53,0

Junct Name=BF4
Junct Desc=, 0 , 0 , 0 ,0
Up River,Reach=BF4             ,BF4
Up River,Reach=Exploits River  ,CB to BF4
Dn River,Reach=Exploits River  ,BF4 to BF3
Junc L&A=960,
Junc L&A=971.85,0

Junct Name=BF3
Junct Desc=, 0 , 0 , 0 ,0
Up River,Reach=BF3             ,BF3
Up River,Reach=Exploits River  ,BF4 to BF3
Dn River,Reach=Exploits River  ,BF3 to BF2
Junc L&A=740,
Junc L&A=708.28,0

Junct Name=BF2
Junct Desc=, 0 , 0 , 0 ,0
Up River,Reach=BF2             ,BF2
Up River,Reach=Exploits River  ,BF3 to BF2
Dn River,Reach=Exploits River  ,BF2 to BF1
Junc L&A=233,
Junc L&A=183.95,0

Junct Name=BF1
Junct Desc=, 0 , 0 , 0 ,0
Up River,Reach=BF1             ,BF1
Up River,Reach=Exploits River  ,BF2 to BF1
Dn River,Reach=Exploits River  ,BF1 to Outlet
Junc L&A=206,
Junc L&A=539.81,0

River Reach=B1              ,B1
Reach XY= 30
569575.6253035985426126.45058309569555.8334035995426060.19878309
569573.6409035995426021.60918309569557.7659035995425934.95798309
569537.5914035985425916.76788309569542.5523035985425895.27038309
569530.6461035985425851.94478309569538.2529035985425839.37708309
569513.4481035985425784.80668309569512.4559035985425757.35608309
569493.7355035985425738.46478309569487.7824035995425720.60538309
569491.0897035985425667.02708309569474.7384035985425593.63158309
569455.9000035985425576.93628309569453.1219035985425560.26758309
569459.4719035985425549.55188309569480.5063035985425547.56748309
569476.5376035985425522.96118309569466.9686035985425507.02688309
569442.9883035985425502.24428309569428.3833035995425488.48598309
569412.5083035995425459.69918309569356.3900035985425400.67058309
569346.8915035995425371.85738309569334.4031035985425364.44898309
569328.6881035995425349.42068309569331.6130035995425333.13598309
569318.1192035985425329.16718309 569323.882464585425285.23069908

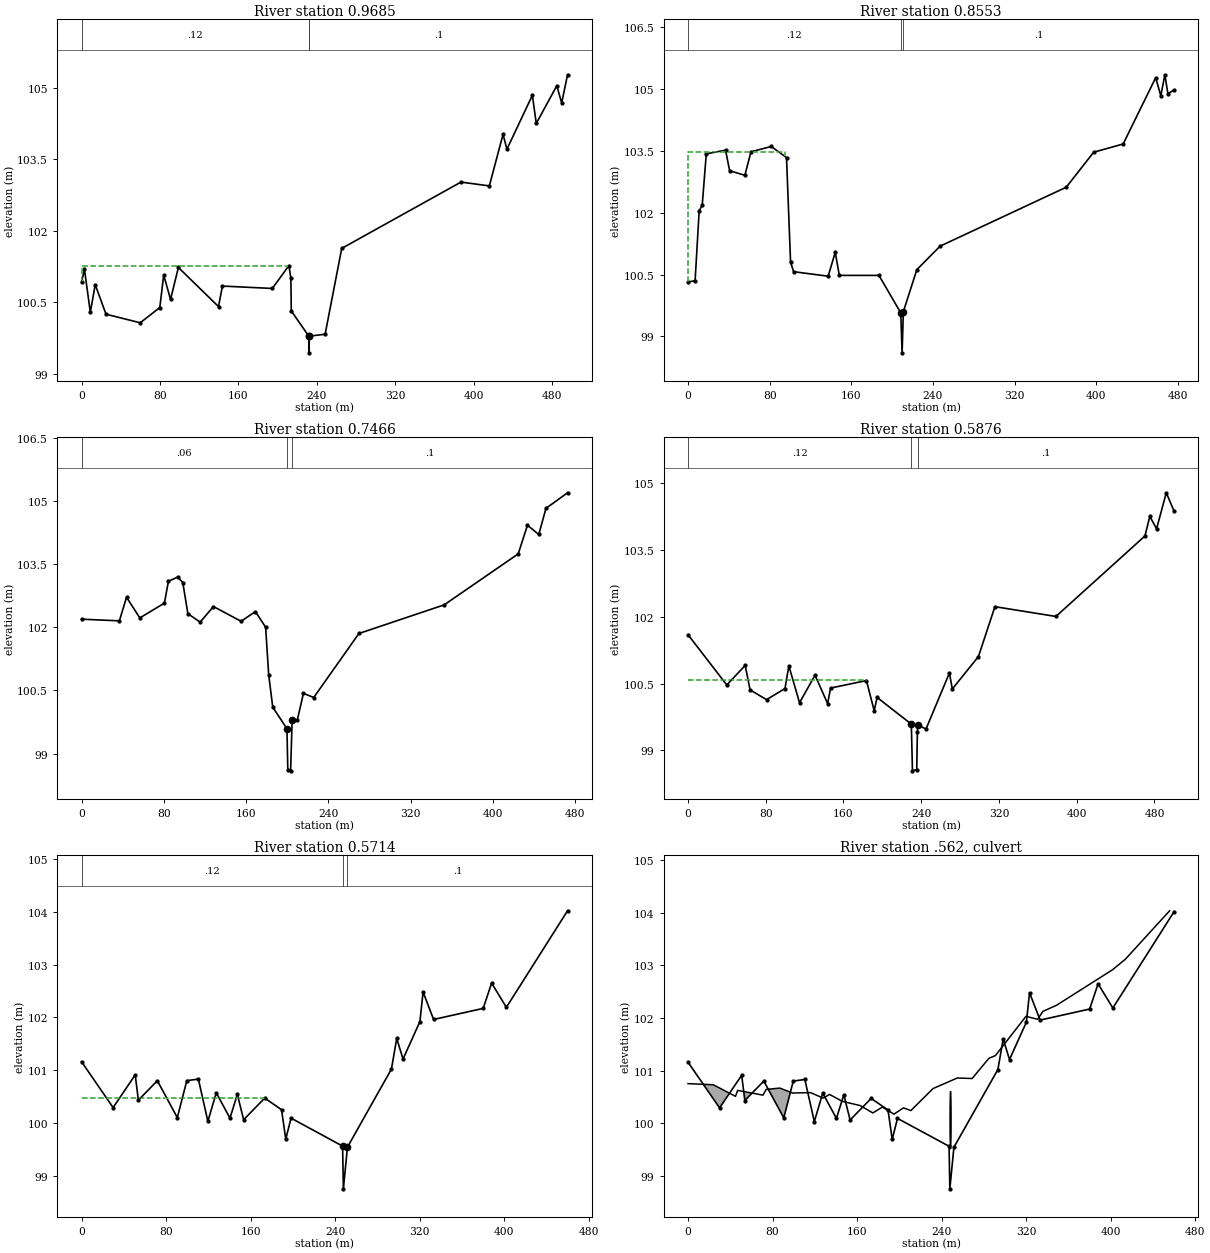
Type RM Length L Ch R = 1 ,0.9685  ,110.82,113.2,115.7
BEGIN DESCRIPTION:
B1_12 (SEM 2019)
END DESCRIPTION:
XS GIS Cut Line= 4
569806.0670035985426054.67378309569611.3333035995426088.54048309
569562.6498035985426103.35718309569336.1660035985426202.84078309
#Sta/Elev= 30
       0  100.92    2.99  101.19    8.98  100.29   13.98  100.87   24.96  100.25
    59.9  100.07   79.86  100.39   83.85  101.07   90.84  100.56   98.83  101.23
  139.76  100.41  143.75  100.84  194.66  100.79  211.63  101.27  213.62     101
  214.02  100.32  231.86   99.79  232.15   99.44  232.42   99.79  248.55   99.83
   265.5  101.63  387.19  103.02  416.12  102.94  430.08  104.02  434.07  103.71
  460.01  104.84     464  104.25  484.94  105.04  489.93  104.68  495.91  105.27
#Mann= 3 , 0 , 0
       0     .12       0  231.86     .04       0  232.42      .1       0
#XS Ineff= 2 , 0
          211.12  101.27
Permanent Ineff=
       F       F
Bank Sta=231.86,232.42
XS Rating Curve= 0 ,0
Exp/Cntr=0.3,0.1

Type RM Length L Ch R = 1 ,0.8553  ,108.76,108.71,106.89
BEGIN DESCRIPTION:
B1_11 (SEM 2019)
END DESCRIPTION:
XS GIS Cut Line= 4
569778.5503035985425950.95688309569590.1665035985425993.29028309
569554.1831035995425995.40698309569317.1160035985426065.25718309
#Sta/Elev= 30
       0  100.32    6.97  100.35   10.95  102.05   13.93  102.18   17.91  103.43
   36.82  103.52   40.81  103.02   55.73  102.91   61.71  103.48   81.61  103.61
   96.54  103.34  100.52   100.8  103.51  100.57  137.35  100.46  144.31  101.04
  148.29  100.48  187.11  100.48  208.52   99.57  209.81    98.6  211.05    99.6
  224.26  100.62  247.07  101.19  370.64  102.62  397.54  103.47  426.44  103.67
  458.33  105.28  463.32  104.84   467.3  105.35  470.29  104.89  476.27  104.98
#Mann= 3 , 0 , 0
       0     .12       0  208.52     .04       0  211.05      .1       0
#XS Ineff= 2 , 0
           94.94  103.47
Permanent Ineff=
       F       F
Bank Sta=208.52,211.05
XS Rating Curve= 0 ,0
Exp/Cntr=0.3,0.1

Type RM Length L Ch R = 1 ,0.7466  ,158.18,159.03,159.09
BEGIN DESCRIPTION:
B1_10 (SEM 2019)
END DESCRIPTION:
XS GIS Cut Line= 4
569746.8002035985425866.29008309569568.9998035985425887.45678309
569543.5998035995425895.92348309569295.9493035985425995.40698309
#Sta/Elev= 30
       0  102.19   36.81  102.15   43.77  102.71    56.7  102.22   80.58  102.57
   84.55  103.09   93.51  103.19   98.48  103.06  103.45  102.32  115.39  102.12
  128.32  102.49  155.18  102.14  169.11  102.37  179.06     102  182.03  100.87
     186   100.1  199.78   99.59  200.65    98.6  203.36   98.59  204.84   99.79
  209.83   99.79  215.83  100.43  225.82  100.33   269.8  101.85  352.77  102.53
  424.74  103.74  433.73  104.42  444.73   104.2  451.72  104.82  472.71  105.19
#Mann= 3 , 0 , 0
       0     .06       0  199.78     .04       0  204.84      .1       0
Bank Sta=199.78,204.84
XS Rating Curve= 0 ,0
Exp/Cntr=0.3,0.1

Type RM Length L Ch R = 1 ,0.5876  ,14.27,16.13,16.06
BEGIN DESCRIPTION:
B1_09 (SEM 2019)
END DESCRIPTION:
XS GIS Cut Line= 4
569740.4502035985425684.25638309569525.7333035985425742.68858309
569501.1270035985425749.56778309569295.9493035985425895.92348309
#Sta/Elev= 30
       0   101.6   39.91  100.47   58.87  100.91   63.86  100.36   80.83  100.14
   99.79  100.39  103.78   100.9  114.76  100.07  130.72  100.69  143.69  100.05
  146.69   100.4  183.61  100.57  191.59   99.89  194.59  100.19   229.8   99.59
  230.97   98.54  235.37   98.57  236.02   99.41  236.64   99.57  244.91   99.48
     269  100.74  271.98  100.38  298.88  101.11  315.81  102.23  378.57  102.01
  470.22  103.82   475.2  104.26  482.17  103.98  492.13  104.79   500.1  104.38
#Mann= 3 , 0 , 0
       0     .12       0   229.8     .04       0  236.64      .1       0
#XS Ineff= 2 , 0
          183.36  100.59
Permanent Ineff=
       F       F
Bank Sta=229.8,236.64
XS Rating Curve= 0 ,0
Exp/Cntr=0.3,0.1

Type RM Length L Ch R = 1 ,0.5714  ,13.95,15.68,15.85
BEGIN DESCRIPTION:
US of Stream B1 Newfoundland T'Railway Culvert - B1_08 (SEM 2019)
END DESCRIPTION:
XS GIS Cut Line= 4
569735.8641035995425673.60248309569508.3219035985425732.86928309
569488.2136035985425742.39428309569308.2965035985425835.52778309
#Sta/Elev= 30
       0  101.16   29.89  100.29   50.81  100.91    53.8  100.43   71.74   100.8
   90.67   100.1   99.63   100.8  110.59  100.83  119.56  100.03  127.53  100.57
  140.48  100.09  147.46  100.54  153.43  100.06  173.36  100.47   189.3  100.25
  193.29   99.69  198.27  100.09  247.08   99.56  247.83   98.75  251.66   99.54
  293.31  101.02   298.3   101.6  304.29  101.21  320.26  101.92  323.25  102.48
  333.23  101.96  380.14  102.17  388.12  102.65  402.09  102.19  459.98  104.02
#Mann= 3 , 0 , 0
       0     .12       0  247.08     .04       0  251.66      .1       0
#XS Ineff= 2 , 0
          173.31  100.47
Permanent Ineff=
       F       F
Bank Sta=247.08,251.66
XS Rating Curve= 0 ,0
Exp/Cntr=0.3,0.1

Type RM Length L Ch R = 2 ,.562    ,,,
Node Photo=.\Photos\B1-CR-1.JPG
BEGIN DESCRIPTION:
Stream B1 Newfoundland T'Railway Culvert
END DESCRIPTION:
Node Name=B1-CR-1
Bridge Culvert--1,0,-1,-1, 0
Deck Dist Width WeirC Skew NumUp NumDn MinLoCord MaxHiCord MaxSubmerge Is_Ogee
6.6,5.4,1.4,0, 30, 30, , , 0.98, 0, 3,3,,
       0 23.992244.9853746.9847370.9769373.9759586.9717398.96783115.9623127.9584
133.9565145.9526 162.947174.9431183.9402194.9366203.9337210.9314231.9246254.9171
268.9126284.9074290.9054 319.896330.8924335.8908348.8866401.8694413.8654455.8518
100.7511100.7298100.5091100.6225100.5324100.6414100.6665100.5725100.5802 100.476
100.5461100.4152 100.334100.1939 100.305100.1706  100.29100.2385100.6574100.8587
100.8484101.2356101.2838102.0318101.9747102.1255 102.243102.9184103.1165104.0392
       0 23.992244.9853746.9847370.9769373.9759586.9717398.96783115.9623127.9584
133.9565145.9526 162.947174.9431183.9402194.9366203.9337210.9314231.9246254.9171
268.9126284.9074290.9054 319.896330.8924335.8908348.8866401.8694413.8654455.8518
100.7511100.7298100.5091100.6225100.5324100.6414100.6665100.5725100.5802 100.476
100.5461100.4152 100.334100.1939 100.305100.1706  100.29100.2385100.6574100.8587
100.8484101.2356101.2838102.0318101.9747102.1255 102.243102.9184103.1165104.0392
BR Coef=-1 , 0 , 0 ,, 0 ,,,0.8,-1,,0,
WSPro=,,,, 1 ,,,, 0 ,,,, 0 ,,,,-1 ,-1 ,-1 , 0 , 0 , 0 , 0 , 0
Culvert=1,1.1,,9.2,0.024,0.9,1,2,3,99.505,248.5,99.373,253.5,Culvert #1  , 0 ,4
   248.5   253.5
BC Culvert Barrel=1,Barrel 1,0
Culvert Bottom n=0.024
BC Design=,, 0 ,, 0 ,,,,,,
BC Use User HTab Curves=0
BC User HTab FreeFlow(D)= 0