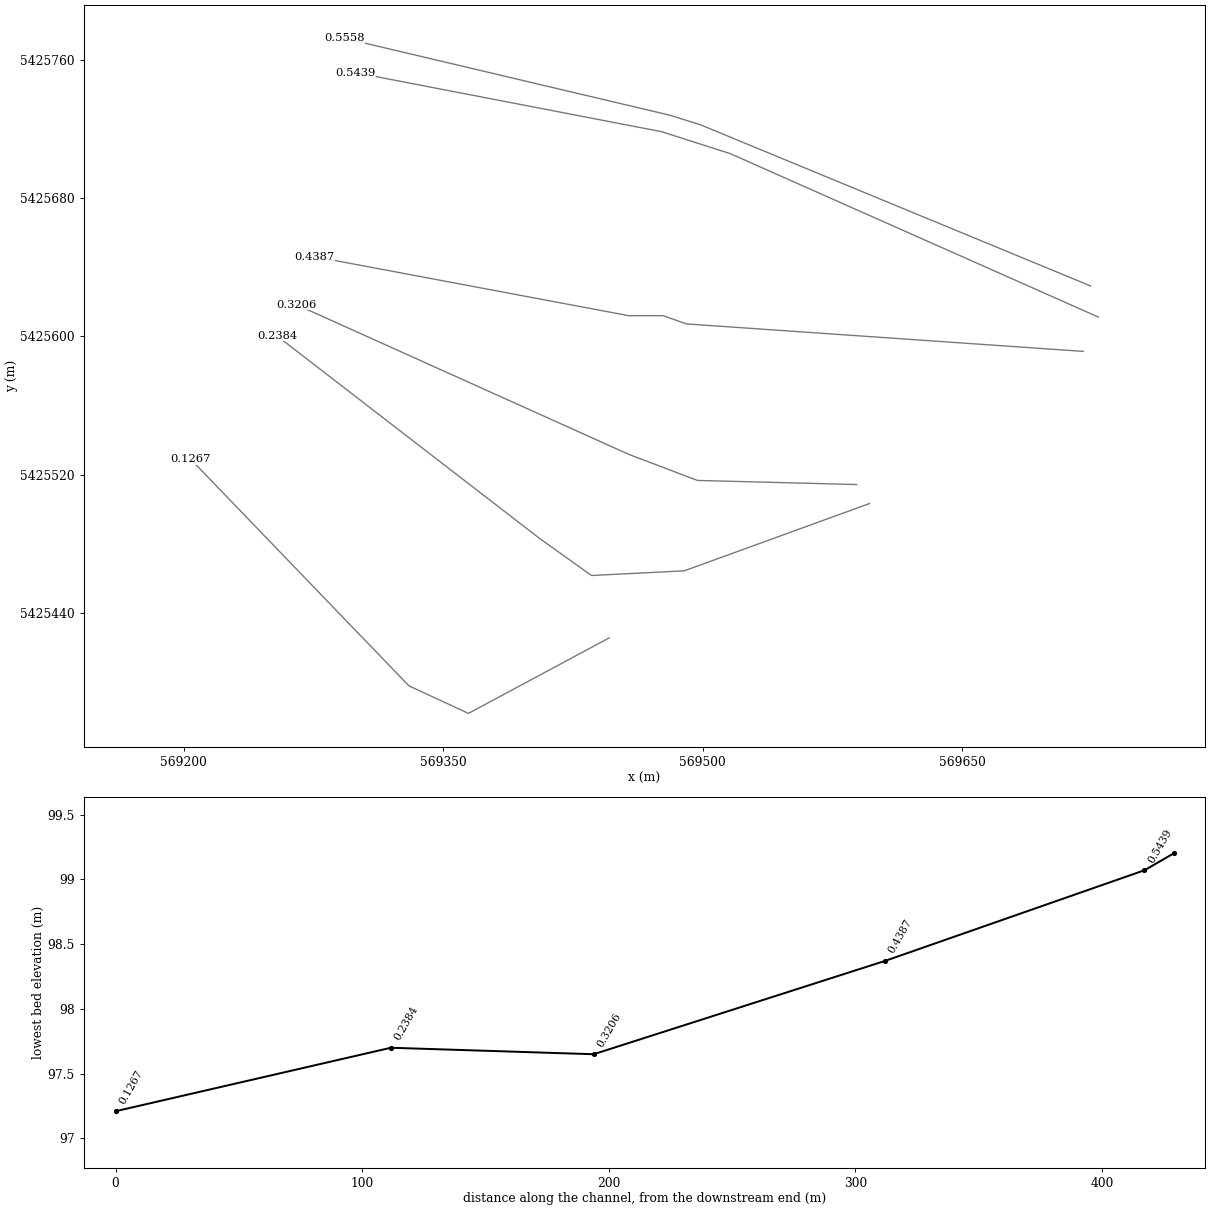
HEC-RAS study Exploits_FMM.prj: Exploits_FMM

--- Exploits_FMM.g01 (geometry) --- (continued)

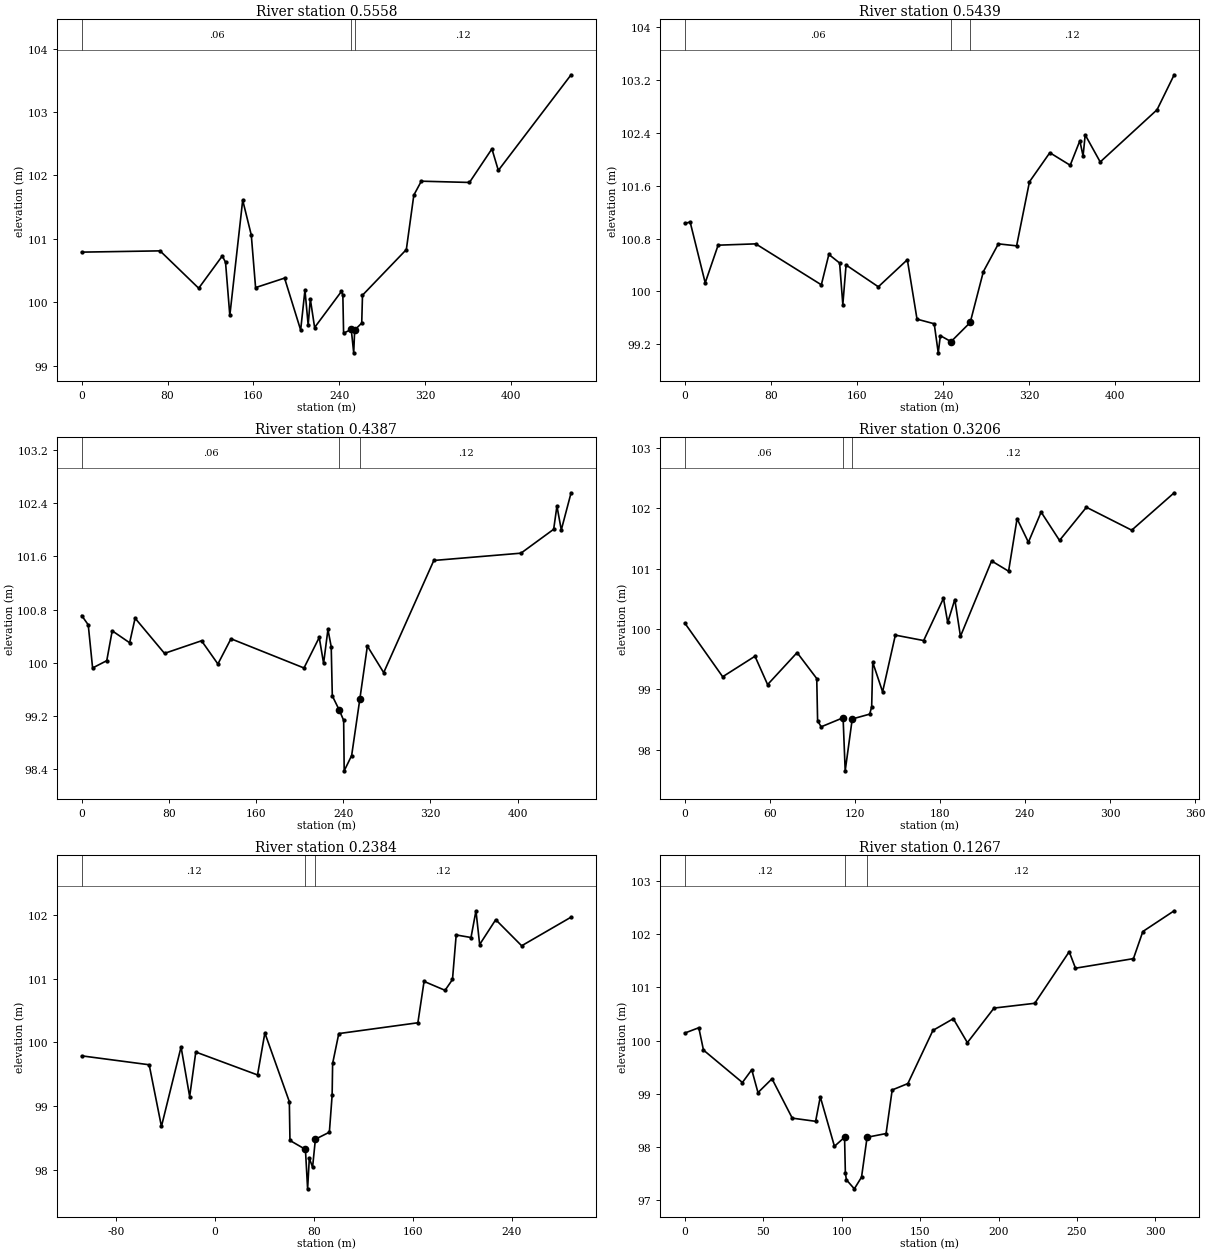
Type RM Length L Ch R = 1 ,0.5558  ,12.23,11.83,11.01
BEGIN DESCRIPTION:
DS of Stream B1 Newfoundland T'Railway Culvert - B1_07 (SEM 2019)
END DESCRIPTION:
XS GIS Cut Line= 4
569724.2224035985425629.15238309569498.7969035985425722.28588309
569481.0698035985425727.84218309569292.9507035995425772.29228309
#Sta/Elev= 30
       0  100.79   72.97  100.81  108.96  100.22  130.95  100.73  133.95  100.63
  137.95   99.79  149.94  101.61  157.94  101.06  161.94  100.23  188.93  100.38
  203.92   99.56  207.92  100.19  210.92   99.64  212.92  100.05  216.92    99.6
  241.91  100.17  243.22  100.11  243.91   99.51  251.04   99.57  253.33    99.2
  254.24   99.56   260.8   99.67  261.51  100.11  302.34  100.83  309.32  101.69
  316.29  101.91  361.13  101.89  382.05  102.42  388.03  102.08  455.79  103.59
#Mann= 3 , 0 , 0
       0     .06       0  251.04     .04       0  254.24     .12       0
Bank Sta=251.04,254.24
XS Rating Curve= 0 ,0
Exp/Cntr=0.3,0.1

Type RM Length L Ch R = 1 ,0.5439  ,105.26,105.24,107.52
BEGIN DESCRIPTION:
B1_06 (SEM 2019)
END DESCRIPTION:
XS GIS Cut Line= 4
569728.7203035985425611.16068309569515.9949035985425705.61708309
569476.3073035985425718.31718309569299.3007035985425752.44848309
#Sta/Elev= 30
       0  101.03    4.99  101.05   18.98  100.13   30.97   100.7   65.93  100.72
  126.87   100.1  133.86  100.56  143.85  100.43  146.84    99.8  149.84   100.4
  179.81  100.07  206.78  100.48  215.77   99.58  231.75   99.51  235.49   99.07
  237.45   99.33  247.39   99.24  265.19   99.53  277.41   100.3  291.35  100.72
  308.29  100.69  320.24  101.66  339.16   102.1  358.08  101.91  367.05  102.28
  370.04  102.05  372.03  102.37  385.97  101.96  438.76  102.75  454.69  103.28
#Mann= 3 , 0 , 0
       0     .06       0  247.39     .04       0  265.19     .12       0
Bank Sta=247.39,265.19
XS Rating Curve= 0 ,0
Exp/Cntr=0.3,0.1

Type RM Length L Ch R = 1 ,0.4387  ,116.06,118.09,109.74
BEGIN DESCRIPTION:
B1_05 (SEM 2019)
END DESCRIPTION:
XS GIS Cut Line= 5
569719.9890035995425591.31688309569490.5948035985425607.19188309
569477.1010035985425611.95438309569457.2573035985425611.95438309
569275.4881035985425646.08578309
#Sta/Elev= 30
       0  100.71       6  100.57      10   99.92   22.99  100.03   27.99  100.48
   43.99   100.3   48.99  100.67   75.98  100.14  109.97  100.33  124.97   99.98
  136.97  100.36  203.95   99.92  217.95  100.38  221.95   99.99  225.94   100.5
  228.94  100.24  229.94    99.5  236.49   99.28  240.36   99.13  240.84   98.37
  247.68    98.6  255.19   99.45  262.11  100.25  277.09   99.85  323.08  101.54
  403.06  101.65  433.05  102.01  436.05  102.36  440.04     102  449.04  102.56
#Mann= 3 , 0 , 0
       0     .06       0  236.49     .04       0  255.19     .12       0
Bank Sta=236.49,255.19
XS Rating Curve= 0 ,0
Exp/Cntr=0.3,0.1

Type RM Length L Ch R = 1 ,0.3206  ,81.57,82.22,75.36
BEGIN DESCRIPTION:
B1_04 (SEM 2019)
END DESCRIPTION:
XS GIS Cut Line= 4
569589.0200035985425514.32298309569496.9448035985425516.70428309
569457.2573035985425531.78548309569265.1694035995425618.30448309
#Sta/Elev= 30
       0   100.1   26.74   99.21   49.52   99.55   58.43   99.08   79.23   99.61
   93.09   99.18    93.7   98.48   96.22   98.38  111.68   98.53  113.16   97.65
  118.13   98.51  130.42   98.59  131.84   98.71  132.59   99.45  139.55   98.96
  148.54    99.9  168.51   99.81  182.49  100.51  185.48  100.11  190.48  100.49
  194.47   99.88  216.44  101.13  228.42  100.96  234.41  101.83   242.4  101.44
  251.38  101.94  264.36  101.47  283.33  102.02  315.28  101.64  345.24  102.26
#Mann= 3 , 0 , 0
       0     .06       0  111.68     .04       0  118.13     .12       0
Bank Sta=111.68,118.13
XS Rating Curve= 0 ,0
Exp/Cntr=0.3,0.1

Type RM Length L Ch R = 1 ,0.2384  ,109.3,111.64,115.08
BEGIN DESCRIPTION:
B1_03 (SEM 2019)
END DESCRIPTION:
XS GIS Cut Line= 5
  569596.4928036 5425503.3601831  569489.3380036 5425464.4324831
  569435.7267036 5425461.7369831  569405.6303036 5425483.2343831
  569253.8253036 5425600.3127831
#Sta/Elev= 30
 -107.51   99.79  -52.98   99.65  -43.07   98.68  -27.21   99.93  -20.27   99.15
  -15.31   99.85   34.58   99.49    40.5  100.15   60.28   99.07   60.79   98.46
   73.28   98.32   75.05    97.7   76.43   98.18   79.07   98.04   81.34   98.48
   92.63   98.59   94.86   99.17   95.26   99.67  100.25  100.14  164.16  100.31
  169.15  100.96  186.12  100.82  192.12  100.99  195.11  101.69  207.09  101.65
  211.09  102.07  214.08  101.54  227.06  101.93  248.03  101.52  287.97  101.97
#Mann= 3 , 0 , 0
 -107.51     .12       0   73.28     .04       0   81.34     .12       0
Bank Sta=73.28,81.34
XS Rating Curve= 0 ,0
Exp/Cntr=0.3,0.1

Type RM Length L Ch R = 1 ,0.1267  ,65.62,68.62,67.33
BEGIN DESCRIPTION:
B1_02 (SEM 2019)
END DESCRIPTION:
XS GIS Cut Line= 4
569445.9794035985425425.68738309569364.6198035985425382.03108309
569330.2239035985425397.90608309569204.1497035995425528.80898309
#Sta/Elev= 30
       0  100.14    8.94  100.24   11.91   99.82   36.73   99.21   42.69   99.45
   46.66   99.02    55.6   99.28    68.5   98.54    83.4   98.48   86.38   98.94
    95.4   98.01  101.85   98.18  102.36   97.51  103.01   97.38  108.08   97.21
  112.67   97.43  116.21   98.18  128.31   98.25  132.21   99.07   142.2   99.19
  158.18  100.19  171.16  100.41  180.14   99.96  197.12  100.61  223.08   100.7
  245.05  101.67  249.05  101.36  285.99  101.54  291.99  102.05  311.96  102.44
#Mann= 3 , 0 , 0
       0     .12       0  101.85     .04       0  116.21     .12       0
Bank Sta=101.85,116.21
XS Rating Curve= 0 ,0
Exp/Cntr=0.3,0.1