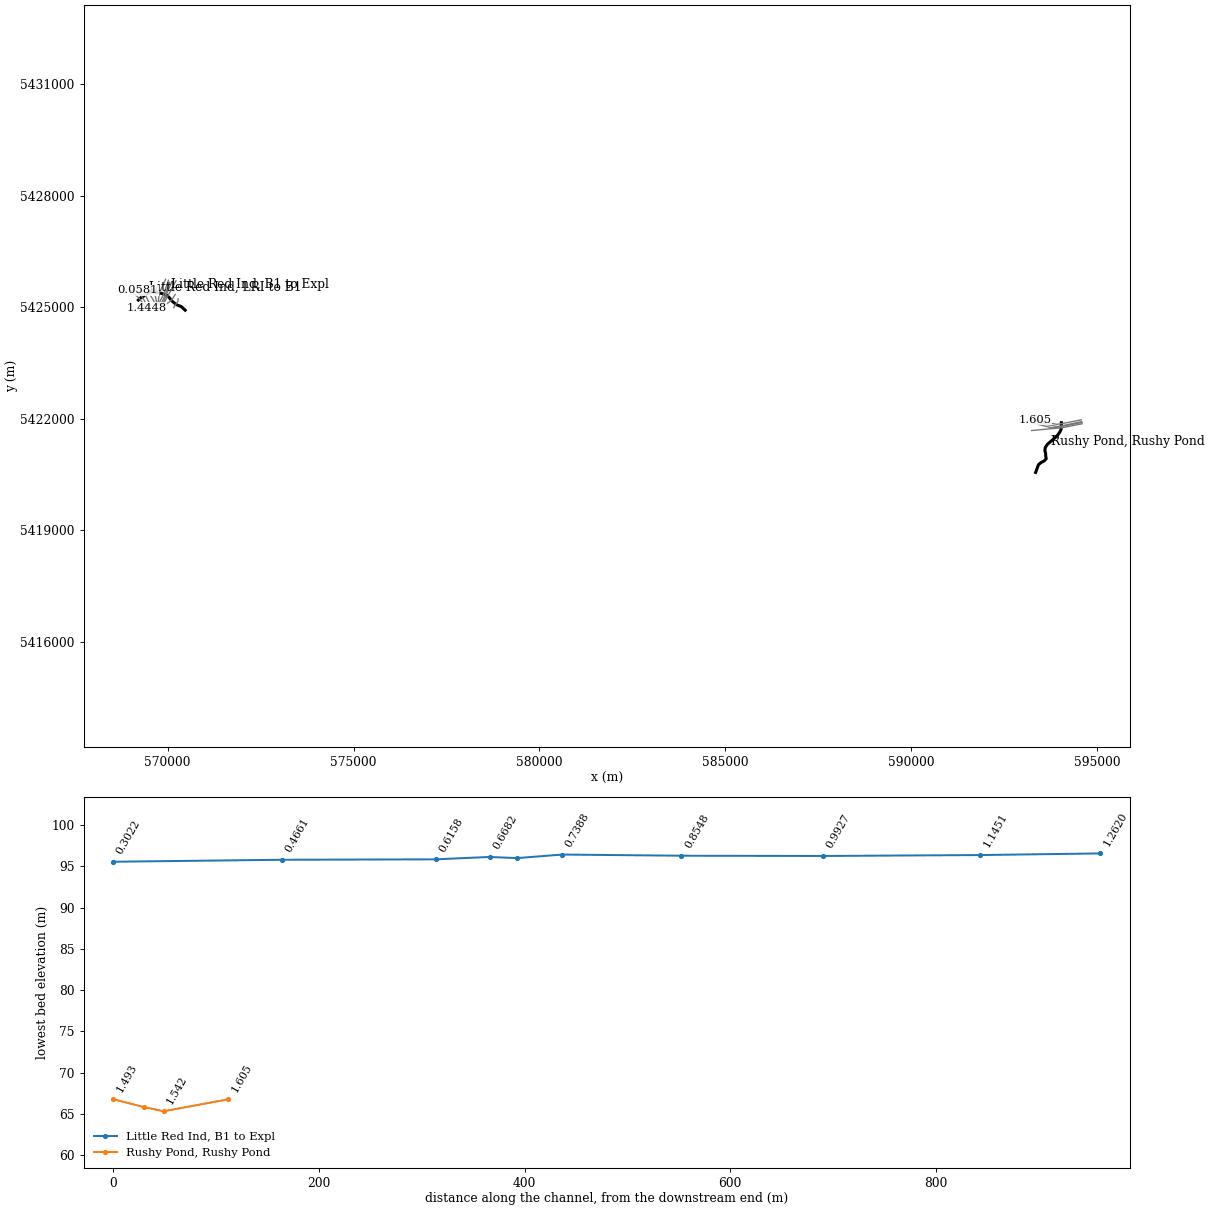
HEC-RAS study Exploits_FMM.prj: Exploits_FMM

--- Exploits_FMM.g01 (geometry) --- (continued)

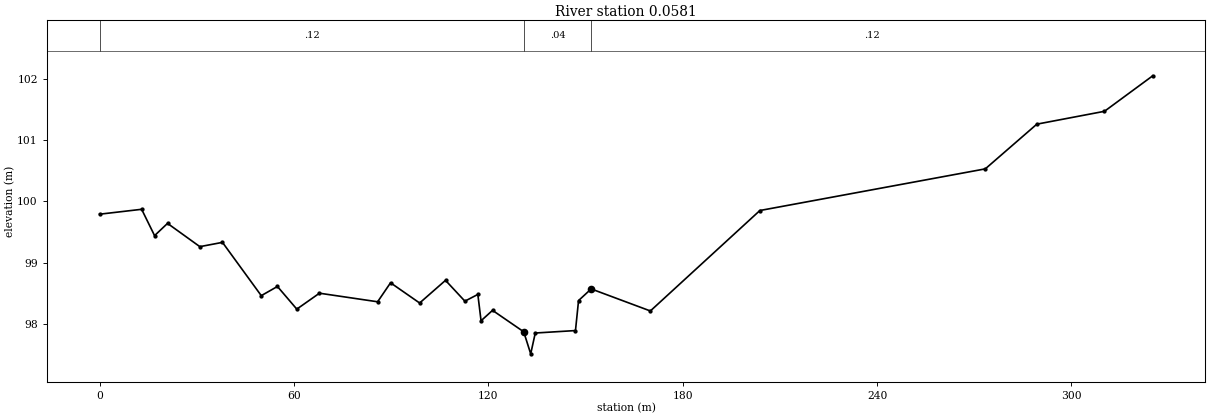
Type RM Length L Ch R = 1 ,0.0581  ,30.83,58.11,34.56
BEGIN DESCRIPTION:
B1_01 (SEM 2019)
END DESCRIPTION:
XS GIS Cut Line= 5
569435.9252035985425407.62958309569347.2896035985425330.10648309
569318.4499035985425334.33978309569308.1312035985425346.77528309
569196.2122035995425463.98588309
#Sta/Elev= 30
       0   99.79   12.97   99.87   16.96   99.44   20.96   99.64   30.94   99.26
   37.92   99.33    49.9   98.46   54.89   98.61   60.87   98.24   67.86    98.5
   85.82   98.36   89.81   98.67   98.79   98.34  106.78   98.71  112.76   98.37
  116.76   98.48  117.75   98.05   121.3   98.22  130.92   97.87  133.08   97.51
  134.49   97.85   146.9   97.89  147.85   98.38  151.75   98.57  170.02   98.21
  203.83   99.85  273.42  100.53  289.33  101.26  310.21  101.47  325.12  102.05
#Mann= 3 , 0 , 0
       0     .12       0  130.92     .04       0  151.75     .12       0
Bank Sta=130.92,151.75
XS Rating Curve= 0 ,0
Exp/Cntr=0.3,0.1

River Reach=Little Red Ind  ,LRI to B1
Reach XY= 4
     569212.6543    5425198.1977     569270.4736    5425252.8639
      569324.013    5425285.3142 569323.882464585425285.23069908

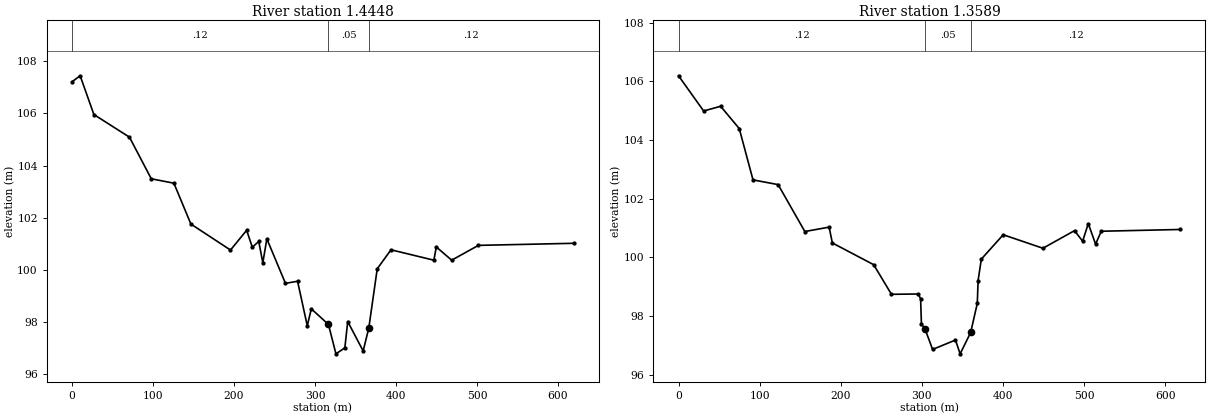
Type RM Length L Ch R = 1 ,1.4448  ,99.23,85.87,92.89
BEGIN DESCRIPTION:
LR12 (SEM 2019)
END DESCRIPTION:
XS GIS Cut Line= 4
569020.3638035985425461.27518309569241.2940035985425234.82298309
569272.8290035995425189.21998309569424.9241035985424993.59988309
#Sta/Elev= 30
       0  107.22    9.98  107.45   26.95  105.96   70.86  105.09   97.81  103.49
  125.75  103.32  146.71  101.75  195.61  100.75  215.57  101.51  222.56  100.86
  230.54  101.08  235.53  100.26  240.52  101.18  263.48   99.47  278.45   99.55
  290.42   97.84  295.41   98.49  316.57   97.89  325.82   96.76  336.81   96.99
  340.38      98  359.44   96.87  366.44   97.76  376.81  100.03   393.8  100.76
  446.75  100.36  449.75  100.87  468.73  100.36  501.71  100.93   619.6  101.01
#Mann= 3 , 0 , 0
       0     .12       0  316.57     .05       0  366.44     .12       0
Bank Sta=316.57,366.44
XS Rating Curve= 0 ,0
Exp/Cntr=0.3,0.1

Type RM Length L Ch R = 1 ,1.3589  ,98.29,96.97,97.34
BEGIN DESCRIPTION:
LR11 (SEM 2019)
END DESCRIPTION:
XS GIS Cut Line= 5
569063.3850035985425486.94048309569299.6660035985425302.87898309
569336.0600035985425244.38098309569461.8483035985425029.73958309
569461.8483035985425028.15208309
#Sta/Elev= 30
       0  106.19   30.95  104.99   51.92  105.15   74.88  104.39   91.85  102.64
   122.8  102.48  155.75  100.88   185.7  101.03  189.69  100.49  240.61   99.75
  262.57   98.74  295.52   98.75  298.51   98.59  299.51   97.73  304.08   97.55
  313.28   96.86  341.48   97.18  347.27   96.71  360.25   97.44  368.41   98.43
  369.41   99.21   373.4   99.94  400.38  100.77  449.34  100.31   488.3  100.91
   498.3  100.55  505.29  101.15  514.28  100.45  521.28  100.89  618.78  100.95
#Mann= 3 , 0 , 0
       0     .12       0  304.08     .05       0  360.25     .12       0
Bank Sta=304.08,360.25
XS Rating Curve= 0 ,0
Exp/Cntr=0.3,0.1

River Reach=Little Red Ind  ,B1 to Expl
Reach XY= 13
 569323.882464585425285.23069908     569451.4928    5425367.9431
     569524.0134     5425405.405     569606.3902    5425417.6007
     569724.1196    5425396.9294     569821.1555    5425380.7475
     569918.3586    5425351.8695      569986.996    5425322.6155
     570040.9625    5425264.2393     570117.7482    5425170.5547
     570234.8874    5425075.3554     570369.6267    5425019.6983
     570472.2323    5424925.2875

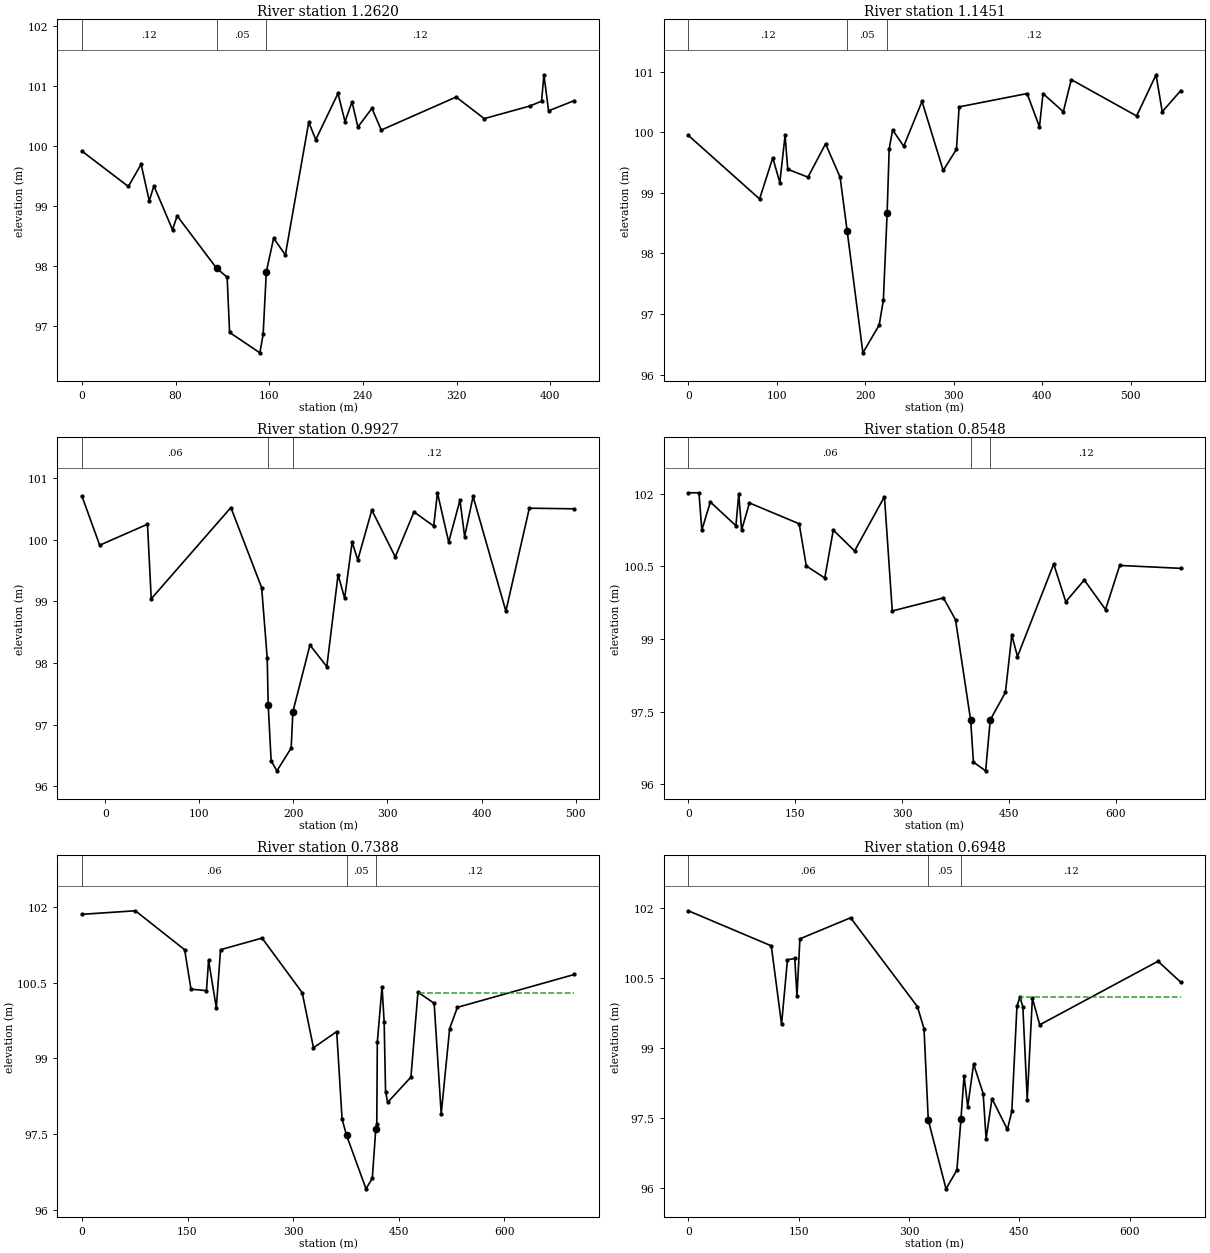
Type RM Length L Ch R = 1 ,1.2620  ,117.98,116.87,117.04
BEGIN DESCRIPTION:
LR10 (SEM 2019)
END DESCRIPTION:
XS GIS Cut Line= 4
  569464.9452036 5425426.2131831  569389.2260036 5425342.1239831
  569417.1370036 5425298.6789831  569530.1535036 5425069.2147831
#Sta/Elev= 30
       0   99.92    39.7   99.33   50.62    99.7   57.57   99.09   61.54   99.34
   77.42   98.61   81.39   98.84  115.02   97.97  124.08   97.82  126.16    96.9
  152.03   96.56  154.83   96.87  157.54   97.91   163.8   98.47  173.79   98.19
  193.77   100.4  199.77  100.11  218.75  100.88  224.74  100.41  230.74  100.74
  235.73  100.32  247.72  100.63  255.72  100.27  319.66  100.82  343.64  100.46
  382.61  100.67   392.6  100.75   394.6  101.19   398.6  100.59  420.58  100.76
#Mann= 3 , 0 , 0
       0     .12       0  115.02     .05       0  157.54     .12       0
Bank Sta=115.02,157.54
XS Rating Curve= 0 ,0
Exp/Cntr=0.3,0.1

Type RM Length L Ch R = 1 ,1.1451  ,156.91,152.39,143.71
BEGIN DESCRIPTION:
LR09 (SEM 2019)
END DESCRIPTION:
XS GIS Cut Line= 6
  569610.9955036 5425505.5883831  569478.7487036 5425418.8289831
  569491.9420036 5425399.9119831  569512.6705036 5425358.9479831
  569528.1155036 5425337.8854831  569686.1938036 5425078.6942831
#Sta/Elev= 30
       0   99.95   80.58    98.9    95.5   99.58  103.45   99.17  109.42   99.95
  112.41   99.39  135.29   99.26  155.18   99.81  171.62   99.26  179.62   98.37
   197.4   96.36  215.85   96.82  220.53   97.23  224.81   98.67  227.14   99.73
  231.01  100.04  243.58   99.77  264.24  100.51  288.21   99.37  303.19   99.72
  306.19  100.42  383.08  100.64  397.06  100.09  401.06  100.64  424.03  100.34
  433.02  100.87  506.92  100.27  528.89  100.95  535.88  100.34  556.85  100.69
#Mann= 3 , 0 , 0
       0     .12       0  179.62     .05       0  224.81     .12       0
Bank Sta=179.62,224.81
XS Rating Curve= 0 ,0
Exp/Cntr=0.3,0.1

Type RM Length L Ch R = 1 ,0.9927  ,141.85,137.93,136.59
BEGIN DESCRIPTION:
LR08 (SEM 2019)
END DESCRIPTION:
XS GIS Cut Line= 6
  569736.6952036 5425594.0303831  569730.4430036 5425583.7878831
  569643.2299036 5425440.9133831  569644.1570036 5425392.7119831
  569715.5080036 5425105.3598831  569715.6743036 5425104.6901831
#Sta/Elev= 30
     -25  100.71   -6.03   99.91   44.79  100.25   48.77   99.04  133.47  100.52
   166.2   99.22   172.1   98.08  173.17   97.31   176.3   96.41  182.47   96.25
  197.58   96.62  199.41   97.21  217.55   98.29   235.5   97.94  247.46   99.43
  254.44   99.05  262.41   99.96   268.4   99.67  283.35  100.48  308.27   99.72
  328.21  100.45  349.14  100.22  353.13  100.76  365.09   99.96  377.06  100.64
  382.04  100.05  391.01   100.7   425.9   98.84  450.83  100.51  498.68   100.5
#Mann= 3 , 0 , 0
     -25     .06       0  173.17     .05       0  199.41     .12       0
Bank Sta=173.17,199.41
XS Rating Curve= 0 ,0
Exp/Cntr=0.3,0.1

Type RM Length L Ch R = 1 ,0.8548  ,117.08,115.94,115.7
BEGIN DESCRIPTION:
LR07 (SEM 2019)
END DESCRIPTION:
XS GIS Cut Line= 4
  569946.6459036 5425756.4258831  569783.7270036 5425401.9979831
  569773.5770036 5425365.2119831  569740.9207036 5425104.1072831
#Sta/Elev= 30
       0  102.02   14.96  102.02   18.96  101.25   30.93  101.83   66.84  101.34
   70.83     102   74.82  101.25    85.8  101.81  155.63  101.38  165.61  100.51
  191.55  100.26  203.52  101.25  233.45  100.82  275.35  101.94  286.32   99.58
  358.15   99.85  375.11    99.4  396.41   97.32  400.25   96.46  417.42   96.28
  423.84   97.33  445.18    97.9  454.15   99.08  462.13   98.64  512.96  100.55
  529.91   99.77  555.82  100.22  585.72   99.61  605.66  100.52  691.38  100.46
#Mann= 3 , 0 , 0
       0     .06       0  396.41     .05       0  423.84     .12       0
Bank Sta=396.41,423.84
XS Rating Curve= 0 ,0
Exp/Cntr=0.3,0.1

Type RM Length L Ch R = 1 ,0.7388  ,43.98,44.07,46.06
BEGIN DESCRIPTION:
LR06 (SEM 2019)
END DESCRIPTION:
XS GIS Cut Line= 5
  570023.1255036 5425731.6166831  569899.9390036 5425381.8449831
  569884.5520036 5425338.5139831  569883.3601036 5425333.2495831
  569753.8255036 5425088.4046831
#Sta/Elev= 30
       0  101.85   75.97  101.92  145.93  101.15  154.93  100.37  176.92  100.34
  179.92  100.94  190.91     100  196.91  101.15  255.88  101.38  312.86   100.3
  328.85   99.21  361.83   99.53  369.46    97.8  375.77   97.48  403.45   96.42
  412.41   96.63  417.33   97.61  418.72    97.7  419.51   99.32  426.21  100.42
  429.21   99.72  431.21   98.34  434.21   98.13  467.21   98.63  477.21  100.31
  500.21  100.09  510.21    97.9  522.21   99.59  533.21  100.01  699.21  100.66
#Mann= 3 , 0 , 0
       0     .06       0  375.77     .05       0  417.33     .12       0
#XS Ineff= 2 , 0
                          479.26           100.3
Permanent Ineff=
       F       F
Bank Sta=375.77,417.33
XS Rating Curve= 0 ,0
Exp/Cntr=0.3,0.1

Type RM Length L Ch R = 1 ,0.6948  ,27.23,26.59,25.31
BEGIN DESCRIPTION:
US of Buchans Hwy Bridge - LR05 (SEM 2019)
END DESCRIPTION:
XS GIS Cut Line= 5
  570055.4848036 5425672.7305831  569941.5670036 5425366.9399831
  569935.8840036 5425354.5409831  569928.1980036 5425322.6279831
  569809.5743036 5425050.8041831
#Sta/Elev= 30
       0  101.94  112.77  101.19  126.74   99.51  134.72  100.89   144.7  100.92
  147.69  100.11  151.68  101.34  220.54  101.79  311.35   99.89  320.33   99.42
  326.16   97.46  350.27   95.99  365.02   96.39  370.56   97.48  374.78   98.41
  379.78   97.75  387.76   98.66  400.75   98.03  404.74   97.06  412.73   97.92
   433.7   97.26  439.69   97.65  446.68    99.9  450.68  100.09  454.67   99.89
  460.66    97.9  467.65  100.07  477.64    99.5  638.41  100.86  669.37  100.41
#Mann= 3 , 0 , 0
       0     .06       0  326.16     .05       0  370.56     .12       0
#XS Ineff= 2 , 0
                          451.91          100.09
Permanent Ineff=
       F       F
Bank Sta=326.16,370.56
XS Rating Curve= 0 ,0
Exp/Cntr=0.3,0.1

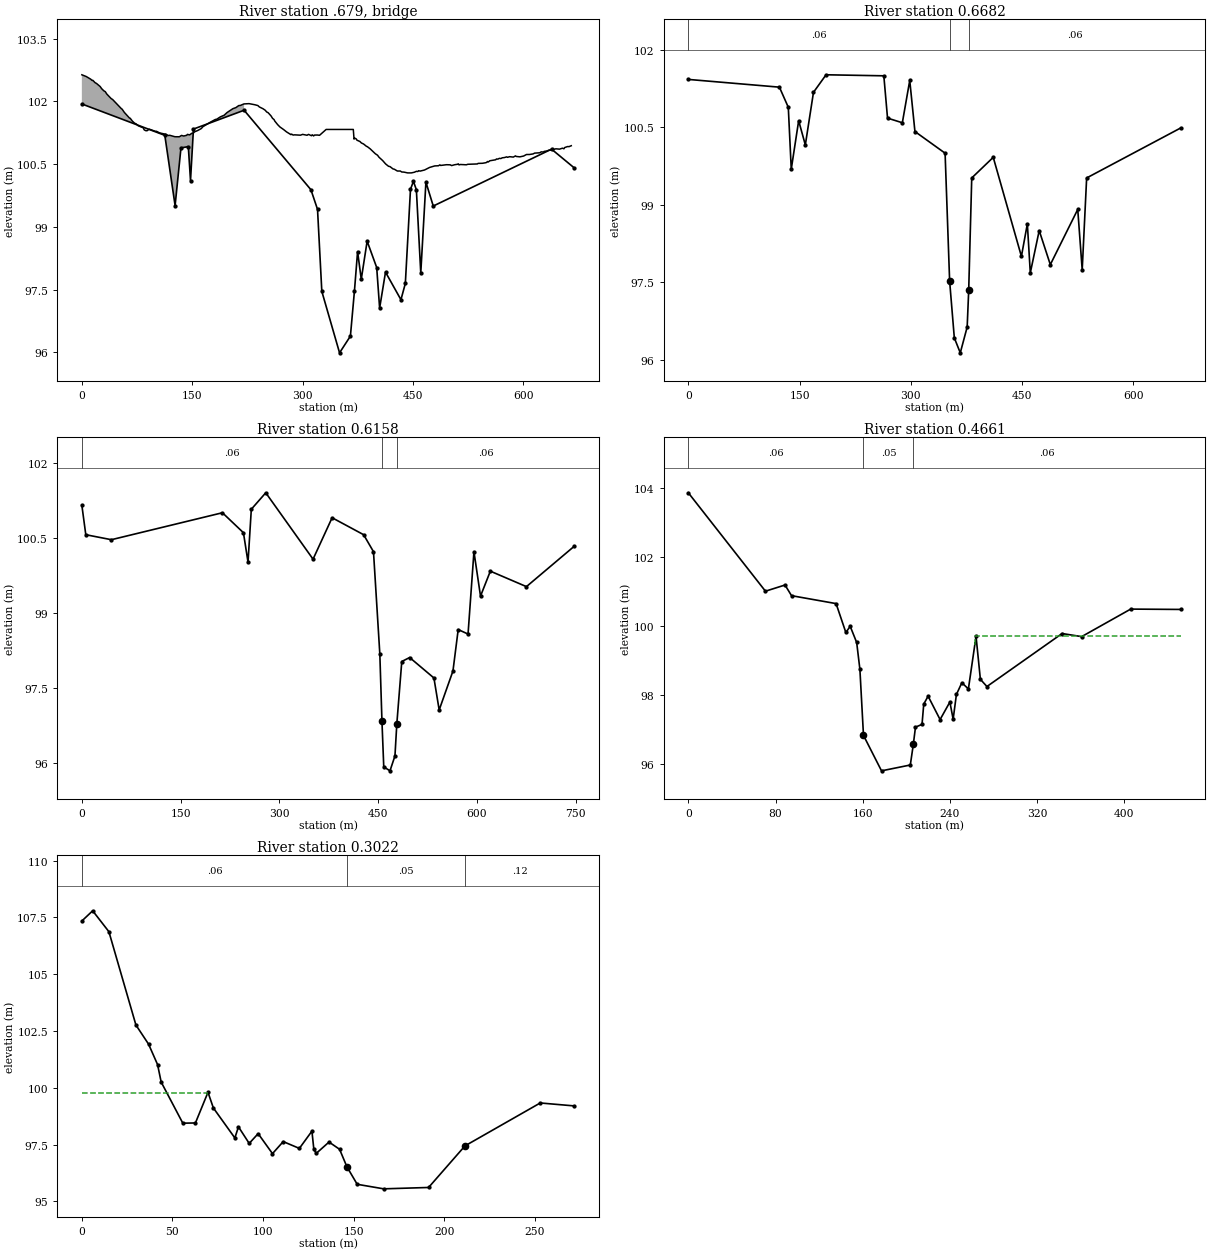
Type RM Length L Ch R = 3 ,.679    ,,,
Node Photo=.\Photos\LRI-CR-1.jpg
BEGIN DESCRIPTION:
Route 370 Buchans Hwy Bridge
END DESCRIPTION:
Node Name=LRI-CR-1
Bridge Culvert--1,0,-1,-1, 0
Deck Dist Width WeirC Skew NumUp NumDn MinLoCord MaxHiCord MaxSubmerge Is_Ogee
5,8.8,1.4,0, 200, 200, , , 0.98, 0, 3,3,,
       0   5.972  11.944  13.935  14.931  17.917  19.907  24.884  26.875  29.861
  31.852  33.843  39.815  41.806   53.75  54.746  57.732  64.699  65.695  68.681
  71.667  73.658  76.644  83.611  84.607  86.597  88.591  91.584  99.566 101.561
 105.552 113.534 117.525  119.52 126.504 132.491 135.484 138.477 142.468 143.466
 146.459 149.452 151.448 153.443 157.434 162.423 164.418 174.396  181.38 183.375
 188.364 193.353 197.344 205.325 209.316 213.307 215.303 220.291 227.276 235.257
 239.248 241.244 246.232 249.226 251.221 253.217 257.207 259.203 261.198 262.196
 266.187  269.18 274.169  278.16 284.146 285.144 287.139 289.135 297.117  300.11
 306.096 308.092 312.083 313.081 315.076 316.074 320.065 323.058 332.037 333.035
 334.033 336.028 337.026 338.024 339.022 341.017 342.015 343.013  344.01 345.008
 346.006 347.003 349.997 354.985 355.983 359.974 360.972 361.969 362.967 363.965
 364.963  365.96 368.954 369.951 370.949 372.945 373.942 377.933 379.929 382.922
 386.913 387.911 391.901 398.886 401.879 403.874 408.863 412.854 416.845  418.84
 422.831 424.827 428.818 432.808 434.804 437.796 442.784 447.771 451.761 454.753
 456.748 457.746 459.741 465.726 472.708  479.69 484.678 486.673  487.67  495.65
 500.638 502.633 506.623 510.613  511.61 512.607 514.602 522.582 524.577 537.545
 538.542 544.527 549.514 551.509 552.507 554.502 562.482 563.479 565.474 567.469
 569.464 571.459 574.452 577.444 578.441 581.434 586.421 589.414 590.411 595.399
 600.386 604.376 608.366 613.353 615.348 622.331 624.326 627.318 628.316 632.306
 634.301 638.291 644.275 649.263 653.253 655.248 656.245 660.235  662.23 665.223
 102.638 102.596 102.534 102.502 102.506  102.45 102.431 102.357 102.307 102.255
 102.234 102.179 102.069 102.047 101.827 101.816 101.739 101.604 101.599  101.53
 101.481 101.465 101.419 101.368 101.324 101.303   101.3 101.338 101.288 101.286
 101.249 101.217 101.186 101.191 101.157 101.156 101.188 101.174 101.191 101.213
 101.201 101.239 101.245 101.276 101.305 101.353 101.395 101.502 101.569 101.576
 101.633  101.67 101.735 101.828 101.853 101.902 101.904 101.941 101.948 101.921
 101.902 101.869 101.826  101.79 101.749 101.731 101.653 101.596 101.568 101.532
 101.445 101.391 101.329 101.273 101.207 101.219 101.197 101.202 101.194 101.213
 101.192 101.213 101.181 101.203 101.176 101.196 101.198 101.191 101.331 101.331
 101.331 101.331 101.331 101.331 101.331 101.331 101.331 101.331 101.331 101.331
 101.331 101.331 101.331 101.331 101.331 101.331 101.331 101.331 101.331 101.331
 101.331 101.331 101.331   101.1 101.123 101.104 101.074 101.043 101.008 100.983
 100.926 100.921 100.867  100.75 100.715 100.667 100.587 100.507  100.45 100.443
 100.388 100.379 100.337 100.337 100.314 100.311 100.292 100.292 100.307  100.33
 100.325 100.344 100.335 100.361 100.423 100.459 100.463 100.484  100.47 100.488
 100.485 100.467 100.487 100.498 100.509 100.484 100.493 100.486 100.498 100.506
 100.519 100.522 100.537 100.564 100.554 100.582 100.606 100.625 100.622  100.64
 100.635 100.653 100.659 100.676 100.664  100.68  100.67 100.699 100.685 100.676
 100.695 100.732 100.732 100.746 100.765 100.773 100.795 100.791 100.806 100.817
 100.833 100.837 100.868  100.86 100.883 100.869 100.898 100.922  100.92 100.942
                                          99.511  99.511  99.511  99.511  99.511
  99.511  99.511  99.511  99.511  99.511  99.511  99.511  99.511  99.511  99.511
  99.511  99.511  99.511
      10  15.972  21.944  23.935  24.931  27.917  29.907  34.884  36.875  39.861
  41.852  43.843  49.815  51.806   63.75  64.746  67.732  74.699  75.695  78.681
  81.667  83.658  86.644  93.611  94.607  96.597  98.591 101.584 109.566 111.561
 115.552 123.534 127.525  129.52 136.504 142.491 145.484 148.477 152.468 153.466
 156.459 159.452 161.448 163.443 167.434 172.423 174.418 184.396  191.38 193.375
 198.364 203.353 207.344 215.325 219.316 223.307 225.303 230.291 237.276 245.257
 249.248 251.244 256.232 259.226 261.221 263.217 267.207 269.203 271.198 272.196
 276.187  279.18 284.169  288.16 294.146 295.144 297.139 299.135 307.117  310.11
 316.096 318.092 322.083 323.081 325.076 326.074 330.065 333.058 342.037 343.035
 344.033 346.028 347.026 348.024 349.022 351.017 352.015 353.013  354.01 355.008
 356.006 357.003 359.997 364.985 365.983 369.974 370.972 371.969 372.967 373.965
 374.963  375.96 378.954 379.951 380.949 382.945 383.942 387.933 389.929 392.922
 396.913 397.911 401.901 408.886 411.879 413.874 418.863 422.854 426.845  428.84
 432.831 434.827 438.818 442.808 444.804 447.796 452.784 457.771 461.761 464.753
 466.748 467.746 469.741 475.726 482.708  489.69 494.678 496.673  497.67  505.65
 510.638 512.633 516.623 520.613  521.61 522.607 524.602 532.582 534.577 547.545
 548.542 554.527 559.514 561.509 562.507 564.502 572.482 573.479 575.474 577.469
 579.464 581.459 584.452 587.444 588.441 591.434 596.421 599.414 600.411 605.399
 610.386 614.376 618.366 623.353 625.348 632.331 634.326 637.318 638.316 642.306
 644.301 648.291 654.275 659.263 663.253 665.248 666.245 670.235  672.23 675.223
 102.638 102.596 102.534 102.502 102.506  102.45 102.431 102.357 102.307 102.255
 102.234 102.179 102.069 102.047 101.827 101.816 101.739 101.604 101.599  101.53
 101.481 101.465 101.419 101.368 101.324 101.303   101.3 101.338 101.288 101.286
 101.249 101.217 101.186 101.191 101.157 101.156 101.188 101.174 101.191 101.213
 101.201 101.239 101.245 101.276 101.305 101.353 101.395 101.502 101.569 101.576
 101.633  101.67 101.735 101.828 101.853 101.902 101.904 101.941 101.948 101.921
 101.902 101.869 101.826  101.79 101.749 101.731 101.653 101.596 101.568 101.532
 101.445 101.391 101.329 101.273 101.207 101.219 101.197 101.202 101.194 101.213
 101.192 101.213 101.181 101.203 101.176 101.196 101.198 101.191 101.331 101.331
 101.331 101.331 101.331 101.331 101.331 101.331 101.331 101.331 101.331 101.331
 101.331 101.331 101.331 101.331 101.331 101.331 101.331 101.331 101.331 101.331
 101.331 101.331 101.331   101.1 101.123 101.104 101.074 101.043 101.008 100.983
 100.926 100.921 100.867  100.75 100.715 100.667 100.587 100.507  100.45 100.443
 100.388 100.379 100.337 100.337 100.314 100.311 100.292 100.292 100.307  100.33
 100.325 100.344 100.335 100.361 100.423 100.459 100.463 100.484  100.47 100.488
 100.485 100.467 100.487 100.498 100.509 100.484 100.493 100.486 100.498 100.506
 100.519 100.522 100.537 100.564 100.554 100.582 100.606 100.625 100.622  100.64
 100.635 100.653 100.659 100.676 100.664  100.68  100.67 100.699 100.685 100.676
 100.695 100.732 100.732 100.746 100.765 100.773 100.795 100.791 100.806 100.817
 100.833 100.837 100.868  100.86 100.883 100.869 100.898 100.922  100.92 100.942
                                          99.511  99.511  99.511  99.511  99.511
  99.511  99.511  99.511  99.511  99.511  99.511  99.511  99.511  99.511  99.511
  99.511  99.511  99.511
BR Coef=-1 , 0 , 0 ,, 0 ,,,0.8,-1,,0,
WSPro=,,,, 1 ,,,, 0 ,,,, 0 ,,,,-1 ,-1 ,-1 , 0 , 0 , 0 , 0 , 0
BC Design=,, 0 ,, 0 ,,,,,,
BC HTab HWMax=104
BC Use User HTab Curves=0
BC User HTab FreeFlow(D)= 0

Type RM Length L Ch R = 1 ,0.6682  ,55.35,52.41,48.81
BEGIN DESCRIPTION:
DS of Buchans Hwy Bridge - LR04 (SEM 2019)
END DESCRIPTION:
XS GIS Cut Line= 4
  570104.6974036 5425666.3805831  569965.1030036 5425355.8259831
  569950.6520036 5425312.5279831  569860.3744036 5425049.7457831
#Sta/Elev= 30
       0  101.43  122.81  101.28   134.8  100.89  138.79   99.69  148.78  100.63
  157.76  100.16  168.75  101.18  185.72  101.52   263.6   101.5  268.59  100.68
  288.56  100.59  298.55  101.41  305.54  100.42  346.21     100  352.32   97.52
  358.64   96.42  366.68   96.13  375.97   96.63  378.03   97.34  382.13   99.52
  411.12   99.92   449.1      98   457.1   98.63  461.09   97.68  473.09    98.5
  488.08   97.84  525.06   98.91  531.06   97.74  537.05   99.52  663.99  100.49
#Mann= 3 , 0 , 0
       0     .06       0  352.32     .05       0  378.03     .06       0
#XS Ineff= 2 , 0
                          410.23            99.9
Permanent Ineff=
       F       F
Bank Sta=352.32,378.03
XS Rating Curve= 0 ,0
Exp/Cntr=0.3,0.1

Type RM Length L Ch R = 1 ,0.6158  ,149.73,149.64,151.5
BEGIN DESCRIPTION:
LR03  (SEM 2019)
END DESCRIPTION:
XS GIS Cut Line= 4
  570224.8816036 5425718.4011831  570014.6690036 5425324.9919831
  569991.8290036 5425294.6229831  569873.7157036 5425058.3668831
#Sta/Elev= 30
       0  101.16    5.99  100.57    44.9  100.47  213.55  101.01  245.48  100.61
  252.46  100.02  257.45  101.08   279.4  101.41  351.25  100.08  380.19  100.91
  428.09  100.57  443.05  100.23   452.7   98.18  455.93   96.83  458.66   95.92
  468.13   95.84  475.68   96.14   478.5   96.78  486.04   98.03     498   98.11
  534.88    97.7  542.86   97.06  563.79   97.84  571.76   98.67  586.71   98.58
  595.68  100.23  605.65   99.34   620.6   99.84  675.42   99.53  748.18  100.34
#Mann= 3 , 0 , 0
       0     .06       0  455.93     .05       0   478.5     .06       0
Bank Sta=455.93,478.5
XS Rating Curve= 0 ,0
Exp/Cntr=0.3,0.1

Type RM Length L Ch R = 1 ,0.4661  ,171.87,163.89,167.83
BEGIN DESCRIPTION:
School Rd - LR02 (SEM 2019)
END DESCRIPTION:
XS GIS Cut Line= 4
  570202.2855036 5425346.1416831  570124.1513036 5425223.3892831
  570081.7383036 5425173.5372831  569887.1582036 5425031.6998831
#Sta/Elev= 30
       0  103.87   70.76  101.01    88.7  101.19   94.68  100.88  135.54  100.65
  144.51   99.81  148.49   99.99  154.44   99.52  157.39   98.74  160.68   96.82
  177.22   95.79  203.64   95.96   206.4   96.56  208.37   97.06  214.38   97.14
  215.96   97.73  219.95   97.96  230.95   97.28  239.94   97.79  242.93   97.29
  245.93   98.01  250.93   98.35  256.92   98.17  263.92    99.7  267.91   98.45
  273.91   98.24  342.85   99.78  360.83   99.69  405.79  100.49  451.75  100.48
#Mann= 3 , 0 , 0
       0     .06       0  160.68     .05       0   206.4     .06       0
#XS Ineff= 2 , 0
                          262.79           99.72
Permanent Ineff=
       F       F
Bank Sta=160.68,206.4
XS Rating Curve= 0 ,0
Exp/Cntr=0.3,0.1

Type RM Length L Ch R = 1 ,0.3022  ,182.29,302.23,152.5
BEGIN DESCRIPTION:
LR01  (SEM 2019)
END DESCRIPTION:
XS GIS Cut Line= 5
  570284.2231036 5425229.9242831  570276.5901036 5425166.7154831
  570243.0550036 5425114.2269831  570200.3580036 5425058.0029831
  570163.3838036 5424992.5414831
#Sta/Elev= 30
       0  107.34    5.97  107.79   14.92  106.87   29.84  102.76   36.81  101.92
   41.78  101.02   43.77  100.25   55.71   98.44   62.67   98.45    69.6    99.8
   72.57   99.11   84.43   97.79   86.41   98.28   92.34   97.55   97.28   97.98
  105.19    97.1  111.12   97.63  120.02   97.33  126.95   98.09  128.01   97.29
  129.33   97.11  136.39   97.61  142.22   97.29  146.26   96.52  151.93   95.75
  166.55   95.55  191.32   95.61  211.39   97.44  252.94   99.33  271.74    99.2
#Mann= 3 , 0 , 0
       0     .06       0  146.26     .05       0  211.39     .12       0
#XS Ineff= 2 , 0
           68.93   99.77
Permanent Ineff=
       F       F
Bank Sta=146.26,211.39
XS Rating Curve= 0 ,0
Exp/Cntr=0.3,0.1

River Reach=Rushy Pond      ,Rushy Pond
Reach XY= 16
594039.3244358945421899.61768731594036.9632035985421802.09568309
594032.8720035985421724.36298309594002.0357035995421653.64928309
593917.3689035985421537.23238309593815.7687035995421448.33228309
593663.3684035995421319.21528309593604.1016035985421228.19848309
593595.6349035995421141.41498309593614.6850035985421080.03148309
593616.8016035995421003.83138309593631.6183035985420931.86458309
593580.8182035985420874.71438309593489.8014035985420826.03098309
593422.2466035985420768.53388309593346.3331035985420561.87178309
Reach Upstream Storage Area=Rushy Pond

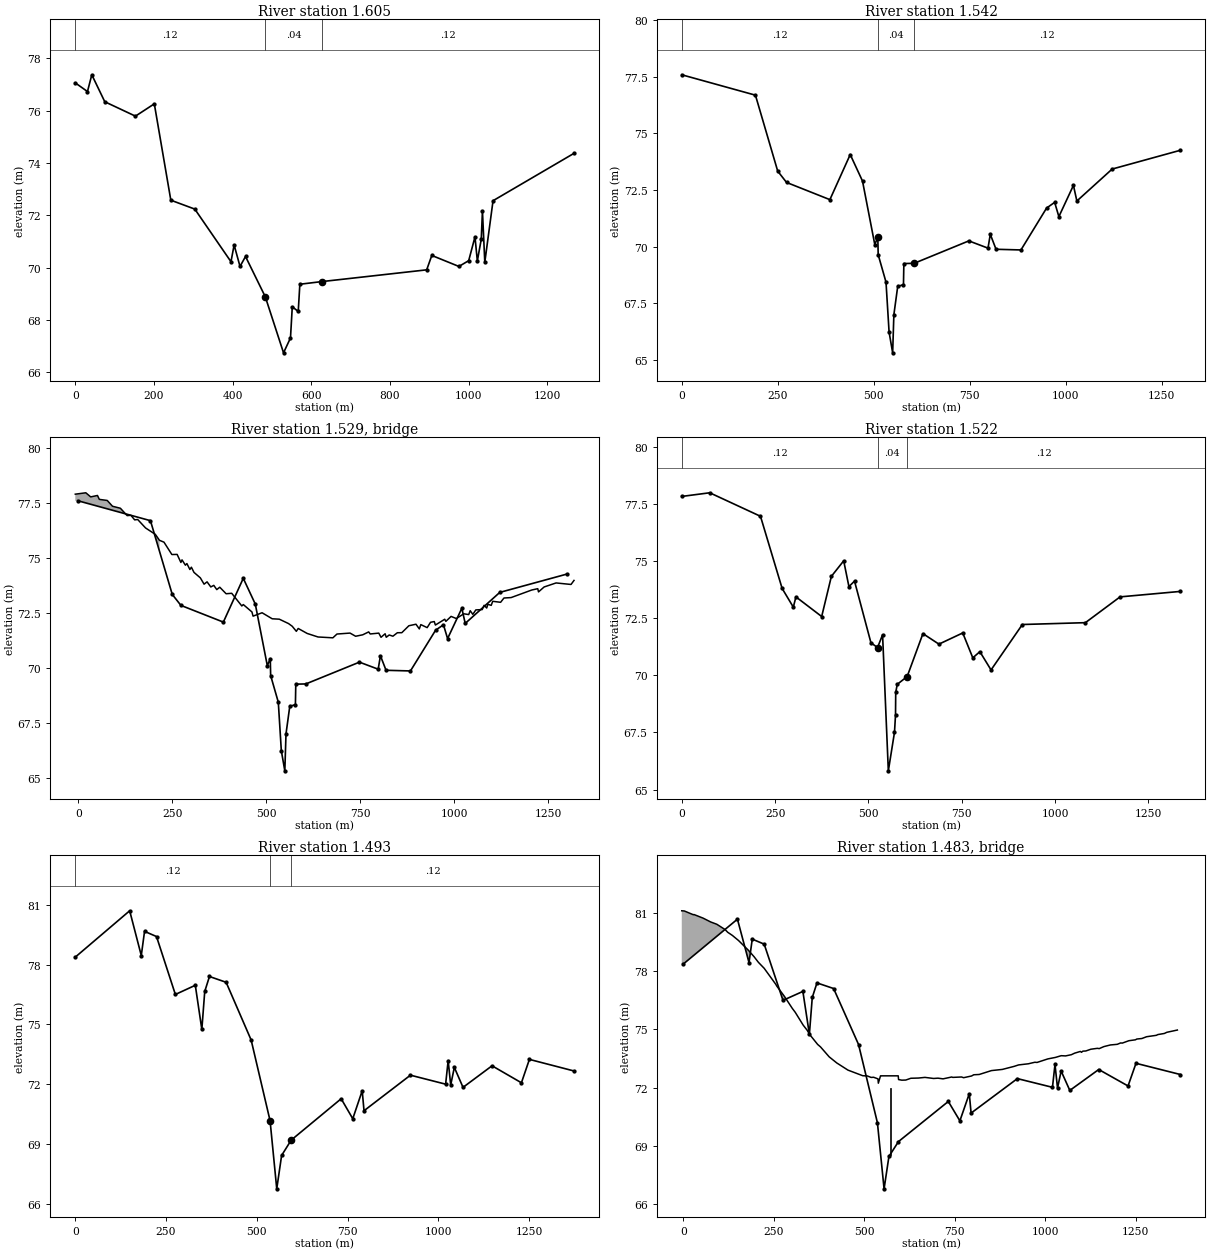
Type RM Length L Ch R = 1 ,1.605   ,63.85,62.61,66.16
BEGIN DESCRIPTION:
Rushy Pond - RP13 (SEM 2019)
END DESCRIPTION:
XS GIS Cut Line= 6
594571.4503035985421976.83008309594119.5832035985421886.85828309
594108.3648035985421886.01158309593916.1429035985421854.66458309
593532.4963035985421926.10218309593328.7667035985421980.34188309
#Sta/Elev= 30
       0   77.06   30.98   76.73   41.98   77.37   74.96   76.34  152.91   75.79
  200.89   76.26  242.86   72.58  303.83   72.24  395.77   70.23  403.77   70.87
  418.76   70.05  432.75   70.43  483.03   68.89  529.38   66.75  547.05   67.32
  551.62   68.51  566.75   68.33  570.87   69.37  625.99   69.47  893.31   69.92
  906.28   70.47  975.15   70.05  1000.1   70.27 1016.07   71.18 1022.06   70.26
 1032.04   71.09 1035.03   72.17 1041.02   70.21 1061.98   72.56 1267.82   74.37
#Mann= 3 , 0 , 0
       0     .12       0  483.03     .04       0  625.99     .12       0
Bank Sta=483.03,625.99
XS Rating Curve= 0 ,0
Exp/Cntr=0.3,0.1

Type RM Length L Ch R = 1 ,1.542   ,19.51,19.48,21.79
BEGIN DESCRIPTION:
US of Rushy Pond T'Railway Bridge - RP12 (SEM 2019)
END DESCRIPTION:
XS GIS Cut Line= 6
594582.8942035995421927.42518309594080.3750035995421821.29398309
594018.0850035995421807.94098309593913.4971035985421795.13318309
593551.0172035985421874.50838309593314.2146035985421936.68558309
#Sta/Elev= 30
       0   77.58  191.85   76.68  249.81   73.33  272.79   72.83   385.7   72.07
  438.66   74.06  470.64   72.89  502.61   70.09  510.46   70.41  511.48   69.64
  531.82   68.43  539.83   66.23  549.14   65.31  552.29   66.99  562.29   68.24
  577.31   68.32   578.3   69.25  605.07   69.26  747.52   70.25  797.39   69.93
  803.38   70.54  818.34   69.88  883.18   69.85  950.01    71.7  970.96   71.95
  981.93   71.32 1019.84    72.7 1028.81   72.01  1120.7   73.42 1298.58   74.25
#Mann= 3 , 0 , 0
       0     .12       0  510.46     .04       0  605.07     .12       0
Bank Sta=510.46,605.07
XS Rating Curve= 0 ,0
Exp/Cntr=0.3,0.1

Type RM Length L Ch R = 3 ,1.529   ,,,
Node Photo=.\Photos\RP-CR-3.JPG
BEGIN DESCRIPTION:
Rushy Pond T'Railway Bridge
END DESCRIPTION:
Node Name=RP-CR-3
Bridge Culvert--1,0,-1,-1, 0
Deck Dist Width WeirC Skew NumUp NumDn MinLoCord MaxHiCord MaxSubmerge Is_Ogee
5,4.2,1.4,0, 96, 96, , , 0.98, 0, 3,3,,
      -8   19.98   32.97  50.957  55.953  76.938  90.928 111.913   129.9 139.892
 149.885 157.879 178.864 204.845 215.837 227.828 248.813 262.803 272.795 275.793
 284.787 288.759 296.704 300.676 307.628 324.511 334.442 342.387 352.318 360.262
 368.207 376.152 393.035 407.931 434.779  438.77 461.722 464.716 488.665 515.609
 534.476 536.441 559.037 568.862 579.755  584.73 608.607 637.423 676.929 687.814
 722.524 737.399 756.265 772.158 776.131 798.978 804.938 815.857 818.815 826.703
 836.563 848.395 860.227 878.976 897.852 906.794 910.767 927.656 936.598 946.532
 949.513  974.35  977.33 991.2391005.1471025.0991038.0741042.0661049.0521057.037
1074.0031078.994 1085.981088.9741097.9561101.9491122.908 1131.891150.8531205.745
1221.714 1223.711238.6241270.4211310.1681318.117
  77.885  77.948  77.761  77.826  77.648  77.599  77.336  77.245   76.91  76.924
  76.716  76.734  76.349  76.058  75.788  75.703  75.141  75.147  74.781  74.898
  74.657  74.731   74.46  74.566  74.329  74.081  73.794    73.9  73.668   73.74
  73.547  73.656  73.359   73.38  72.804  72.867  72.531  72.341  72.495  72.221
  72.203  72.187  72.003  71.881  71.651  71.781  71.554  71.394  71.356  71.528
  71.571  71.427  71.493  71.625  71.531  71.569   71.38   71.54  71.381  71.485
  71.429  71.587  71.589  71.904  71.974  71.761  71.956  71.819  72.062  72.095
  71.937    72.2  72.104  72.329  72.232  72.448  72.412  72.589  72.422  72.625
  72.639  72.834   72.71  72.879  72.831  73.016   72.97  73.165  73.185  73.529
  73.589  73.442  73.667   73.85  73.781  73.965
  71.303  71.287  71.103
       5   32.98   45.97  63.957  68.953  89.938 103.928 124.913   142.9 152.892
 162.885 170.879 191.864 217.845 228.837 240.828 261.813 275.803 285.795 288.793
 297.787 301.759 309.704 313.676 320.628 337.511 347.442 355.387 365.318 373.262
 381.207 389.152 406.035 420.931 447.779  451.77 474.722 477.716 501.665 528.609
 547.476 549.441 572.037 581.862 592.755  597.73 621.607 650.423 689.929 700.814
 735.524 750.399 769.265 785.158 789.131 811.978 817.938 828.857 831.815 839.703
 849.563 861.395 873.227 891.976 910.852 919.794 923.767 940.656 949.598 959.532
 962.513  987.35  990.331004.2391018.1471038.0991051.0741055.0661062.0521070.037
1087.0031091.994 1098.981101.9741110.9561114.9491135.908 1144.891163.8531218.745
1234.714 1236.711251.6241283.4211323.1681331.117
  77.885  77.948  77.761  77.826  77.648  77.599  77.336  77.245   76.91  76.924
  76.716  76.734  76.349  76.058  75.788  75.703  75.141  75.147  74.781  74.898
  74.657  74.731   74.46  74.566  74.329  74.081  73.794    73.9  73.668   73.74
  73.547  73.656  73.359   73.38  72.804  72.867  72.531  72.341  72.495  72.221
  72.203  72.187  72.003  71.881  71.651  71.781  71.554  71.394  71.356  71.528
  71.571  71.427  71.493  71.625  71.531  71.569   71.38   71.54  71.381  71.485
  71.429  71.587  71.589  71.904  71.974  71.761  71.956  71.819  72.062  72.095
  71.937    72.2  72.104  72.329  72.232  72.448  72.412  72.589  72.422  72.625
  72.639  72.834   72.71  72.879  72.831  73.016   72.97  73.165  73.185  73.529
  73.589  73.442  73.667   73.85  73.781  73.965
  71.303  71.287  71.103
BR Coef=-1 , 0 , 0 ,, 0 ,,,0.8,-1,,0,
WSPro=,,,, 1 ,,,, 0 ,,,, 0 ,,,,-1 ,-1 ,-1 , 0 , 0 , 0 , 0 , 0
BC Design=,, 0 ,, 0 ,,,,,,
BC HTab HWMax=74
BC Use User HTab Curves=0
BC User HTab FreeFlow(D)= 0

Type RM Length L Ch R = 1 ,1.522   ,37.63,29.53,28.96
BEGIN DESCRIPTION:
DS of Rushy Pond T'Railway Bridge - RP11 (SEM 2019)
END DESCRIPTION:
XS GIS Cut Line= 5
594593.0807035985421906.91988309594067.0980035985421800.46598309
594019.1983035985421788.12178309593797.7416035985421759.94358309
593286.5656035985421885.35628309
#Sta/Elev= 30
       0   77.84   74.95      78  210.86   76.97  268.82   73.81   298.8   72.99
   305.8   73.44  374.75   72.58  400.74   74.34  433.72   75.02  447.71   73.89
   462.7   74.13  506.67   71.43  524.33   71.22  537.84   71.78  553.27   65.82
  569.77   67.51   572.5   68.27  573.06   69.26  577.21   69.61  603.67   69.95
  645.91   71.83  688.76   71.37  752.55   71.86  779.46   70.77  798.39   71.04
  828.33   70.24  912.22   72.23 1081.01   72.31 1173.89   73.44 1335.69   73.68
#Mann= 3 , 0 , 0
       0     .12       0  524.33     .04       0  603.67     .12       0
Bank Sta=524.33,603.67
XS Rating Curve= 0 ,0
Exp/Cntr=0.3,0.1

Type RM Length L Ch R = 1 ,1.493   ,32.58,30.63,37.38
BEGIN DESCRIPTION:
RP10 (SEM 2019)
END DESCRIPTION:
XS GIS Cut Line= 4
594597.0495035985421871.20108309594072.0990035985421766.30398309
594002.2170035985421760.24798309593237.3530035985421688.50588309
#Sta/Elev= 30
       0   78.37  149.81   80.69  181.77   78.45  190.76   79.66  223.72    79.4
  275.65    76.5  330.58   76.96  348.56   74.75  356.55   76.65  369.54    77.4
  415.48   77.11  484.39   74.22  536.52   70.18  554.91   66.77  568.29   68.44
  594.72   69.21  732.34   71.28  764.31   70.28  790.28   71.68  795.28   70.68
  923.15   72.46 1020.05   72.01 1027.04   73.19 1034.04   71.97 1044.03   72.85
    1068   71.85 1147.92   72.93 1228.84   72.08 1250.82   73.25  1373.7   72.67
#Mann= 3 , 0 , 0
       0     .12       0  536.52     .04       0  594.72     .12       0
Bank Sta=536.52,594.72
XS Rating Curve= 0 ,0
Exp/Cntr=0.3,0.1

Type RM Length L Ch R = 3 ,1.483   ,,,
Node Photo=.\Photos\RP-CR-2.JPG
BEGIN DESCRIPTION:
Rushy Pond TCH Bridge
END DESCRIPTION:
Node Name=RP-CR-2
Bridge Culvert--1,0,-1,-1, 0
Deck Dist Width WeirC Skew NumUp NumDn MinLoCord MaxHiCord MaxSubmerge Is_Ogee
15,8.6,1.4,0, 99, 99, , , 0.98, 0, 3,3,,
      -4    2.99  27.955  29.952  54.917  75.888  92.864 115.832 122.822 135.804
  152.78 179.742  195.72 207.703  223.68 255.634 258.625 279.561 301.495  309.47
 331.404 342.371 349.349 371.308 379.295 403.258 424.226 455.178 496.114 508.096
 519.079 526.068 538.049 539.047 545.038 546.036 551.028  556.02 559.015 566.004
 571.995  574.99 577.985 580.981 584.974 587.969 588.968  593.96 594.958 603.944
 614.927 628.904 649.871 667.844 691.808  703.79 717.769 741.732 744.728 768.692
 774.683  796.65 802.641 817.618 851.567 881.522 914.472 926.454 953.413 971.386
 977.3771007.332  1028.31044.2761056.2581072.234 1081.221097.1961100.1921104.186
1112.1741126.1681144.1651149.1641162.1611180.1581199.1541208.1521213.1511231.148
1249.1441253.1431267.1411280.1381307.1331311.1321329.1281336.1271365.121
  81.123  81.114  80.919  80.928  80.744  80.546  80.427  80.152  80.015  79.851
  79.589  79.091  78.753  78.463  78.154  77.331  77.233  76.705  76.081  75.883
  75.221  74.958  74.736  74.226  74.097  73.583  73.268  72.898  72.608    72.6
  72.521  72.529  72.446  72.223  72.603  72.603  72.603  72.603  72.603  72.603
  72.603  72.603  72.603  72.603  72.603  72.603  72.603  72.603   72.41  72.379
  72.386  72.478  72.489  72.523  72.467  72.483  72.447  72.543  72.523  72.544
  72.507  72.596  72.658  72.673  72.874  72.934  73.093  73.166  73.225  73.304
  73.294  73.477  73.554  73.643  73.631  73.694  73.773  73.863  73.819  73.878
  73.886  73.977  74.023  74.008  74.113  74.197   74.23    74.3  74.294  74.416
  74.462  74.503   74.53  74.622  74.695  74.733   74.79  74.851  74.967
                                  70.903  70.903  70.903  70.903  70.903  70.903
  70.903  70.903  70.903  70.903  70.903  70.903  70.903  70.903
       4   10.99  35.955  37.952  62.917  83.888 100.864 123.832 130.822 143.804
  160.78 187.742  203.72 215.703  231.68 263.634 266.625 287.561 309.495  317.47
 339.404 350.371 357.349 379.308 387.295 411.258 432.226 463.178 504.114 516.096
 527.079 534.068 546.049 547.047 553.038 554.036 559.028  564.02 567.015 574.004
 579.995  582.99 585.985 588.981 592.974 595.969 596.968  601.96 602.958 611.944
 622.927 636.904 657.871 675.844 699.808  711.79 725.769 749.732 752.728 776.692
 782.683  804.65 810.641 825.618 859.567 889.522 922.472 934.454 961.413 979.386
 985.3771015.332  1036.31052.2761064.2581080.234 1089.221105.1961108.1921112.186
1120.1741134.1681152.1651157.1641170.1611188.1581207.1541216.1521221.1511239.148
1257.1441261.1431275.1411288.1381315.1331319.1321337.1281344.1271373.121
  81.123  81.114  80.919  80.928  80.744  80.546  80.427  80.152  80.015  79.851
  79.589  79.091  78.753  78.463  78.154  77.331  77.233  76.705  76.081  75.883
  75.221  74.958  74.736  74.226  74.097  73.583  73.268  72.898  72.608    72.6
  72.521  72.529  72.446  72.223  72.603  72.603  72.603  72.603  72.603  72.603
  72.603  72.603  72.603  72.603  72.603  72.603  72.603  72.603   72.41  72.379
  72.386  72.478  72.489  72.523  72.467  72.483  72.447  72.543  72.523  72.544
  72.507  72.596  72.658  72.673  72.874  72.934  73.093  73.166  73.225  73.304
  73.294  73.477  73.554  73.643  73.631  73.694  73.773  73.863  73.819  73.878
  73.886  73.977  74.023  74.008  74.113  74.197   74.23    74.3  74.294  74.416
  74.462  74.503   74.53  74.622  74.695  74.733   74.79  74.851  74.967
                                  70.903  70.903  70.903  70.903  70.903  70.903
  70.903  70.903  70.903  70.903  70.903  70.903  70.903  70.903
Pier Skew, UpSta & Num, DnSta & Num=  ,571.75, 2 ,579.75, 2 , 0 , 0 , 0 ,,
       2       2
       0      72
       2       2
       0      72
BR Coef=-1 , 0 , 0 ,, 0 ,,,0.8,-1,,0,
WSPro=,,,, 1 ,,,, 0 ,,,, 0 ,,,,-1 ,-1 ,-1 , 0 , 0 , 0 , 0 , 0
BC Design=,, 0 ,, 0 ,,,,,,
BC HTab HWMax=76
BC Use User HTab Curves=0
BC User HTab FreeFlow(D)= 0