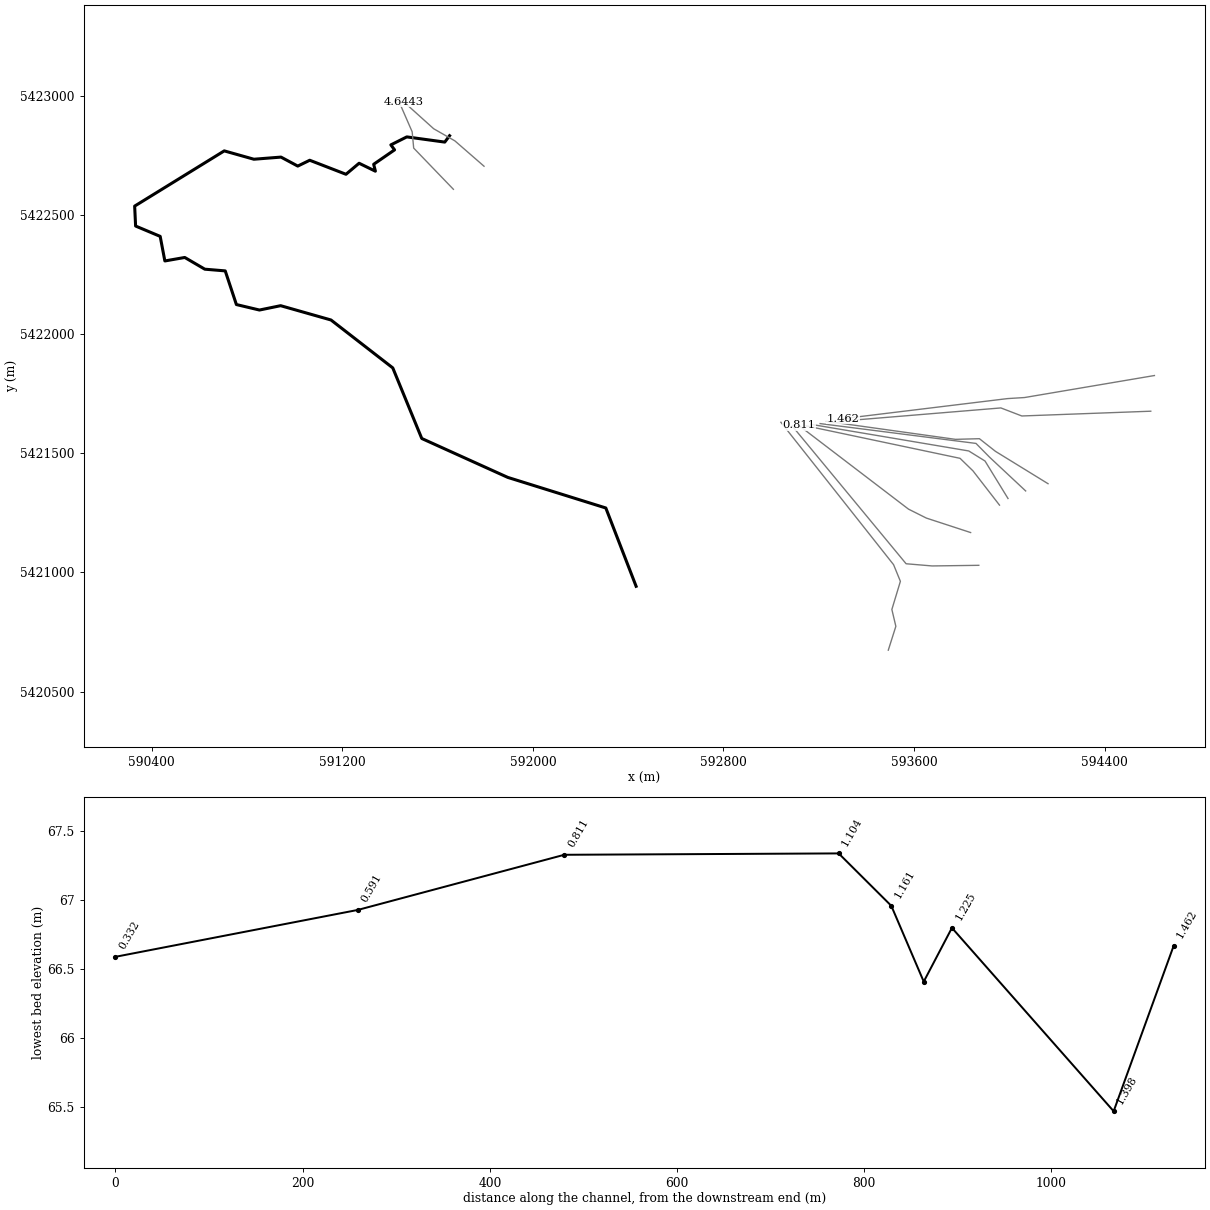
HEC-RAS study Exploits_FMM.prj: Exploits_FMM

--- Exploits_FMM.g01 (geometry) --- (continued)

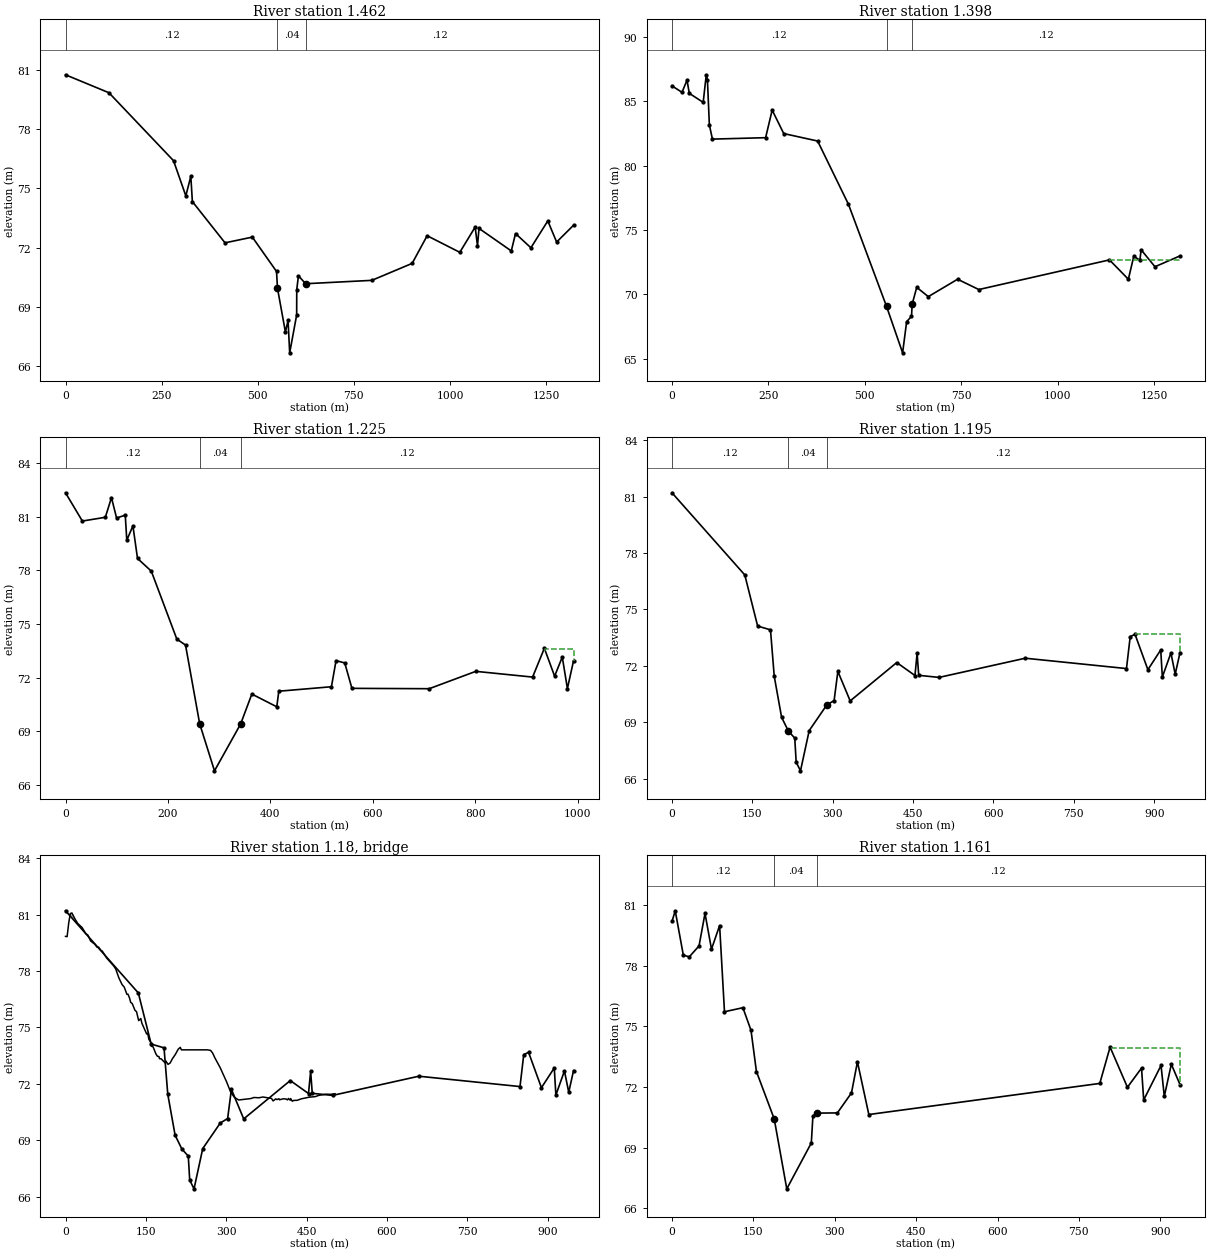
Type RM Length L Ch R = 1 ,1.462   ,77.12,64.12,47.6
BEGIN DESCRIPTION:
RP09 (SEM 2019)
END DESCRIPTION:
XS GIS Cut Line= 4
594608.9557035985421826.75098309594063.9130035985421734.41118309
593992.2108035985421729.91328309593300.8531035995421645.64338309
#Sta/Elev= 30
       0   80.75  112.96   79.84   280.9    76.4  312.89   74.62  325.89   75.61
  329.89   74.33  414.86   72.24  485.83   72.53  548.81   70.79  551.21   69.94
  571.83   67.73  578.74   68.31  582.97   66.67  601.11   68.59  601.34   69.87
  605.71   70.57  624.45   70.17  796.52   70.34  901.45    71.2  940.42    72.6
 1025.36   71.76 1065.33   73.04 1071.32   72.09 1075.32   72.97 1159.26   71.83
 1170.25   72.71 1210.22   71.99 1254.19   73.35 1277.17   72.28 1321.14   73.13
#Mann= 3 , 0 , 0
       0     .12       0  551.21     .04       0  624.45     .12       0
Bank Sta=551.21,624.45
XS Rating Curve= 0 ,0
Exp/Cntr=0.3,0.1

Type RM Length L Ch R = 1 ,1.398   ,183.71,172.77,159.43
BEGIN DESCRIPTION:
RP08 (SEM 2019)
END DESCRIPTION:
XS GIS Cut Line= 4
594593.6099035985421676.99648309594052.2840035995421656.97798309
593964.4294035985421690.75488309593284.9781035995421634.53078309
#Sta/Elev= 30
       0   86.18   25.99   85.68   38.98   86.62   44.97    85.6   80.95    84.9
   88.95   87.04   91.95   86.67   96.95   83.15  104.94   82.05  242.86   82.16
  259.85    84.3  289.84   82.48  377.79    81.9  457.74   76.99  556.51   69.07
  598.17   65.47  608.61   67.89  621.21    68.3  622.95   69.25  634.83   70.55
  664.81   69.83  740.78   71.18  795.77   70.38 1134.66   72.68 1183.64   71.18
 1197.64   72.95 1213.63   72.66 1216.63   73.47 1252.62   72.15  1317.6   72.99
#Mann= 3 , 0 , 0
       0     .12       0  556.51     .04       0  622.95     .12       0
#XS Ineff= 2 , 0
                         1132.62           72.68
Permanent Ineff=
       F       F
Bank Sta=556.51,622.95
XS Rating Curve= 0 ,0
Exp/Cntr=0.3,0.1

Type RM Length L Ch R = 1 ,1.225   ,35.7,30.12,24.68
BEGIN DESCRIPTION:
RP07 (SEM 2019)
END DESCRIPTION:
XS GIS Cut Line= 5
594162.3382035985421372.72508309593941.5429035985421508.58888309
593874.2460035985421561.63198309593773.9687035985421558.85388309
593232.5905035995421634.53078309
#Sta/Elev= 30
       0   82.34    32.9   80.76   77.77   80.97   89.74   82.07   99.71   80.93
  116.66   81.09  119.65   79.69  131.62   80.49  140.59   78.67  167.51   77.96
  217.37   74.16  234.32   73.83  261.95   69.43  290.87    66.8  341.93   69.42
  363.81   71.09  412.48   70.38  416.45   71.25   519.2    71.5   528.2   72.96
  545.19   72.83  559.18   71.41  710.08   71.39  801.02   72.36  911.95   72.04
  934.93   73.65  954.92   72.09  969.91   73.16   979.9    71.4   991.9   72.95
#Mann= 3 , 0 , 0
       0     .12       0  261.95     .04       0  341.93     .12       0
#XS Ineff= 2 , 0
                          936.74           73.63
Permanent Ineff=
       F       F
Bank Sta=261.95,341.93
XS Rating Curve= 0 ,0
Exp/Cntr=0.3,0.1

Type RM Length L Ch R = 1 ,1.195   ,28.04,34.66,44.69
BEGIN DESCRIPTION:
US of Gold Course Bridge - RP06 (SEM 2019)
END DESCRIPTION:
XS GIS Cut Line= 4
594068.4109035985421342.29798309593917.3335035985421483.58568309
593859.8910035985421541.78598309593205.6029035985421625.00578309
#Sta/Elev= 30
       0    81.2   135.9   76.83  159.88   74.11  183.87   73.91  190.86   71.44
  204.57   69.26  217.15   68.53  229.15   68.15  231.81   66.87  239.87   66.41
   256.1   68.55  288.84   69.91  302.61   70.15  309.61    71.7  332.59   70.13
  419.54   72.17  453.51   71.48  457.51   72.66  460.51   71.49  498.48   71.38
  659.37    72.4  848.25   71.85  855.24   73.55  864.24   73.67  888.22   71.79
   912.2   72.84   915.2    71.4  931.19   72.68  939.19   71.55  948.18    72.7
#Mann= 3 , 0 , 0
       0     .12       0  217.15     .04       0  288.84     .12       0
#XS Ineff= 2 , 0
                          864.19           73.71
Permanent Ineff=
       F       F
Bank Sta=217.15,288.84
XS Rating Curve= 0 ,0
Exp/Cntr=0.3,0.1

Type RM Length L Ch R = 3 ,1.18    ,,,
Node Photo=.\Photos\RP-CR-1.JPG
BEGIN DESCRIPTION:
Golf Course Bridge
END DESCRIPTION:
Node Name=RP-CR-1
Bridge Culvert--1,0,-1,-1, 0
Deck Dist Width WeirC Skew NumUp NumDn MinLoCord MaxHiCord MaxSubmerge Is_Ogee
18,3,1.4,0, 100, 100, , , 0.98, 0, 3,3,,
       0    2.99    5.98    8.97  11.959  17.939  22.922  30.895  37.872  41.858
  46.841  54.814  58.801  61.791  65.777  68.767   76.74  89.696  93.683  99.662
 105.642 109.629 114.612 116.605 119.595 121.588 124.578 129.561 132.551 136.537
 140.524 142.517 151.487  153.48 155.473 158.463 160.456 163.446 168.429 171.419
 174.409 175.406 178.395 186.368 187.365 191.352 195.338 199.325 205.284 210.243
 214.209 216.192 217.184 220.159 221.151 224.125 225.117  233.05 235.033 238.008
 256.849 257.841 260.816 262.799 263.791 264.782 270.732 274.699 278.658 288.548
 300.417  308.33 315.253 323.166 345.914 351.849 360.752 368.669 384.502 387.482
 392.449 394.436 398.409 399.403 406.357 412.317 414.304 416.291 419.271 420.265
 423.245 426.225 432.196 440.165  454.11 466.063 473.036 486.487 495.146 503.105
  79.839  79.824   80.55  81.054  81.083  80.751  80.523   80.31  79.985  79.901
  79.593  79.417  79.263  79.267  79.104  79.052  78.689  78.274  78.106  77.625
  77.271   77.14  76.756  76.763  76.553  76.332  76.262  75.911  75.832  75.356
  75.471  75.222  74.645  74.691  74.369  74.235  73.993  73.966  73.603  73.466
  73.445  73.332  73.329  73.096  73.207  73.029  73.106  73.321  73.572  73.833
  73.936  73.803  73.803  73.803  73.803  73.803  73.803  73.803  73.803  73.803
  73.803  73.803  73.803  73.803  73.803  73.803  73.775  73.628  73.383  72.863
  72.117   71.55  71.278  71.136  71.212  71.269  71.254  71.295  71.217  71.086
  71.197  71.155  71.202  71.148  71.199  71.184   71.14  71.218  71.124  71.208
   71.07  71.115  71.117  71.198  71.282  71.315  71.384  71.444  71.438  71.469
          73.403  73.403  73.403  73.403  73.403  73.403  73.403  73.403  73.403
  73.403  73.403  73.403  73.403  73.403  73.403
     -20  -17.01  -14.02  -11.03  -8.041  -2.061   2.922  10.895  17.872  21.858
  26.841  34.814  38.801  41.791  45.777  48.767   56.74  69.696  73.683  79.662
  85.642  89.629  94.612  96.605  99.595 101.588 104.578 109.561 112.551 116.537
 120.524 122.517 131.487  133.48 135.473 138.463 140.456 143.446 148.429 151.419
 154.409 155.406 158.395 166.368 167.365 171.352 175.338 179.325 185.284 190.243
 194.209 196.192 197.184 200.159 201.151 204.125 205.117  213.05 215.033 218.008
 236.849 237.841 240.816 242.799 243.791 244.782 250.732 254.699 258.658 268.548
 280.417  288.33 295.253 303.166 325.914 331.849 340.752 348.669 364.502 367.482
 372.449 374.436 378.409 379.403 386.357 392.317 394.304 396.291 399.271 400.265
 403.245 406.225 412.196 420.165  434.11 446.063 453.036 466.487 475.146 483.105
  79.839  79.824   80.55  81.054  81.083  80.751  80.523   80.31  79.985  79.901
  79.593  79.417  79.263  79.267  79.104  79.052  78.689  78.274  78.106  77.625
  77.271   77.14  76.756  76.763  76.553  76.332  76.262  75.911  75.832  75.356
  75.471  75.222  74.645  74.691  74.369  74.235  73.993  73.966  73.603  73.466
  73.445  73.332  73.329  73.096  73.207  73.029  73.106  73.321  73.572  73.833
  73.936  73.803  73.803  73.803  73.803  73.803  73.803  73.803  73.803  73.803
  73.803  73.803  73.803  73.803  73.803  73.803  73.775  73.628  73.383  72.863
  72.117   71.55  71.278  71.136  71.212  71.269  71.254  71.295  71.217  71.086
  71.197  71.155  71.202  71.148  71.199  71.184   71.14  71.218  71.124  71.208
   71.07  71.115  71.117  71.198  71.282  71.315  71.384  71.444  71.438  71.469
          73.403  73.403  73.403  73.403  73.403  73.403  73.403  73.403  73.403
  73.403  73.403  73.403  73.403  73.403  73.403
BR Coef=-1 , 0 , 0 ,, 0 ,,,0.8,-1,,0,
WSPro=,,,, 1 ,,,, 0 ,,,, 0 ,,,,-1 ,-1 ,-1 , 0 , 0 , 0 , 0 , 0
BC Design=,, 0 ,, 0 ,,,,,,
BC HTab HWMax=76
BC Use User HTab Curves=0
BC User HTab FreeFlow(D)= 0

Type RM Length L Ch R = 1 ,1.161   ,62.62,56.22,46.95
BEGIN DESCRIPTION:
DS of Golf Course Bridge - RP05 (SEM 2019)
END DESCRIPTION:
XS GIS Cut Line= 4
593994.3274035985421310.54788309593897.8410035995421467.89198309
593829.5460035985421510.13898309593167.5029035985421621.83078309
#Sta/Elev= 30
       0    80.2    5.99   80.73   20.95   78.53   31.93   78.45   49.88   78.99
   60.86    80.6   72.83   78.83    87.8      80   96.78   75.73   130.7   75.93
  145.66   74.81  155.64   72.77  188.46   70.42  211.57   66.96  256.79   69.23
  259.73   70.56  266.57   70.71  304.84   70.72  330.82   71.71  341.81   73.25
  362.79   70.64  788.41   72.18   807.4   73.98  839.37   71.99  865.35   72.94
  869.34   71.36  901.31   73.07  907.31   71.54   920.3   73.13  936.28   72.12
#Mann= 3 , 0 , 0
       0     .12       0  188.46     .04       0  266.57     .12       0
#XS Ineff= 2 , 0
                          808.37           73.92
Permanent Ineff=
       F       F
Bank Sta=188.46,266.57
XS Rating Curve= 0 ,0
Exp/Cntr=0.3,0.1

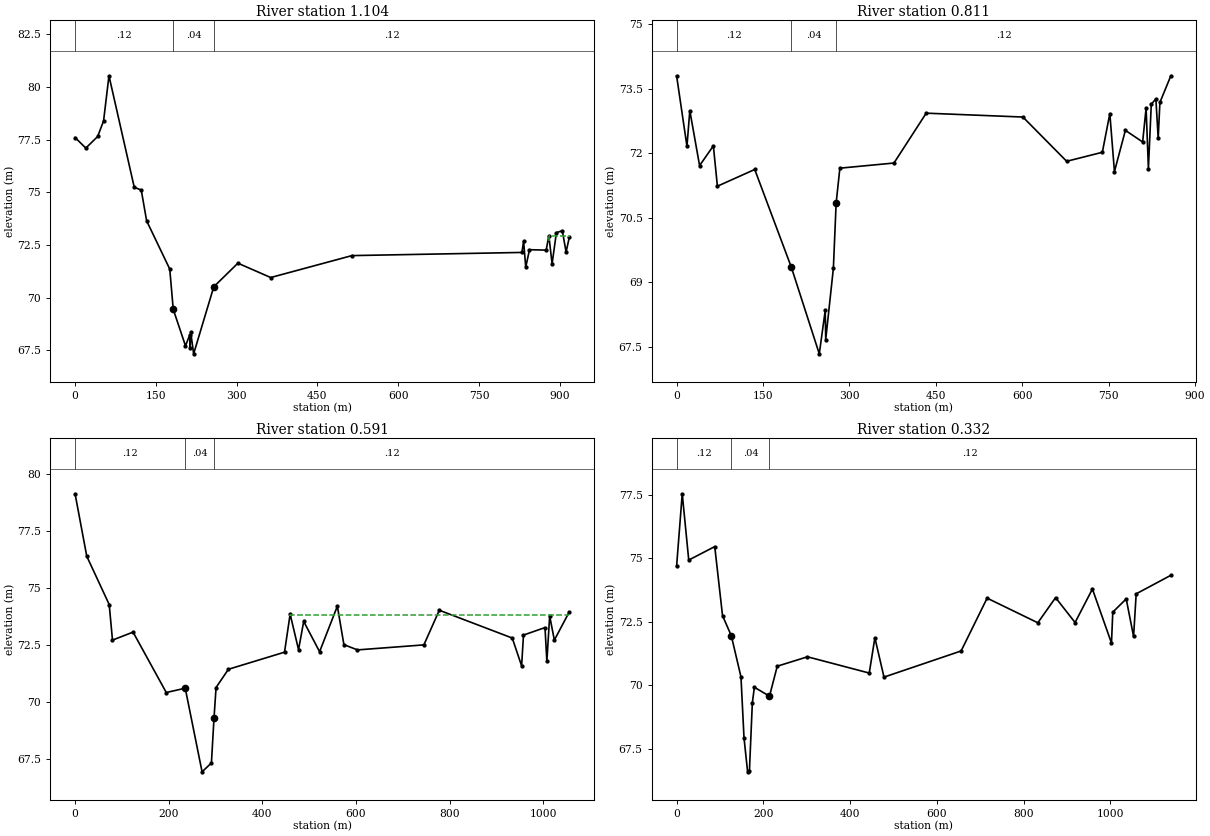
Type RM Length L Ch R = 1 ,1.104   ,281.55,293.12,309.8
BEGIN DESCRIPTION:
RP04 (SEM 2019)
END DESCRIPTION:
XS GIS Cut Line= 4
593958.6086035995421282.76658309593847.2840035995421426.55298309
593793.0602035985421479.18748309593146.8653035985421615.48078309
#Sta/Elev= 30
       0    77.6   19.98    77.1   41.96   77.65   52.95   78.39   62.95   80.53
  109.91   75.24   122.9   75.11  132.89   73.65  175.85   71.36  182.32   69.45
  205.05   67.72  213.08   68.24  213.66   67.64  214.71   68.38  220.19   67.34
  257.58   70.52  302.37   71.64  363.32   70.96  514.19      72   829.9   72.15
   832.9   72.69  836.89   71.45  843.89   72.28  874.86   72.26  879.85   72.94
  885.85   71.61  893.84   73.09  904.83   73.18  911.82   72.17  917.82   72.87
#Mann= 3 , 0 , 0
       0     .12       0  182.32     .04       0  257.58     .12       0
#XS Ineff= 2 , 0
                          880.93           72.94
Permanent Ineff=
       F       F
Bank Sta=182.32,257.58
XS Rating Curve= 0 ,0
Exp/Cntr=0.3,0.1

Type RM Length L Ch R = 1 ,0.811   ,219.57,220.6,242.99
BEGIN DESCRIPTION:
RP03 (SEM 2019)
END DESCRIPTION:
XS GIS Cut Line= 4
593837.3410035995421167.67258309593651.5840035985421228.37898309
593576.5180035985421266.00898309593116.7028035985421617.06828309
#Sta/Elev= 30
       0    73.8   17.95   72.16   22.93   72.99   39.88   71.71   63.81   72.17
   70.79   71.23   135.6   71.62  199.29   69.34  247.65   67.33  257.99   68.34
   258.8   67.66  272.13   69.32  276.92   70.84  283.39   71.65  377.31   71.77
  433.26   72.93  601.12   72.84  677.06   71.81     739   72.02  751.99   72.92
  759.99   71.57  778.97   72.53  808.95   72.26  814.94   73.05  818.94   71.64
  823.93   73.14  831.93   73.26  835.92   72.35  838.92   73.18   857.9    73.8
#Mann= 3 , 0 , 0
       0     .12       0  199.29     .04       0  276.92     .12       0
#XS Ineff= 2 , 0
                          433.49           72.92
Permanent Ineff=
       F       F
Bank Sta=199.29,276.92
XS Rating Curve= 0 ,0
Exp/Cntr=0.3,0.1

Type RM Length L Ch R = 1 ,0.591   ,316.1,258.95,211.39
BEGIN DESCRIPTION:
RP02 (SEM 2019)
END DESCRIPTION:
XS GIS Cut Line= 4
593871.7369035995421030.08898309593675.9448035985421027.44318309
593566.5720035985421036.64998309593088.5687035985421614.81928309
#Sta/Elev= 30
       0   79.13   24.98   76.39   72.93   74.27   79.92   72.71  123.88   73.06
  194.81   70.41  235.32    70.6  271.31   66.93  291.26   67.32  296.77   69.28
  301.19   70.63  327.54   71.43  447.41   72.18   459.4   73.85  477.38   72.29
  488.37   73.53  522.33    72.2  560.29    74.2  574.27   72.51  603.24   72.28
  745.09    72.5  778.05   74.02  933.88    72.8  953.86   71.58  957.86   72.93
 1003.81   73.26  1007.8   71.78  1013.8   73.77 1023.79   72.71 1055.75   73.95
#Mann= 3 , 0 , 0
       0     .12       0  235.32     .04       0  296.77     .12       0
#XS Ineff= 2 , 0
                          458.79            73.8
Permanent Ineff=
       F       F
Bank Sta=235.32,296.77
XS Rating Curve= 0 ,0
Exp/Cntr=0.3,0.1

Type RM Length L Ch R = 1 ,0.332   ,19.87,331.75,35.98
BEGIN DESCRIPTION:
RP01 (SEM 2019)
END DESCRIPTION:
XS GIS Cut Line= 6
593491.7945035985420673.95908309593523.5445035985420773.97178309
593506.8050035985420844.70498309593542.5946035985420962.88468309
593514.0195035985421032.73478309593040.9436035995421630.69438309
#Sta/Elev= 30
       0   74.69   12.99   77.54   27.98   74.93   87.94   75.46  105.91   72.74
  126.15   71.95  148.41   70.33  155.43   67.93  163.74   66.59  167.89   66.61
  174.62    69.3  179.33   69.92  214.18   69.57   232.1   70.75  301.81   71.12
  444.23   70.48  457.22   71.87  478.21   70.32  656.08   71.35  716.04   73.43
  832.95   72.46  873.92   73.45  918.89   72.47  958.86   73.79 1002.83   71.66
 1005.83   72.88 1036.81    73.4 1053.79   71.92 1059.79    73.6 1139.73   74.33
#Mann= 3 , 0 , 0
       0     .12       0  126.15     .04       0  214.18     .12       0
#XS Ineff= 2 , 0
                          715.53           73.38
Permanent Ineff=
       F       F
Bank Sta=126.15,214.18
XS Rating Curve= 0 ,0
Exp/Cntr=0.3,0.1

River Reach=Wigwam Brook    ,Wigwam Brook
Reach XY= 30
     591650.1718     5422833.423     591629.9973     5422806.634
     591470.5855     5422828.462     591403.7384     5422794.953
      591419.296     5422773.998     591331.5963     5422713.527
     591338.8724     5422684.423     591270.3716     5422717.827
     591215.3514     5422671.551     591063.2157     5422730.421
     591012.9448     5422705.947     590942.4993      5422743.65
     590828.7282      5422734.72     590704.3738     5422769.778
     590328.2679     5422537.936     590332.2576      5422454.28
     590435.4453     5422410.888     590455.0245     5422307.701
      590538.633     5422322.359     590622.7707     5422273.146
     590708.4958     5422266.002     590755.3272     5422124.714
     590852.1649     5422101.696      590941.065     5422119.952
     591152.4675     5422059.891     591411.7597     5421858.808
     591533.4683     5421562.474     591894.6253     5421399.093
     592306.0532      5421270.77     592433.2195      5420942.03

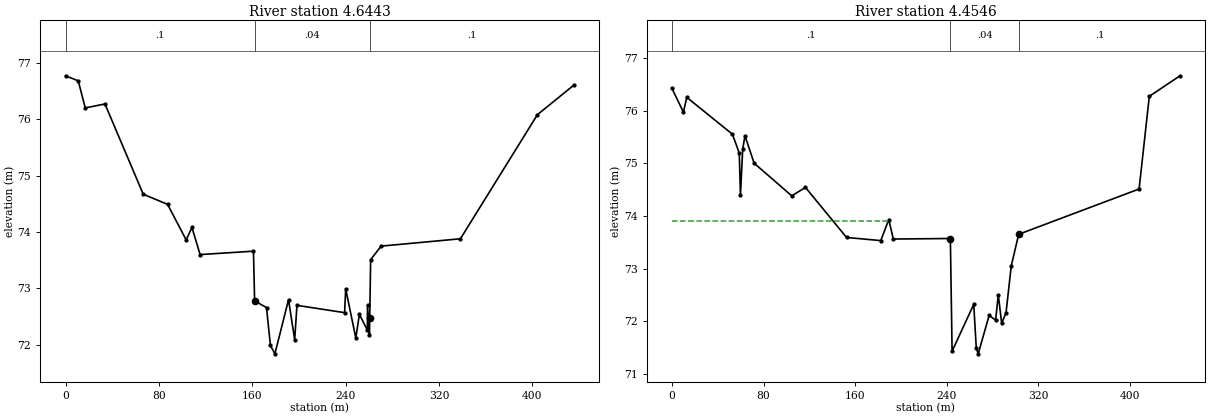
Type RM Length L Ch R = 1 ,4.6443  ,200.6,189.72,178.83
BEGIN DESCRIPTION:
WB28 (SEM 2019)
END DESCRIPTION:
XS GIS Cut Line= 4
591794.8142035995422705.35608309591672.5765035985422811.71878309
591583.6763035985422862.51888309591456.6761035985422976.81908309
#Sta/Elev= 30
       0   76.77   10.93   76.68    16.9    76.2    33.8   76.27    66.6   74.67
   87.48   74.49  103.38   73.86  108.35   74.08  115.31    73.6  161.04   73.66
  162.03   72.78  172.22   72.66  175.57   71.99   179.4   71.84  191.08    72.8
  196.36   72.09   198.3    72.7  239.13   72.57  240.07   72.99  248.74   72.12
   251.8   72.54  258.61   72.26  258.75    72.7  260.43   72.17  260.64   72.47
  261.44   73.51  270.42   73.75  338.36   73.88  404.31   76.08  435.29    76.6
#Mann= 3 , 0 , 0
       0      .1       0  162.03     .04       0  260.64      .1       0
Bank Sta=162.03,260.64
XS Rating Curve= 0 ,0
Exp/Cntr=0.3,0.1

Type RM Length L Ch R = 1 ,4.4546  ,67.95,39.34,44.12
BEGIN DESCRIPTION:
WB27 (SEM 2019)
END DESCRIPTION:
XS GIS Cut Line= 4
591666.2265035995422608.51838309591499.5386035985422781.55618309
591493.1886035995422849.81888309591439.2135035985422973.64408309
#Sta/Elev= 30
       0   76.42    9.97   75.97   12.96   76.25   52.84   75.55   58.82   75.19
   59.82   74.39   61.81   75.27    63.8   75.52   71.78      75  104.68   74.38
  116.64   74.54  152.53   73.59  182.44   73.53  189.42   73.93  193.41   73.56
  243.24   73.57  244.76   71.43  263.67   72.32  265.88   71.49  267.58   71.38
  277.12   72.11  282.78   72.02  285.11    72.5  288.08   71.96  291.88   72.16
  296.45   73.05  302.94   73.65  408.14   74.51  417.08   76.27   443.9   76.66
#Mann= 3 , 0 , 0
       0      .1       0  243.24     .04       0  302.94      .1       0
#XS Ineff= 2 , 0
          189.77    73.9
Permanent Ineff=
       F       F
Bank Sta=243.24,302.94
XS Rating Curve= 0 ,0
Exp/Cntr=0.3,0.1