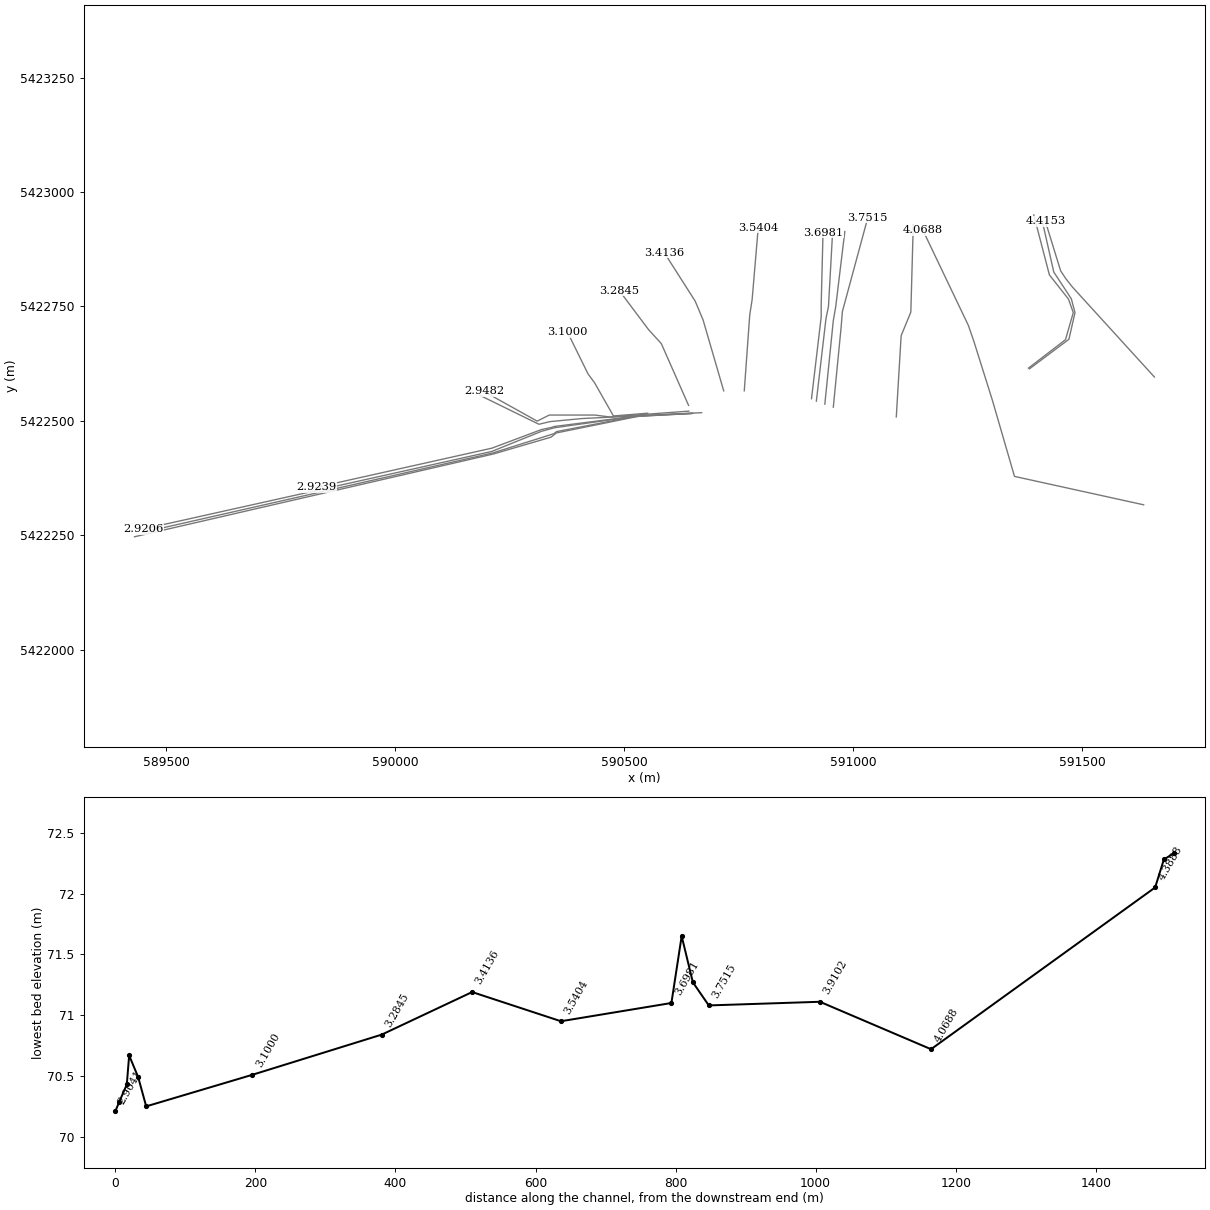
HEC-RAS study Exploits_FMM.prj: Exploits_FMM

--- Exploits_FMM.g01 (geometry) --- (continued)

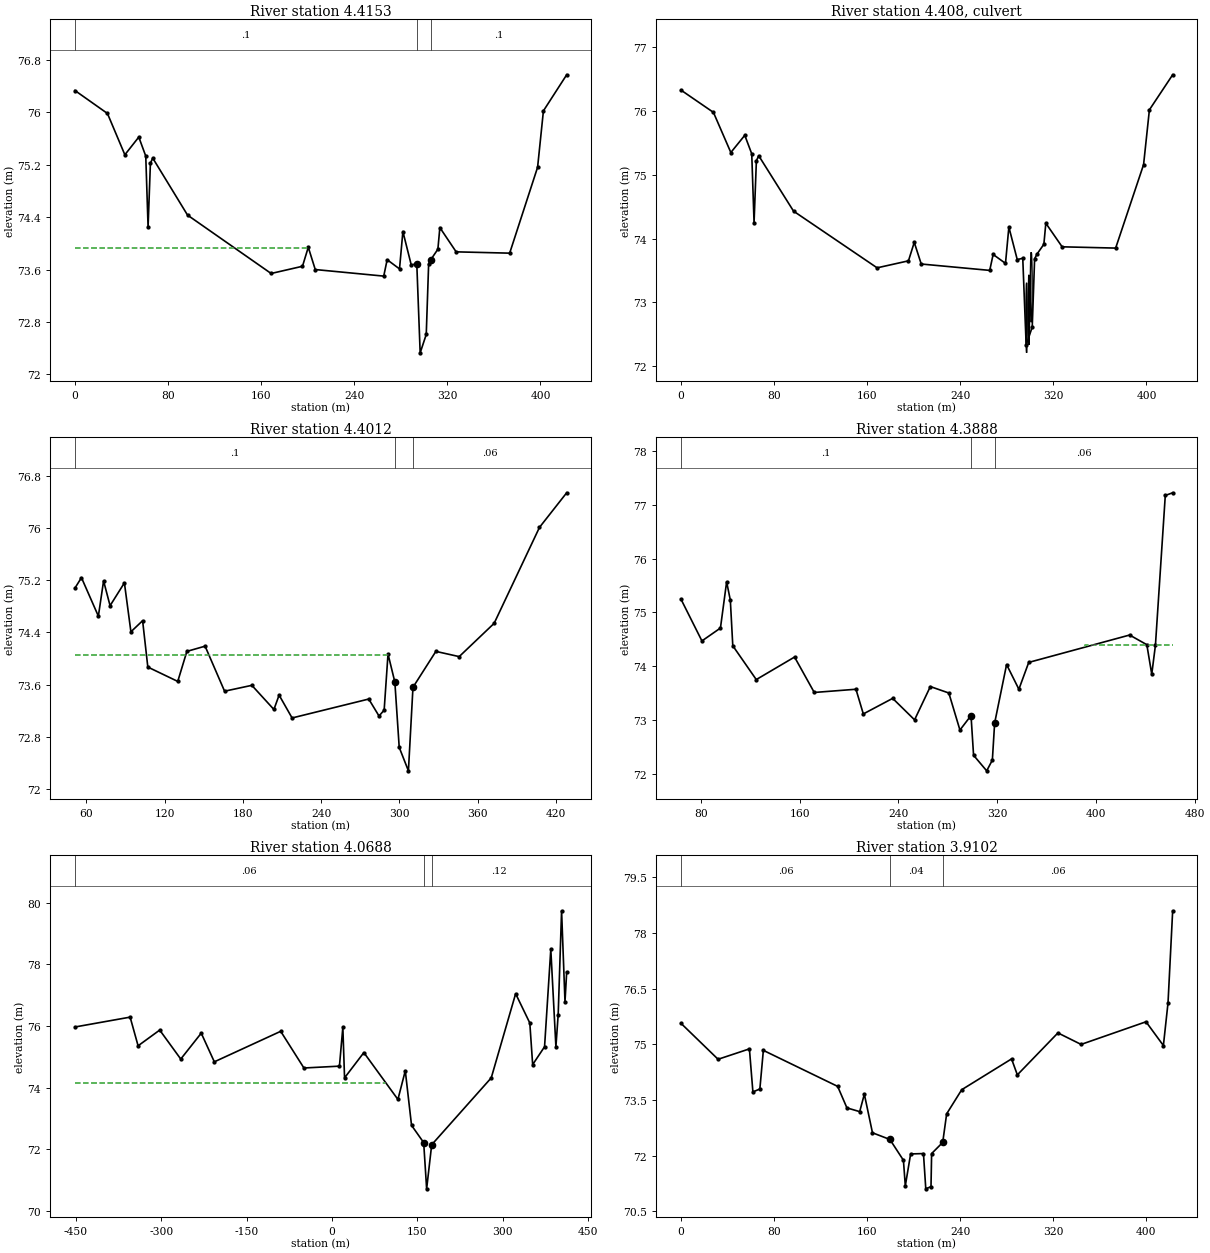
Type RM Length L Ch R = 1 ,4.4153  ,13.76,14.02,13.8
BEGIN DESCRIPTION:
US of Wigwam Brook Unnamed Road 2 Culvert - WB26 (SEM 2019)
END DESCRIPTION:
XS GIS Cut Line= 5
591658.2890035995422595.81838309591478.9011035985422792.66878309
591464.6136035985422810.92498309591453.5010035985422827.59378309
591420.1635035985422935.54398309
#Sta/Elev= 30
       0   76.33   27.93   75.98   42.89   75.35   54.86   75.62   60.85   75.33
   62.84   74.25   64.84   75.22   66.83    75.3   96.76   74.43  168.57   73.54
  195.51   73.65  200.49   73.94  206.48    73.6  265.33    73.5  268.26   73.75
  278.88   73.61  281.78   74.18  288.97   73.67  293.72   73.69  296.63   72.33
  301.85   72.61   303.9   73.68  305.74   73.75  311.85   73.91  313.54   74.24
  327.54   73.87  373.53   73.85  397.53   75.16  402.53   76.02  422.52   76.57
#Mann= 3 , 0 , 0
       0      .1       0  293.72     .04       0  305.74      .1       0
#XS Ineff= 2 , 0
          200.93   73.93
Permanent Ineff=
       F       F
Bank Sta=293.72,305.74
XS Rating Curve= 0 ,0
Exp/Cntr=0.3,0.1

Type RM Length L Ch R = 2 ,4.408   ,,,
Node Photo=.\Photos\WB-CR-5.JPG
BEGIN DESCRIPTION:
Wigwam Brook Unnamed Road 2 Culvert
END DESCRIPTION:
Node Name=WB-CR-5
Bridge Culvert--1,0,-1,-1, 0
Deck Dist Width WeirC Skew NumUp NumDn MinLoCord MaxHiCord MaxSubmerge Is_Ogee
2,6,1.4,0, 435, 435, , , 0.98, 0, 3,3,,
       0    .999   1.997   2.996   3.995   4.994   5.992   6.991    7.99   8.988
   9.987  10.986  11.985  12.983  13.982  14.981  15.979  16.978  17.977  18.976
  19.974  20.973  21.972   22.97  23.969  24.968  25.967  26.965  27.964  28.963
  29.961   30.96  31.959  32.958  33.956  34.955  35.954  36.952  37.951   38.95
  39.949  40.947  41.946  42.945  43.943  44.942  45.941   46.94  47.938  48.937
  49.936  50.934  51.929  52.924  53.918  54.913  55.908  56.902  57.897  58.892
  59.886  60.881  61.876   62.87  63.865  64.859  65.854  66.849  67.843  68.838
  69.833  70.827  71.822  72.817  73.811  74.806  75.801  76.795   77.79  78.784
  79.779  80.774  81.768  82.763  83.758  84.752  85.747  86.742  87.736  88.731
  89.726   90.72  91.715   92.71  93.704  94.699  95.693  96.688  97.683  98.677
  99.672 100.667 101.661 102.656 103.651 104.645  105.64 106.635 107.629 108.624
 109.619 110.613 111.608 112.602 113.597 114.592 115.586 116.581 117.576  118.57
 119.565  120.56 121.554 122.537  123.52 124.503 125.485 126.468 127.451 128.434
 129.416 130.399 131.382 132.365 133.348  134.33 135.313 136.296 137.279 138.261
 139.244 140.227  141.21 142.193 143.175 144.158 145.141 146.124 147.106 148.089
 149.072 150.055 151.017  151.98 152.942 153.905 154.868  155.83 156.793 157.755
 158.718  159.68 160.643 161.606 162.568 163.531 164.493 165.456 166.418 167.381
 168.344 169.306 170.269 171.231 172.194 173.157 174.132 175.108 176.084  177.06
 178.036 179.012 179.988 180.963 181.939 182.915 183.891 184.867 185.843 186.819
 187.794  188.77 189.746 190.722 191.698 192.674  193.65 194.626 195.601 196.577
 197.553 198.529 199.505 200.481 201.457 202.432 203.388 204.343 205.299 206.254
 207.209 208.165  209.12 210.075 211.031 211.986 212.941 213.897 214.852 215.808
 216.763 217.718 218.674 219.629 220.584  221.54 222.495  223.45 224.435  225.42
 226.405  227.39 228.374 229.359 230.344 231.329 232.313 233.298 234.283 235.268
 236.253 237.237 238.222 239.207 240.192 241.176 242.161 243.146 244.131 245.115
   246.1 247.085  248.07 249.055 250.039 251.024 252.017 253.009 254.002 254.994
 255.987 256.979 257.972 258.964 259.957 260.949 261.942 262.934 263.927 264.919
 265.912 266.905 267.897  268.89 269.882 270.875 271.867  272.86 273.852 274.845
 275.837  276.83 277.822 278.815 279.807   280.8 281.792 282.762 283.733 284.703
 285.673 286.643 287.613 288.583 289.553 290.523 291.493 292.463 293.433 294.404
 295.374 296.344 297.314 298.284 299.254 300.224 301.194 302.164 303.134 304.104
 305.075 306.045 307.015 307.985 308.955 309.925 310.895 311.865 312.861 313.856
 314.852 315.848 316.843 317.839 318.835  319.83 320.826 321.822 322.817 323.813
 324.809 325.804   326.8 327.796 328.791 329.787 330.783 331.778 332.774  333.77
 334.765 335.761 336.757 337.752 338.748 339.744 340.739 341.735 342.731 343.711
 344.692 345.673 346.654 347.635 348.615 349.596 350.577 351.558 352.539  353.52
   354.5 355.481 356.462 357.443 358.424 359.405 360.385 361.366 362.347 363.328
 364.309 365.289  366.27 367.251 368.232 369.213 370.194 371.174 372.155 373.136
 374.117 375.098 376.078 377.059  378.04 379.021 380.006 380.992 381.977 382.962
 383.948 384.933 385.918 386.904 387.889 388.874  389.86 390.845  391.83 392.816
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       0.99871411.9974282.9961423.9948574.9935715.9922856.9909997.9897138.988427
9.98714210.9858611.9845712.98328  13.98214.9807115.9794316.9781417.9768518.97557
19.97428  20.97321.9717122.9704223.9691424.9678525.9665726.9652827.9639928.96271
29.9614230.9601431.9588532.9575733.9562834.9549935.9537136.9524237.9511438.94985
39.9485740.94728  41.94642.9447143.9434244.9421345.9408546.9395647.9382848.93699
49.9357150.9344251.9290752.9237153.91835  54.91355.9076456.9022957.8969358.89158
59.8862260.8808761.8755162.87016 63.864864.8594465.8540966.8487367.8433868.83802
69.8326770.8273271.82196 72.816673.8112574.8058975.8005476.7951877.7898378.78447
79.7791180.77376 81.768482.7630583.7576984.7523385.7469886.7416387.7362788.73092
89.7255690.7202191.71485 92.709593.7041494.6987895.6934396.6880797.6827298.67736
  99.672100.6666101.6613102.6559103.6506104.6452105.6399106.6345107.6292108.6238
109.6185110.6131111.6077112.6024 113.597114.5917115.5863 116.581117.5756118.5703
119.5649120.5595121.5542 122.537123.5197124.5025125.4853126.4681127.4508128.4336
129.4164130.3992131.3819132.3647133.3475134.3303 135.313136.2958137.2786138.2614
139.2441140.2269141.2097142.1925143.1752 144.158145.1408146.1236147.1064148.0891
149.0719150.0547151.0172151.9798152.9424 153.905154.8676155.8301156.7927157.7553
158.7178159.6804 160.643161.6056162.5681163.5307164.4933165.4559166.4184 167.381
168.3436169.3062170.2687171.2313172.1939173.1565174.1323175.1082176.0841177.0599
178.0358179.0117179.9875180.9634181.9392182.9151 183.891184.8668185.8427186.8186
187.7944188.7703189.7462 190.722191.6979192.6738193.6496194.6255195.6013196.5772
197.5531198.5289199.5048200.4807201.4565202.4324203.3878204.3431205.2985206.2539
207.2092208.1646209.1199210.0753211.0307211.9861212.9414213.8968214.8521215.8075
216.7629217.7182218.6736 219.629220.5843221.5397222.4951223.4504224.4352  225.42
226.4047227.3895228.3743229.3591230.3438231.3286232.3134233.2982234.2829235.2677
236.2525237.2372 238.222239.2068240.1916241.1763242.1611243.1459244.1307245.1154
246.1002 247.085248.0697249.0545250.0393251.0241252.0166253.0091254.0016254.9942
255.9867256.9792257.9717258.9643259.9568260.9493261.9418262.9344263.9269264.9194
 265.912266.9045 267.897268.8895 269.882270.8746271.8671272.8596273.8521274.8447
275.8372276.8297277.8222278.8148279.8073280.7998281.7924282.7624283.7325284.7026
285.6727286.6428287.6129 288.583289.5531290.5232291.4933292.4633293.4334294.4035
295.3736296.3437297.3138298.2839 299.254300.2241301.1942302.1642303.1343304.1044
305.0745306.0446307.0147307.9848308.9549 309.925310.8951311.8651312.8608313.8564
314.8521315.8478316.8434317.8391318.8347319.8304 320.826321.8217322.8174 323.813
324.8087325.8044   326.8327.7957328.7913 329.787330.7827331.7783 332.774333.7696
334.7653335.7609336.7566337.7523338.7479339.7436340.7392341.7349342.7305343.7114
344.6922 345.673346.6538347.6346348.6154349.5963350.5771351.5579352.5388353.5196
354.5004355.4812 356.462357.4428358.4237359.4045360.3853361.3661 362.347363.3278
364.3086365.2894366.2702 367.251368.2319369.2127370.1935371.1743372.1552 373.136
374.1168375.0976376.0784377.0592378.0401379.0209380.0062380.9916381.9769382.9623
383.9476 384.933385.9183386.9037 387.889388.8744389.8597390.8451391.8304392.8157
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BR Coef=-1 , 0 , 0 ,, 0 ,,,0.8,-1,,0,
WSPro=,,,, 1 ,,,, 0 ,,,, 0 ,,,,-1 ,-1 ,-1 , 0 , 0 , 0 , 0 , 0
Culvert=1,1.1,,8.2,0.024,0.9,1,2,3,72.206,297,72.22,302,Culvert #1  , 0 ,1
     297     302
BC Culvert Barrel=1,Left,0
Culvert Bottom n=0.024
Culvert=1,1.1,,8.2,0.024,0.9,1,2,3,72.331,299,72.414,304,Culvert #2  , 0 ,1
     299     304
BC Culvert Barrel=1,Right,0
Culvert Bottom n=0.024
Culvert=3,1.1,1.56,8.2,0.024,0.9,1,36,1,72.686,301,72.452,306,Culvert #3  , 0 ,1
     301     306
BC Culvert Barrel=1,Right,0
Culvert Bottom n=0.024
BC Design=,, 0 ,, 0 ,,,,,,
BC Use User HTab Curves=0
BC User HTab FreeFlow(D)= 0

Type RM Length L Ch R = 1 ,4.4012  ,12.49,12.42,12.04
BEGIN DESCRIPTION:
DS of Wigwam Brook Unnamed Road 2 Culvert - WB25 (SEM 2019)
END DESCRIPTION:
XS GIS Cut Line= 6
  591385.2843036 5422613.6763831  591471.5386036 5422678.2348831
  591484.7678036 5422736.4432831  591476.8303036 5422766.6058831
  591438.4198036 5422825.2125831  591414.6072036 5422930.7814831
#Sta/Elev= 30
   51.35   75.08   56.34   75.24   69.31   74.65    73.3   75.19   78.28   74.81
89.25999   75.16   94.25   74.41  103.22   74.58  107.21   73.87  130.16   73.65
  137.14   74.11  151.11   74.19  166.05    73.5  186.95   73.59  203.86   73.22
  207.84   73.44  217.79   73.09  276.55   73.38  284.42   73.12  288.36   73.21
  291.32   74.07  296.56   73.64   299.9   72.64  306.96   72.28  310.45   73.56
     328   74.11  345.87   74.03  372.67   74.54  407.42   76.01  428.27   76.54
#Mann= 3 , 0 , 0
   51.35      .1       0  296.56     .04       0  310.45     .06       0
#XS Ineff= 2 , 0
          291.16   74.05
Permanent Ineff=
       F       F
Bank Sta=296.56,310.45
XS Rating Curve= 0 ,0
Exp/Cntr=0.3,0.1

Type RM Length L Ch R = 1 ,4.3888  ,300.2,320.01,279.72
BEGIN DESCRIPTION:
WB24 (SEM 2019)
END DESCRIPTION:
XS GIS Cut Line= 6
  591383.1676036 5422615.2638831  591463.9798036 5422677.3549831
  591481.0637036 5422736.4432831  591470.5235036 5422766.1174831
  591428.8947036 5422818.8625831  591394.7634036 5422949.8315831
#Sta/Elev= 30
      64   75.25   80.99   74.47   95.97   74.71  100.97   75.57  103.97   75.23
  105.96   74.38  124.95   73.75  155.92   74.17  171.86   73.51  205.59   73.57
  211.55   73.11  235.29    73.4  253.01      73  265.77   73.62  280.73    73.5
  289.71   72.81  298.68   73.08  300.74   72.34  311.35   72.05  315.94   72.25
  317.78   72.94  327.45   74.03   337.4   73.57  345.36   74.07  426.97   74.58
   440.9    74.4  444.88   73.85  447.86   74.39  455.83   77.18   461.8   77.23
#Mann= 3 , 0 , 0
      64      .1       0  298.68     .04       0  317.78     .06       0
#XS Ineff= 2 , 0
                          391.16            74.4
Permanent Ineff=
       F       F
Bank Sta=298.68,317.78
XS Rating Curve= 0 ,0
Exp/Cntr=0.3,0.1

Type RM Length L Ch R = 1 ,4.0688  ,160.35,158.65,149.82
BEGIN DESCRIPTION:
WB23 (SEM 2019)
END DESCRIPTION:
XS GIS Cut Line= 6
  591634.7410036 5422316.7120831  591352.6380036 5422378.7619831
  591304.3762036 5422545.0114831  591263.7944036 5422674.1351831
  591251.8881036 5422708.5310831  591152.6692036 5422916.2293831
#Sta/Elev= 30
  -451.7   75.97 -354.75   76.29 -340.76   75.36 -302.78   75.87  -265.8   74.93
 -229.82   75.77 -206.83   74.84  -90.23   75.83  -49.43   74.64   12.96    74.7
   18.95   75.96   21.94   74.32   55.85   75.14  115.69   73.62  128.65   74.55
  139.62   72.78  160.95   72.22  166.15   70.72  175.02   72.15  279.66   74.32
   322.5   77.05  347.41    76.1   352.4   74.75  373.32   75.33  384.28   78.49
  393.25   75.33  397.24   76.37  403.22   79.74   409.2   76.79  412.18   77.75
#Mann= 3 , 0 , 0
  -451.7     .06       0  160.95     .04       0  175.02     .12       0
#XS Ineff= 2 , 0
           94.88   74.16
Permanent Ineff=
       F       F
Bank Sta=160.95,175.02
XS Rating Curve= 0 ,0
Exp/Cntr=0.3,0.1

Type RM Length L Ch R = 1 ,3.9102  ,152.03,158.66,161.13
BEGIN DESCRIPTION:
WB22 (SEM 2019)
END DESCRIPTION:
XS GIS Cut Line= 4
  591094.4607036 5422508.7702831  591105.0441036 5422686.0414831
  591126.2108036 5422737.6352831  591131.5025036 5422926.8127831
#Sta/Elev= 30
       0   75.57   31.93    74.6   58.86   74.88   61.86   73.72   67.84    73.8
   70.84   74.84  134.69   73.87  142.67   73.29  153.64   73.19  157.63   73.66
  164.62   72.62  179.58   72.44  191.22   71.88  192.84   71.19  197.41   72.05
  208.44   72.06  210.44   71.11  214.92   71.17  215.45   72.06  224.98   72.36
  228.37   73.13  241.32   73.78  284.15   74.61  289.13   74.18     324   75.31
  343.92      75   399.7   75.61  414.64   74.97  418.62   76.12  422.61    78.6
#Mann= 3 , 0 , 0
       0     .06       0  179.58     .04       0  224.98     .06       0
#XS Ineff= 2 , 0
             120   74.01
Permanent Ineff=
       F       F
Bank Sta=179.58,224.98
XS Rating Curve= 0 ,0
Exp/Cntr=0.3,0.1

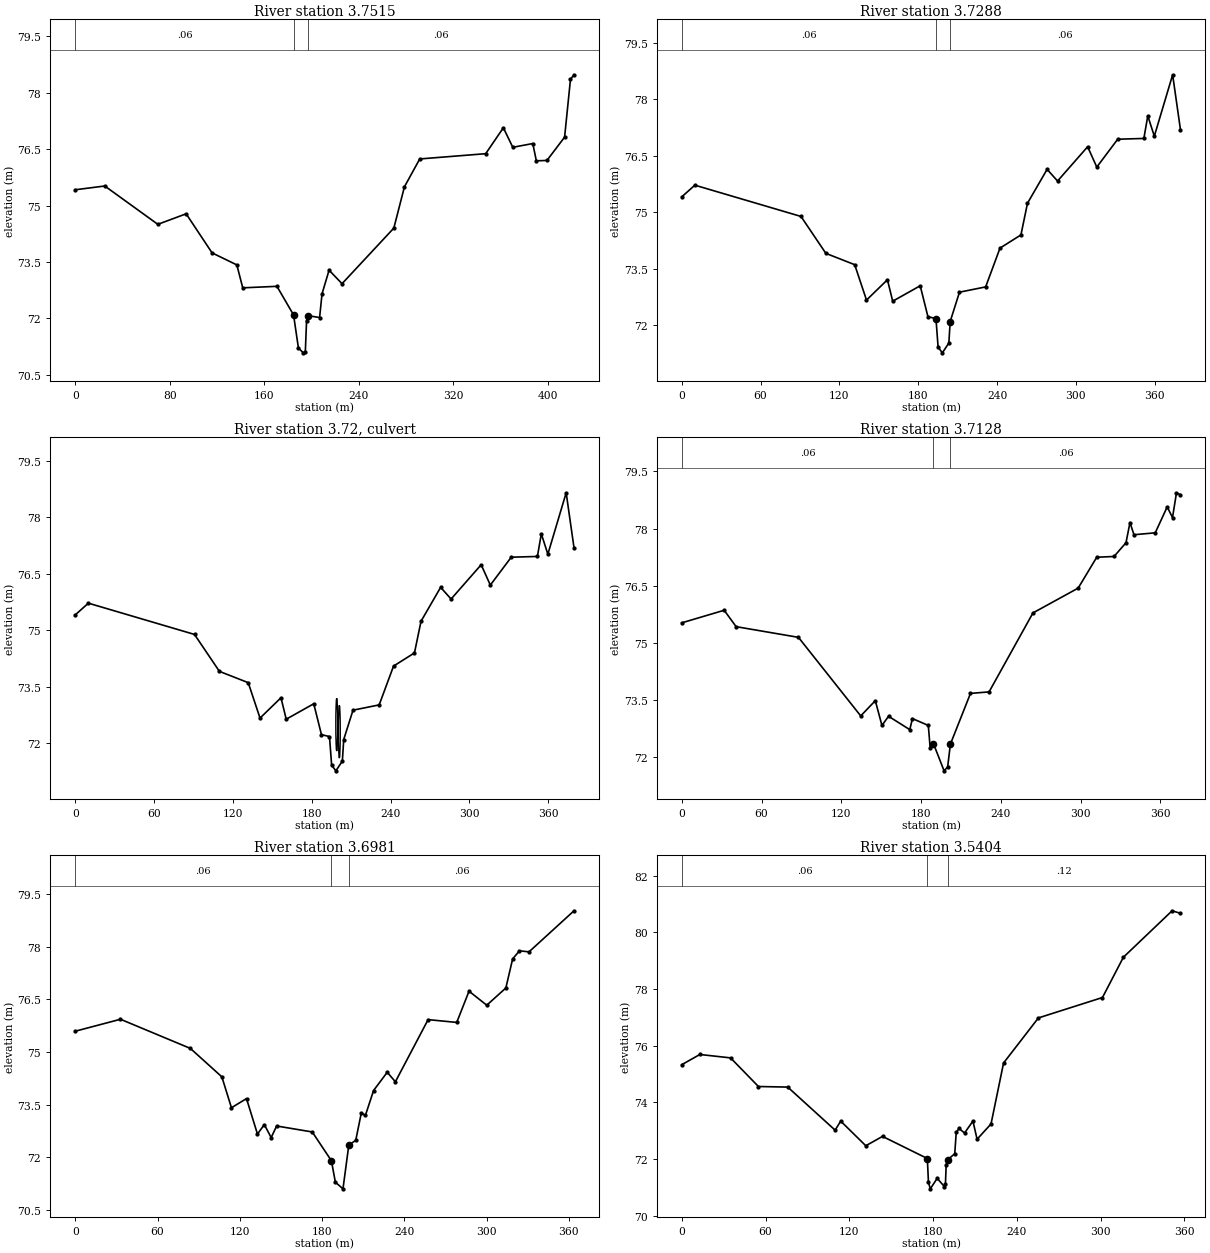
Type RM Length L Ch R = 1 ,3.7515  ,23.1,22.71,16.31
BEGIN DESCRIPTION:
WB21 (SEM 2019)
END DESCRIPTION:
XS GIS Cut Line= 4
590956.8771035985422529.93698309590974.0751035995422705.88518309
590976.7209035985422738.95818309591032.2835035995422944.01068309
#Sta/Elev= 30
       0   75.42   24.97   75.52   69.92    74.5   93.89   74.78  115.86   73.74
  136.83   73.42  141.83   72.81  170.79   72.85  184.86   72.09  188.98   71.21
  193.09   71.08  194.81   71.09   195.9   71.94  196.93   72.07  206.93   72.02
  208.99   72.65  214.95   73.28  225.92   72.92  269.81    74.4  278.79    75.5
  291.75   76.24  347.61   76.38  362.57   77.07  370.55   76.55   387.5   76.65
   390.5   76.19  399.47    76.2  414.43   76.82  419.42   78.36  422.41   78.48
#Mann= 3 , 0 , 0
       0     .06       0  184.86     .04       0  196.93     .06       0
Bank Sta=184.86,196.93
XS Rating Curve= 0 ,0
Exp/Cntr=0.3,0.1

Type RM Length L Ch R = 1 ,3.7288  ,18.18,16.01,15.97
BEGIN DESCRIPTION:
US of Wigwam Brook Unnamed Road 1 Culvert - WB20 (SEM 2019)
END DESCRIPTION:
XS GIS Cut Line= 4
590938.3563035985422536.55158309590956.8771035985422719.11438309
590962.1688035985422749.54158309590982.0126035995422913.58358309
#Sta/Elev= 30
       0   75.41    9.97   75.72   90.75   74.89   109.7   73.91  131.64   73.61
  140.62   72.67  156.57   73.21  160.56   72.64  181.51   73.05  187.38   72.23
  193.49   72.18  195.13   71.42  198.36   71.27   203.3   71.53  204.32    72.1
  211.39   72.88  231.31   73.02  242.25   74.05  258.18    74.4  263.16   75.24
  278.09   76.14  286.05   75.83  308.95   76.74  315.92    76.2  331.84   76.94
  351.75   76.96  354.74   77.56  359.71   77.02  373.65   78.65  379.62   77.19
#Mann= 3 , 0 , 0
       0     .06       0  193.49     .04       0  204.32     .06       0
Bank Sta=193.49,204.32
XS Rating Curve= 0 ,0
Exp/Cntr=0.3,0.1

Type RM Length L Ch R = 2 ,3.72    ,,,
Node Photo=.\Photos\WB-CR-4.JPG
BEGIN DESCRIPTION:
Wigwam Brook Unnamed Road 1 Culvert
END DESCRIPTION:
Node Name=WB-CR-4
Bridge Culvert--1,0,-1,-1, 0
Deck Dist Width WeirC Skew NumUp NumDn MinLoCord MaxHiCord MaxSubmerge Is_Ogee
5.7,5.3,1.4,0, 368, 368, , , 0.98, 0, 3,3,,
      1010.9955111.9910212.9865313.9820314.9775415.9730516.9685617.9640718.95958
19.9550820.95059 21.946122.9416123.9371224.9326325.9281326.9236427.9191528.91466
29.9101730.9056831.9011832.89669 33.892234.8877135.8832236.8787337.8742438.86974
39.8652540.8607641.8562742.8517843.8472944.84279 45.838346.8338147.8293248.82483
49.8203450.8158551.8113552.8068653.8023754.7978855.7933956.78889 57.784458.77991
59.7754260.7709361.7664462.7619463.7574564.7529665.7484766.7439867.7394968.73499
69.7305170.7260171.7215272.7170373.7125474.7080575.7035576.6990777.6945778.69008
79.68559 80.681181.6766182.6721183.6676384.6631385.6586486.6541487.6496688.64516
89.6406790.6361891.63169 92.6272 93.622794.6182295.6137296.6092397.6047498.60025
99.59576100.5913101.5868102.5823103.5778104.5733105.5688106.5643107.5598108.5553
109.5508110.5463111.5419112.5374113.5329114.5284115.5239116.5194117.5149118.5104
119.5059120.5014121.4969122.4924 123.488124.4835 125.479126.4745  127.47128.4655
 129.461130.4565 131.452132.4475 133.443134.4386135.4341136.4296137.4251138.4206
139.4161140.4116141.4071142.4026143.3981144.3936145.3891146.3846147.3802148.3757
149.3712150.3667151.3622152.3577153.3532154.3487155.3442156.3198157.2954 158.271
159.2466160.2222161.1978162.1734 163.149164.1246165.1003166.0759167.0515168.0271
169.0027169.9783170.9539171.9295172.9051173.8807174.8563175.8319176.8075177.7831
178.7587179.7343180.7099181.6855182.6611183.6367184.6123185.5879186.5635187.5391
188.5147189.4903190.4659191.4415192.4171193.3927194.3683195.3076196.2469197.1862
198.1255199.0649206.5793207.5186208.4579209.3972210.3935211.3898212.3861213.3824
214.3787 215.375216.3712217.3675218.3638219.3601220.3564221.3527 222.349223.3452
224.3415225.3378226.3341227.3304228.3267 229.323230.3193231.3156232.3118233.3081
234.3044235.3007 236.297237.2933238.2906239.2878240.2851241.2824242.2797 243.277
244.2742245.2715246.2688247.2661248.2634249.2606250.2579251.2552252.2525253.2498
254.2471255.2443256.2416257.2389258.2362259.2335260.2307 261.228262.2253263.2226
264.2198265.2171266.2144267.2117 268.209269.2063270.2036271.2008272.1981273.1954
274.1927275.1899276.1872277.1845278.1818279.1791280.1764281.1736282.1709283.1682
284.1655285.1628  286.16287.1573288.1546289.1519290.1492291.1465292.1437 293.141
294.1383295.1356296.1328297.1301298.1274299.1247 300.122301.1193302.1165303.1138
304.1111305.1084306.1057307.1029308.1002309.0975310.0948311.0921312.0894313.0866
314.0839315.0812316.0785317.0757 318.073319.0703320.0676321.0649322.0622323.0594
324.0567 325.054326.0513327.0486328.0458329.0431330.0404331.0377 332.035333.0323
334.0295335.0268336.0241337.0214338.0187339.0159340.0132341.0105342.0078343.0051
344.0023344.9996345.9969346.9942347.9915348.9888 349.986350.9833351.9806352.9779
353.9752354.9724355.9697 356.967357.9643358.9616359.9589360.9561361.9534362.9507
 363.948364.9453365.9425366.9398367.9371368.9344369.9317 370.929371.9262372.9235
373.9208374.9181375.9153376.9126377.9099378.9072379.9045380.9018
 75.6629 75.7122 75.7408  75.746 75.7222 75.6896 75.6405 75.6126 75.6011 75.5964
 75.6101 75.6252 75.6327 75.6419 75.6647 75.6925 75.7156 75.7053 75.7251 75.7384
  75.762 75.7741 75.8028 75.8157  75.849 75.8692 75.8634 75.8797 75.8774 75.9229
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       77.9955088.9910169.98652610.9820311.9775412.9730513.9685614.9640715.95958
16.9550817.95059 18.946119.9416120.9371221.9326322.9281323.9236424.9191525.91466
26.9101727.9056828.9011829.89669 30.892231.8877132.8832233.8787334.8742435.86974
36.8652537.8607638.8562739.8517840.8472941.84279 42.838343.8338144.8293245.82483
46.8203447.8158548.8113549.8068650.8023751.7978852.7933953.78889 54.784455.77991
56.7754257.7709358.7664459.7619460.7574561.7529662.7484763.7439864.7394965.73499
66.7305167.7260168.7215269.7170370.7125471.7080572.7035573.6990774.6945775.69008
76.68559 77.681178.6766179.6721180.6676381.6631382.6586483.6541484.6496685.64516
86.6406787.6361888.63169 89.6272 90.622791.6182292.6137293.6092394.6047495.60025
96.5957697.5912698.5867899.58228100.5778101.5733102.5688103.5643104.5598105.5553
106.5508107.5463108.5419109.5374110.5329111.5284112.5239113.5194114.5149115.5104
116.5059117.5014118.4969119.4924 120.488121.4835 122.479123.4745  124.47125.4655
 126.461127.4565 128.452129.4475 130.443131.4386132.4341133.4296134.4251135.4206
136.4161137.4116138.4071139.4026140.3981141.3936142.3891143.3846144.3802145.3757
146.3712147.3667148.3622149.3577150.3532151.3487152.3442153.3198154.2954 155.271
156.2466157.2222158.1978159.1734 160.149161.1246162.1003163.0759164.0515165.0271
166.0027166.9783167.9539168.9295169.9051170.8807171.8563172.8319173.8075174.7831
175.7587176.7343177.7099178.6855179.6611180.6367181.6123182.5879183.5635184.5391
185.5147186.4903187.4659188.4415189.4171190.3927191.3683192.3076193.2469194.1862
195.1255196.0649203.5793204.5186205.4579206.3972207.3935208.3898209.3861210.3824
211.3787 212.375213.3712214.3675215.3638216.3601217.3564218.3527 219.349220.3452
221.3415222.3378223.3341224.3304225.3267 226.323227.3193228.3156229.3118230.3081
231.3044232.3007 233.297234.2933235.2906236.2878237.2851238.2824239.2797 240.277
241.2742242.2715243.2688244.2661245.2634246.2606247.2579248.2552249.2525250.2498
251.2471252.2443253.2416254.2389255.2362256.2335257.2307 258.228259.2253260.2226
261.2198262.2171263.2144264.2117 265.209266.2063267.2036268.2008269.1981270.1954
271.1927272.1899273.1872274.1845275.1818276.1791277.1764278.1736279.1709280.1682
281.1655282.1628  283.16284.1573285.1546286.1519287.1492288.1465289.1437 290.141
291.1383292.1356293.1328294.1301295.1274296.1247 297.122298.1193299.1165300.1138
301.1111302.1084303.1057304.1029305.1002306.0975307.0948308.0921309.0894310.0866
311.0839312.0812313.0785314.0757 315.073316.0703317.0676318.0649319.0622320.0594
321.0567 322.054323.0513324.0486325.0458326.0431327.0404328.0377 329.035330.0323
331.0295332.0268333.0241334.0214335.0187336.0159337.0132338.0105339.0078340.0051
341.0023341.9996342.9969343.9942344.9915345.9888 346.986347.9833348.9806349.9779
350.9752351.9724352.9697 353.967354.9643355.9616356.9589357.9561358.9534359.9507
 360.948361.9453362.9425363.9398364.9371365.9344366.9317 367.929368.9262369.9235
370.9208371.9181372.9153373.9126374.9099375.9072376.9045377.9018
 75.6629 75.7122 75.7408  75.746 75.7222 75.6896 75.6405 75.6126 75.6011 75.5964
 75.6101 75.6252 75.6327 75.6419 75.6647 75.6925 75.7156 75.7053 75.7251 75.7384
  75.762 75.7741 75.8028 75.8157  75.849 75.8692 75.8634 75.8797 75.8774 75.9229
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BR Coef=-1 , 0 , 0 ,, 0 ,,,0.8,-1,,0,
WSPro=,,,, 1 ,,,, 0 ,,,, 0 ,,,,-1 ,-1 ,-1 , 0 , 0 , 0 , 0 , 0
Culvert=1,1.4,,5.8,0.024,0.9,1,2,3,71.795,199,71.944,195.5,Culvert #1  , 0 ,5.4
     199   195.5
BC Culvert Barrel=1,1,0
Culvert Bottom n=0.024
Culvert=1,1.4,,5.8,0.024,0.9,1,2,3,71.608,201,71.757,197.5,Culvert #2  , 0 ,5.4
     201   197.5
BC Culvert Barrel=1,1,0
Culvert Bottom n=0.024
BC Design=,, 0 ,, 0 ,,,,,,
BC Use User HTab Curves=0
BC User HTab FreeFlow(D)= 0

Type RM Length L Ch R = 1 ,3.7128  ,13.72,14.64,15.37
BEGIN DESCRIPTION:
DS of Wigwam Brook Unnamed Road 1 Culvert - WB19 (SEM 2019)
END DESCRIPTION:
XS GIS Cut Line= 4
590919.8354035985422543.16618309590941.0021035985422724.40608309
590946.2938035985422749.54158309590955.5542035985422916.22938309
#Sta/Elev= 30
       0   75.53   31.91   75.86   40.88   75.43   87.75   75.15  134.61   73.09
  145.58   73.49  150.56   72.84  155.55   73.08   171.5   72.73   173.5   73.02
  185.44   72.84  186.82   72.26  189.34   72.36   197.3   71.65  199.98   71.75
  202.05   72.35  217.16   73.68  231.15   73.72  264.14   75.79  298.13   76.44
  312.12   77.25  325.12   77.27  334.12   77.63  337.12   78.16  340.11   77.84
  356.11   77.89  365.11   78.57   369.1   78.29   372.1   78.94   375.1   78.89
#Mann= 3 , 0 , 0
       0     .06       0  189.34     .04       0  202.05     .06       0
Bank Sta=189.34,202.05
XS Rating Curve= 0 ,0
Exp/Cntr=0.3,0.1

Type RM Length L Ch R = 1 ,3.6981  ,157.28,157.73,165.49
BEGIN DESCRIPTION:
WB18 (SEM 2019)
END DESCRIPTION:
XS GIS Cut Line= 4
590909.2520035985422548.45778309590930.4187035985422727.05198309
590930.4187035985422754.83328309590934.3875035985422910.93768309
#Sta/Elev= 30
       0   75.59   32.97   75.93   83.93    75.1  106.91   74.29   113.9   73.41
  124.89   73.67  132.88   72.66  137.88   72.93  142.88   72.56  146.87   72.89
  172.85   72.72  186.83    71.9   189.7   71.29  195.26    71.1  199.52   72.35
  204.56   72.48  208.62   73.26   211.6   73.19  217.57    73.9  227.52   74.42
  233.49   74.15  257.36   75.92  278.24   75.84   287.2   76.73  300.13   76.33
  314.05   76.82  319.02   77.65     324   77.88  330.96   77.85  363.78   79.02
#Mann= 3 , 0 , 0
       0     .06       0  186.83     .04       0  199.52     .06       0
Bank Sta=186.83,199.52
XS Rating Curve= 0 ,0
Exp/Cntr=0.3,0.1

Type RM Length L Ch R = 1 ,3.5404  ,121.5,126.8,133.44
BEGIN DESCRIPTION:
WB17 (SEM 2019)
END DESCRIPTION:
XS GIS Cut Line= 4
590762.4080035985422565.65578309590774.3143035985422731.02068309
590779.6059035985422765.41658309590792.8351035985422921.52108309
#Sta/Elev= 30
       0   75.33   12.98   75.69   34.96   75.57   54.93   74.56   75.91   74.54
  109.86   73.02  113.86   73.34  131.84   72.47  143.82    72.8  175.92   72.02
  176.72   71.18  178.04   70.95  182.98   71.32  188.12   71.03  188.89   71.12
  189.42    71.8  190.59   71.98  195.56   72.19  196.62   72.94  198.61   73.08
  202.59   72.92  208.58   73.34  211.57    72.7  221.55   73.24  230.53   75.39
  255.48   76.98  301.38    77.7  316.35   79.12  351.27   80.76  357.26   80.67
#Mann= 3 , 0 , 0
       0     .06       0  175.92     .04       0  190.59     .12       0
Bank Sta=175.92,190.59
XS Rating Curve= 0 ,0
Exp/Cntr=0.3,0.1

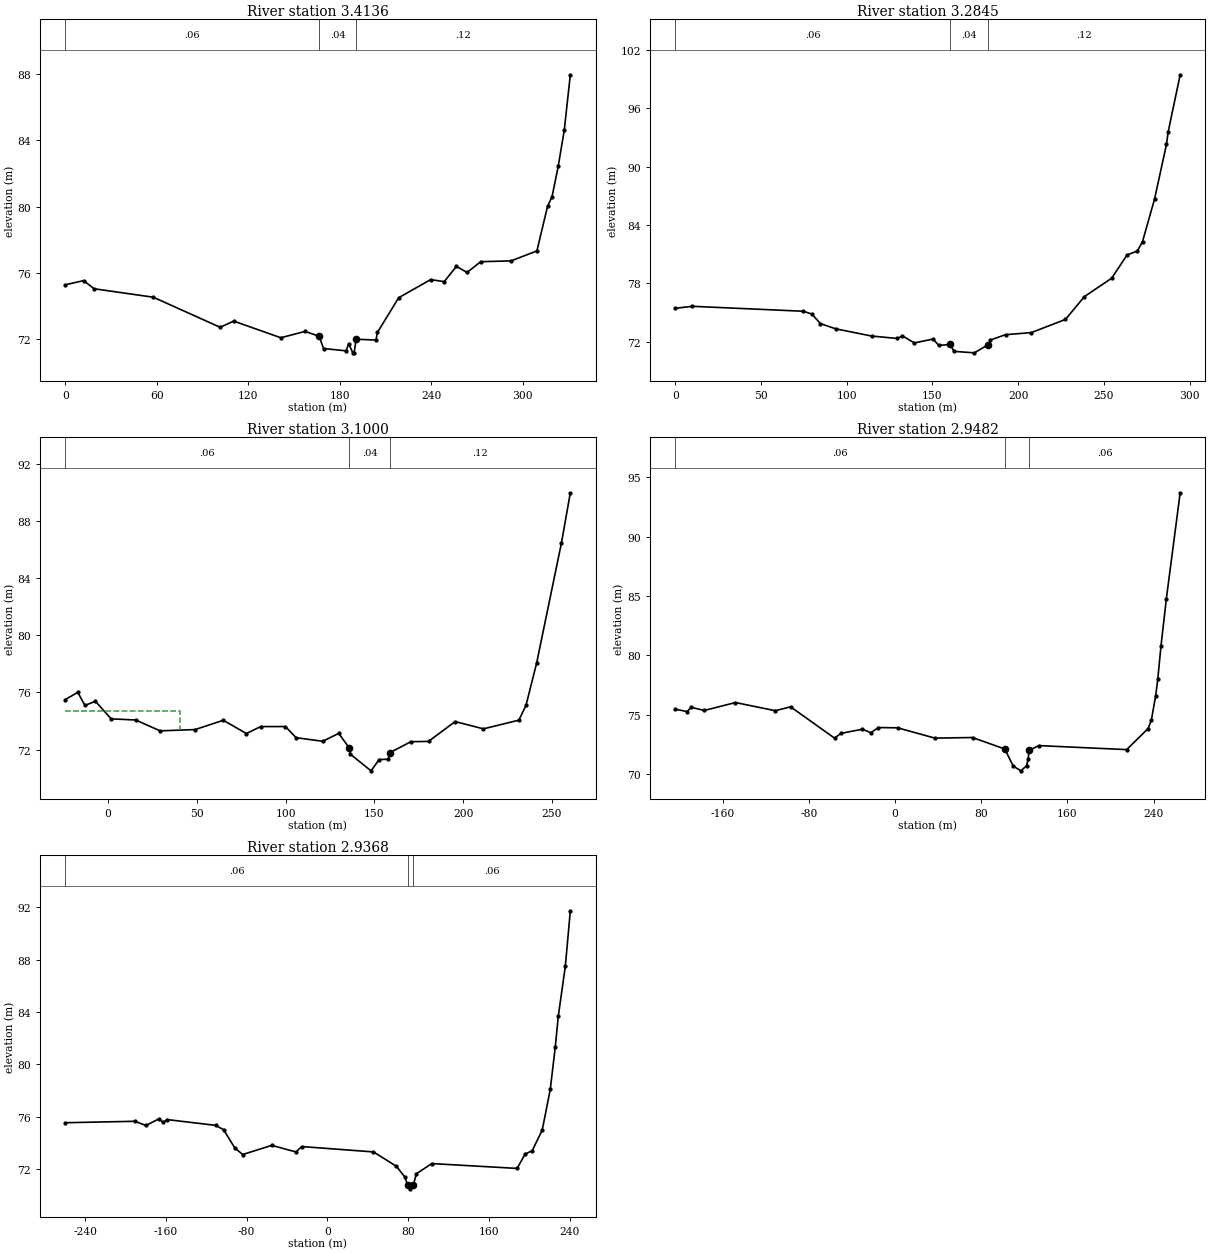
Type RM Length L Ch R = 1 ,3.4136  ,133.84,129.09,137.3
BEGIN DESCRIPTION:
WB16 (SEM 2019)
END DESCRIPTION:
XS GIS Cut Line= 4
590717.4287035995422565.65578309590672.4495035985422720.43738309
590655.2515035985422761.44788309590587.7826035985422867.28138309
#Sta/Elev= 30
       0   75.29   11.94   75.54    18.9   75.05   57.71   74.54  101.49   72.73
  110.44    73.1  141.29    72.1   157.2   72.48  166.44   72.19  169.33   71.45
   184.1   71.31  185.85   71.74  188.52   71.19  189.42   71.21  190.72   72.01
  203.71   71.96  204.67   72.42   218.6   74.51  239.52    75.6  248.49   75.48
  256.46    76.4  263.43   76.03  272.39   76.68  292.32   76.73  309.25   77.33
  316.22   80.01  319.21    80.6   323.2   82.42  327.18   84.59  331.17   87.94
#Mann= 3 , 0 , 0
       0     .06       0  166.44     .04       0  190.72     .12       0
Bank Sta=166.44,190.72
XS Rating Curve= 0 ,0
Exp/Cntr=0.3,0.1

Type RM Length L Ch R = 1 ,3.2845  ,198.86,184.52,186.3
BEGIN DESCRIPTION:
WB15 (SEM 2019)
END DESCRIPTION:
XS GIS Cut Line= 4
590640.6994035985422533.90568309590581.1681035985422668.84348309
590553.3867035985422699.27058309590489.8866035985422783.93748309
#Sta/Elev= 30
       0   75.42    9.97   75.63   74.74   75.12   79.72   74.83    84.7   73.85
   93.67   73.31   114.6   72.57  129.55   72.32  132.54   72.58  139.51   71.86
  150.43   72.26  153.73    71.6  160.27    71.7  162.66   70.99  174.49   70.84
  182.16   71.64  183.24   71.67  183.78   72.16  192.68   72.71  207.66   72.92
  227.63   74.28  238.61   76.62  254.58   78.52  263.57   80.92  269.56   81.32
  272.56   82.29  279.55   86.65  286.53   92.29  287.53   93.59  294.52   99.46
#Mann= 3 , 0 , 0
       0     .06       0  160.27     .04       0  182.16     .12       0
Bank Sta=160.27,182.16
XS Rating Curve= 0 ,0
Exp/Cntr=0.3,0.1

Type RM Length L Ch R = 1 ,3.1000  ,153.28,151.77,165.48
BEGIN DESCRIPTION:
WB14 (SEM 2019)
END DESCRIPTION:
XS GIS Cut Line= 6
  590551.3810036 5422516.8028831  590476.5950036 5422510.7851831
  590435.6469036 5422582.8536831  590421.0948036 5422602.6974831
  590376.1156036 5422693.9789831  590376.1068036 5422693.9969831
#Sta/Elev= 30
     -24    75.5     -17   76.01     -13   75.09   -7.08   75.38    1.79   74.15
   15.57   74.07   29.36   73.31   49.06    73.4   64.95   74.05   77.94   73.12
   85.93   73.61   99.92   73.61  105.92   72.83  120.91   72.58   129.9   73.13
  135.86   72.11  136.43   71.68  148.08   70.51  152.67    71.3  157.85   71.32
   158.5   71.77  170.48   72.55  180.45   72.57  195.42   73.96  211.38   73.45
  231.33   74.06  235.32   75.09  241.31   78.05  255.28   86.46  260.29   89.98
#Mann= 3 , 0 , 0
     -24     .06       0  135.86     .04       0   158.5     .12       0
#XS Ineff= 2 , 0
           40.47    74.7
Permanent Ineff=
       F       F
Bank Sta=135.86,158.5
XS Rating Curve= 0 ,0
Exp/Cntr=0.3,0.1

Type RM Length L Ch R = 1 ,2.9482  ,12.43,11.43,11.04
BEGIN DESCRIPTION:
WB13 (SEM 2019)
END DESCRIPTION:
XS GIS Cut Line= 6
  590641.2849036 5422521.3085831  590468.2201036 5422508.6172831
  590435.8351036 5422512.7389831  590336.4280036 5422512.7389831
  590309.9696036 5422499.5097831  590193.6226036 5422564.2939831
#Sta/Elev= 30
    -204   75.45 -193.01   75.25 -189.01   75.61 -177.03   75.34 -148.05   76.01
 -111.09   75.32  -96.93   75.65  -56.14   73.01  -50.17   73.41  -30.27   73.76
  -22.36   73.46  -15.43    73.92.379997   73.88   36.95   73.01    71.9   73.06
  101.86   72.09  109.67   70.65  116.89   70.25  122.02   70.68  123.59   71.25
  124.35   71.97  133.43   72.38  214.97   72.04  234.86   73.82  237.85   74.51
  241.82   76.55  243.81   77.96  246.79   80.76  251.77   84.75  264.61    93.7
#Mann= 3 , 0 , 0
    -204     .06       0  101.86     .04       0  124.35     .06       0
Bank Sta=101.86,124.35
XS Rating Curve= 0 ,0
Exp/Cntr=0.3,0.1

Type RM Length L Ch R = 1 ,2.9368  ,13.02,12.9,12.85
BEGIN DESCRIPTION:
US of Red Cliff Road Bridge - WB12 (SEM 2019)
END DESCRIPTION:
XS GIS Cut Line= 6
  590669.1526036 5422517.8957831  590539.6578036 5422511.5540831
  590407.6602036 5422505.0897831  590338.2139036 5422498.4514831
  590313.8722036 5422492.6306831  590185.3024036 5422555.5927831
#Sta/Elev= 30
  -259.5   75.54 -190.69   75.65 -179.72   75.33 -166.75   75.84 -162.76   75.57
 -158.77   75.78 -110.77   75.34 -102.82   75.01  -91.89   73.63-83.9399   73.11
  -55.13   73.81-31.2799   73.31-25.3199   73.72   45.56   73.31   68.33   72.21
   76.97   71.36   79.28   70.77   81.33   70.49   85.07   70.78   88.05   71.64
  103.29   72.42   187.8   72.05  195.76   73.15  202.72    73.4  212.66   74.98
  220.62   78.09  225.59   81.33  228.57   83.68  235.53   87.49  240.48   91.73
#Mann= 3 , 0 , 0
  -259.5     .06       0   79.28     .04       0   85.07     .06       0
Bank Sta=79.28,85.07
XS Rating Curve= 0 ,0
Exp/Cntr=0.3,0.1

Type RM Length L Ch R = 3 ,2.928   ,,,
Node Photo=.\Photos\WB-CR-3.JPG
BEGIN DESCRIPTION:
Red Cliff Road Bridge
END DESCRIPTION:
Node Name=WB-CR-3
Bridge Culvert--1,0,-1,-1, 0
Deck Dist Width WeirC Skew NumUp NumDn MinLoCord MaxHiCord MaxSubmerge Is_Ogee
5.8,6.6,1.4,0, 400, 400, , , 0.98, 0, 3,3,,
    -129-128.005 -127.01 -125.02 -123.03-122.035 -121.04-120.045 -119.05 -117.06
-116.065 -115.07-114.076-113.081-112.086-110.096-109.101-105.121-102.136-101.141
 -97.161 -95.171 -94.176 -93.181 -92.186 -91.191 -89.201 -87.211 -86.216 -83.231
 -82.237 -81.242 -79.252 -78.257 -76.267 -73.282 -71.292 -69.302 -68.307 -66.317
 -63.332 -61.342 -58.357 -57.362 -55.372 -53.382 -52.387 -51.392 -49.403 -48.408
 -45.423 -42.438 -39.453 -38.458 -36.468 -34.478 -32.488 -29.503 -27.513 -24.528
 -23.533 -22.538 -20.549 -19.554 -18.559 -17.564 -13.584 -12.589 -10.599  -8.609
  -3.634  -1.644   -.649   1.341   2.336   5.321   6.316   7.311   9.301  10.296
  11.291  13.281  14.275   17.26   19.25  20.245  22.235  24.225   25.22  28.205
  30.195   31.19  32.185   33.18  36.141  37.128  38.114  40.088  42.062   46.01
  47.984  49.958  54.892  57.853   58.84  61.801  62.788  64.761  65.748  67.722
  68.709  72.657  73.644  75.618  76.605  77.591  78.578  79.565  80.552  81.539
  83.513    84.5  85.487  86.191  88.448  89.435  91.408  93.382  94.369  95.356
   97.33 100.291 101.278 103.253 105.231 108.198 109.187 111.165 113.143 115.121
 118.088 119.077 120.066 122.044 124.022     126 127.978 130.945 131.934 133.912
  135.89 138.856 140.834 143.801 145.779 146.768 149.735 153.691 155.669 157.647
 158.636 159.625 160.614 162.592  164.57 165.559 168.526 170.504 172.482 174.459
 176.437 178.417 181.387 182.378 183.368 186.339 187.329  189.31  192.28 194.261
 196.241 199.212 201.193 203.173 206.144 207.134 208.125 209.115 210.105 211.095
 212.086 214.066 216.047 218.027 219.018 221.988 223.969  227.93  228.92 230.901
 233.872 234.862 235.852 236.842 238.823 239.813 241.794 242.785 244.766 246.748
  248.73  249.72 250.711 252.693 253.684 255.665 256.656 257.647 260.619 262.601
 264.582 268.545 271.518 273.499  274.49 277.462 279.444 281.425 282.416 283.407
 285.389  287.37 288.361 292.324 294.306 295.296 297.278  300.25 301.241 303.223
 306.195 308.176 309.167 311.149  312.14  313.13 314.121 316.103 317.093 321.057
 323.038 324.029 327.992 329.974 331.955 333.937 334.928 336.909 338.891 340.872
 342.854 343.845 345.828  347.81 350.783 352.765 354.747 355.738 358.712 360.694
 362.676 363.667  366.64 368.622 369.613 372.587 373.578  375.56 376.551 377.542
 378.533 382.497 385.471 386.462 387.453 388.444 390.426 391.417 393.399 395.381
 396.373 399.346 400.337 402.319 404.301 407.274 409.257 413.221 414.212 417.185
 418.176 419.167 420.158 421.149 424.123 426.105 429.078  431.06 433.042 436.016
 437.007 438.989 440.971 442.953 444.935 446.917 448.899  449.89 451.872 452.863
 456.826 459.799  460.79 462.772 463.763 465.745 466.736 468.718 469.709 472.681
 473.672 476.645 477.636 479.618   481.6 482.591 485.564 489.527 490.518 491.509
 493.491 494.482 495.473 496.464 497.455 499.437 500.428  502.41 504.392 506.373
 508.355 510.337 511.328 514.301 515.292 517.274 518.265 522.228 525.201 527.177
 528.165 529.153 531.129 534.092  535.08 537.056 538.044  540.02 541.008 541.996
 543.972 544.959 546.935 549.899 550.887 552.863 555.826 557.802 559.778  563.73
 565.706 566.693 567.681 571.633 572.621 573.609 574.597 575.585  577.56 580.524
 583.488 584.476  587.44 592.379 595.343 597.319 598.307 599.294  601.27 602.258
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                                          72.257  72.258   72.26  72.261  72.263
  72.265  72.267  72.268  72.269
     -31 -30.005  -29.01-27.0201-25.0301-24.0352-23.0402-22.0452-21.0503-19.0603
-18.0654-17.0704-16.0754-15.0805-14.0855-12.0956-11.1006-7.12076-4.13586-3.14089
  .83898 2.82892 3.82389 4.81886 5.81382 6.80879 8.7987310.7886711.7836314.76854
 15.763516.7584718.7484119.7433821.7333124.7182226.7081628.6980929.6930631.68299
 34.667936.6578439.6427440.6377142.6276544.6175845.6125546.6075248.5974649.59242
52.5773355.5622358.5471359.5421161.5320463.5219865.5119268.49682 70.4868 73.4717
 74.4666 75.4616 77.4515 78.4465 79.4415 80.4364 84.4163 85.4113 87.4012 89.3912
  94.366 96.3559 97.3509 99.3408100.3358103.3207104.3157105.3106107.3006108.2955
109.2905111.2805112.2754115.2603117.2503118.2452120.2352122.2251123.2201 126.205
128.1949129.1899130.1848131.1798134.1406135.1275136.1144138.0883140.0621144.0098
145.9837147.9575152.8921155.8529156.8398159.8006160.7875162.7614163.7483165.7222
166.7091170.6568171.6437173.6175174.6045175.5914176.5783177.5652178.5522179.5391
181.5129182.4998183.4868184.1914186.4476187.4345189.4083191.3822192.3691 193.356
195.3299198.2906199.2776201.2534203.2314206.1983207.1873209.1652211.1432213.1211
 216.088 217.077 218.066220.0439222.0219223.9998225.9778228.9447229.9336231.9116
233.8895236.8564238.8344241.8013243.7792244.7682247.7351 251.691 253.669255.6469
256.6359257.6248258.6138260.5918262.5697263.5587266.5256268.5035270.4815272.4594
274.4374276.4166279.3874280.3777 281.368284.3387 285.329287.3095290.2803292.2609
294.2414297.2122299.1927301.1732 304.144305.1343306.1246307.1148308.1051309.0954
310.0856312.0662314.0467316.0272317.0175319.9883321.9688325.9299326.9201328.9007
331.8715332.8617 333.852334.8423336.8228 337.813339.7941340.7849342.7664 344.748
346.7296347.7203348.7111350.6927351.6835 353.665354.6558355.6466358.6189360.6005
362.5821366.5452369.5175371.4991372.4899375.4622377.4438379.4254380.4161381.4069
383.3885  385.37386.3608390.3239392.3055393.2963395.2778398.2502 399.241401.2225
404.1949406.1764407.1672409.1488410.1396411.1303412.1211414.1027415.0934419.0566
421.0381422.0289 425.992427.9736429.9552431.9367432.9275434.9091436.8906438.8722
440.8543441.8454443.8276445.8097 448.783450.7651452.7473453.7383456.7116458.6937
460.6759 461.667464.6402466.6223467.6134470.5866471.5777473.5599 474.551 475.542
476.5331480.4974483.4706484.4617485.4528486.4438 488.426489.4171491.3993493.3814
494.3725497.3457498.3368 500.319502.3011505.2744507.2565511.2208512.2119515.1851
516.1762517.1672518.1583519.1494522.1226524.1048 527.078529.0602531.0424534.0156
535.0067536.9888538.9709540.9531 542.935544.9169546.8987547.8897549.8716550.8625
554.8263557.7991  558.79560.7719561.7629563.7448564.7357566.7176567.7085570.6813
571.6723574.6451 575.636577.6179579.5998580.5908583.5636587.5273588.5183589.5092
591.4911592.4821 593.473594.4639595.4549597.4368598.4277600.4096602.3915604.3734
606.3552608.3371609.3281612.3009613.2918615.2737616.2646620.2284623.2012625.1771
 626.165627.1529629.1287632.0924633.0803635.0562636.0441638.0199639.0078639.9957
641.9715642.9594644.9352647.8989648.8868650.8627653.8264655.8022 657.778661.7297
663.7055664.6934665.6813669.6329670.6208671.6088672.5967673.5846675.5604678.5241
681.4879682.4758685.4395 690.379693.3428695.3186696.3065697.2944699.2702700.2581
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                                          72.27372.2677272.2624472.2571672.25188
72.2413372.2360572.23077  72.227
BR Coef=-1 , 0 , 0 ,, 0 ,,,0.8,-1,,0,
WSPro=,,,, 1 ,,,, 0 ,,,, 0 ,,,,-1 ,-1 ,-1 , 0 , 0 , 0 , 0 , 0
BC Design=,, 0 ,, 0 ,,,,,,
BC Use User HTab Curves=0
BC User HTab FreeFlow(D)= 0

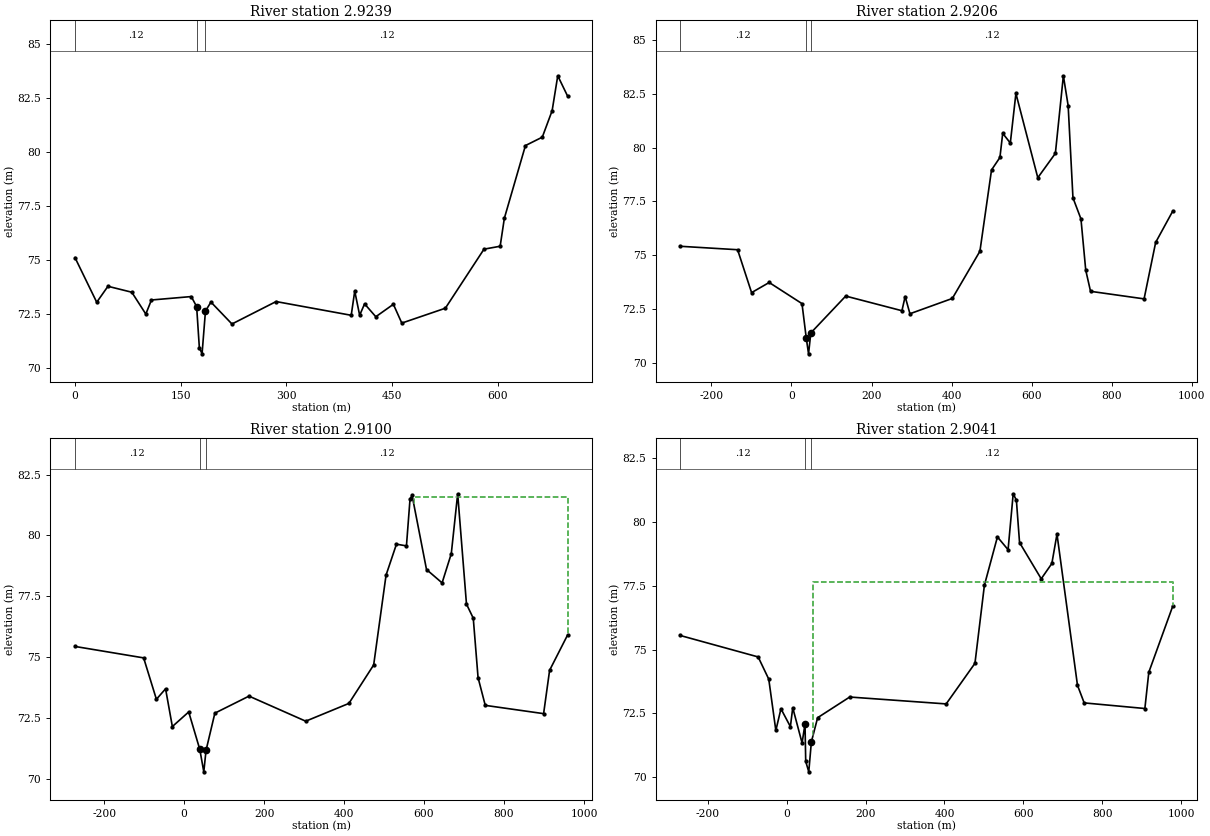
Type RM Length L Ch R = 1 ,2.9239  ,3.19,3.35,3.48
BEGIN DESCRIPTION:
DS of Red Cliff Road Bridge - WB11 (SEM 2019)
END DESCRIPTION:
XS GIS Cut Line= 6
      590508.074       5422508.2       590347.18     5422487.729
      590341.894     5422485.805      590319.155     5422480.989
      590211.251     5422440.453      589827.457     5422354.741
#Sta/Elev= 30
       0 75.121730.87247 73.055246.80664 73.794180.66676 73.5194100.5845 72.5095
108.5516   73.16165.1166 73.3189172.7254 72.8548176.5827 70.9573  180.44  70.669
185.2616 72.6486193.0373  73.064222.8843 72.0503285.5631 73.0877392.2387 72.4523
 397.226 73.5719404.2084 72.4542411.1907 72.9809427.1502 72.3859452.0871 72.9615
464.0567 72.0915   525.9 72.7797 580.761 75.5117603.7029 75.6468609.6877 76.9436
639.6119 80.3048663.5513 80.6938677.5159 81.9188685.4957 83.5333699.4603 82.5932
#Mann= 3 , 0 , 0
       0     .12       0172.7254     .04       0185.2616     .12       0
Bank Sta=172.7254,185.2616
XS Rating Curve= 0 ,0
Exp/Cntr=0.3,0.1

Type RM Length L Ch R = 1 ,2.9206  ,11.42,10.57,10.27
BEGIN DESCRIPTION:
WB10 (SEM 2019)
END DESCRIPTION:
XS GIS Cut Line= 6
  590650.0302036 5422516.7240831  590532.1086036 5422510.9855831
  590348.0018036 5422485.0534831  590319.6697036 5422477.3395831
  590210.8194036 5422433.2316831  589449.2830036 5422263.6404831
#Sta/Elev= 30
    -278   75.42  -134.7   75.26  -99.72   73.27  -55.74   73.74   26.23   72.76
   37.01   71.15   42.62   70.43   48.31    71.4  135.49   73.11  276.01   72.43
  284.01   73.09     296   72.29  401.93      73  470.89   75.19  499.87   78.96
  520.86   79.54  527.85   80.66  546.84   80.21  560.83   82.51  615.51    78.6
  659.45   79.73  679.42   83.33   691.4   81.94  703.38   77.67  723.36   76.69
  735.34   74.31747.3199   73.33  881.12   72.98  910.08    75.6  953.02   77.06
#Mann= 3 , 0 , 0
    -278     .12       0   37.01     .04       0   48.31     .12       0
Bank Sta=37.01,48.31
XS Rating Curve= 0 ,0
Exp/Cntr=0.3,0.1

Type RM Length L Ch R = 1 ,2.9100  ,6.45,5.87,5.76
BEGIN DESCRIPTION:
WB09 (SEM 2019)
END DESCRIPTION:
XS GIS Cut Line= 6
  590648.6941036 5422516.4528831  590521.9268036 5422509.3094831
  590352.4752036 5422476.6257831  590346.5250036 5422472.0478831
  590213.0294036 5422429.9065831  589447.7962036 5422256.3276831
#Sta/Elev= 30
    -273   75.44  -101.3   74.97  -69.38   73.27  -46.43    73.7  -29.48   72.15
   11.42   72.75   39.18   71.21   49.16   70.29   54.76   71.17   76.84    72.7
  162.26    73.4   304.1   72.37  412.05    73.1  474.03   74.68  505.01   78.37
     531   79.64  555.99   79.57  564.99    81.5  570.18   81.64  606.17    78.6
  645.15   78.05  668.15   79.25  684.14   81.71  706.13   77.18  723.12    76.6
  735.12   74.16  753.11   73.02  899.05   72.68  914.05   74.46  959.03   75.91
#Mann= 3 , 0 , 0
    -273     .12       0   39.18     .04       0   54.76     .12       0
#XS Ineff= 2 , 0
                          574.43           81.56
Permanent Ineff=
       F       F
Bank Sta=39.18,54.76
XS Rating Curve= 0 ,0
Exp/Cntr=0.3,0.1

Type RM Length L Ch R = 1 ,2.9041  ,13.33,14.47,17.38
BEGIN DESCRIPTION:
US of Wigwam Brook Newfoundland T'Railway Bridge - WB08 (SEM 2019)
END DESCRIPTION:
XS GIS Cut Line= 6
  590646.3657036 5422515.8178831  590533.9890036 5422510.6247831
  590351.8677036 5422473.6902831  590340.4660036 5422464.5336831
  590214.6409036 5422427.7535831  589430.5459036 5422246.9117831
#Sta/Elev= 30
    -270   75.55  -72.46   74.71  -45.54   73.84   -27.6   71.83  -14.64   72.68
9.289993   71.98   15.27   72.72   38.95   71.34   46.36   72.09   48.16   70.62
   55.91   70.21   62.47   71.38   78.35   72.33  159.71   73.14   404.3   72.87
  477.29   74.46  501.28   77.52  534.28   79.41  561.28   78.91  574.27    81.1
  582.36   80.85  590.36   79.19  645.32   77.77   672.3   78.37   685.3   79.52
  737.26    73.6  754.25   72.91  908.15   72.69  918.14   74.11   979.1   76.71
#Mann= 3 , 0 , 0
    -270     .12       0   46.36     .04       0   62.47     .12       0
#XS Ineff= 2 , 0
                           66.67           77.65
Permanent Ineff=
       F       F
Bank Sta=46.36,62.47
XS Rating Curve= 0 ,0
Exp/Cntr=0.3,0.1