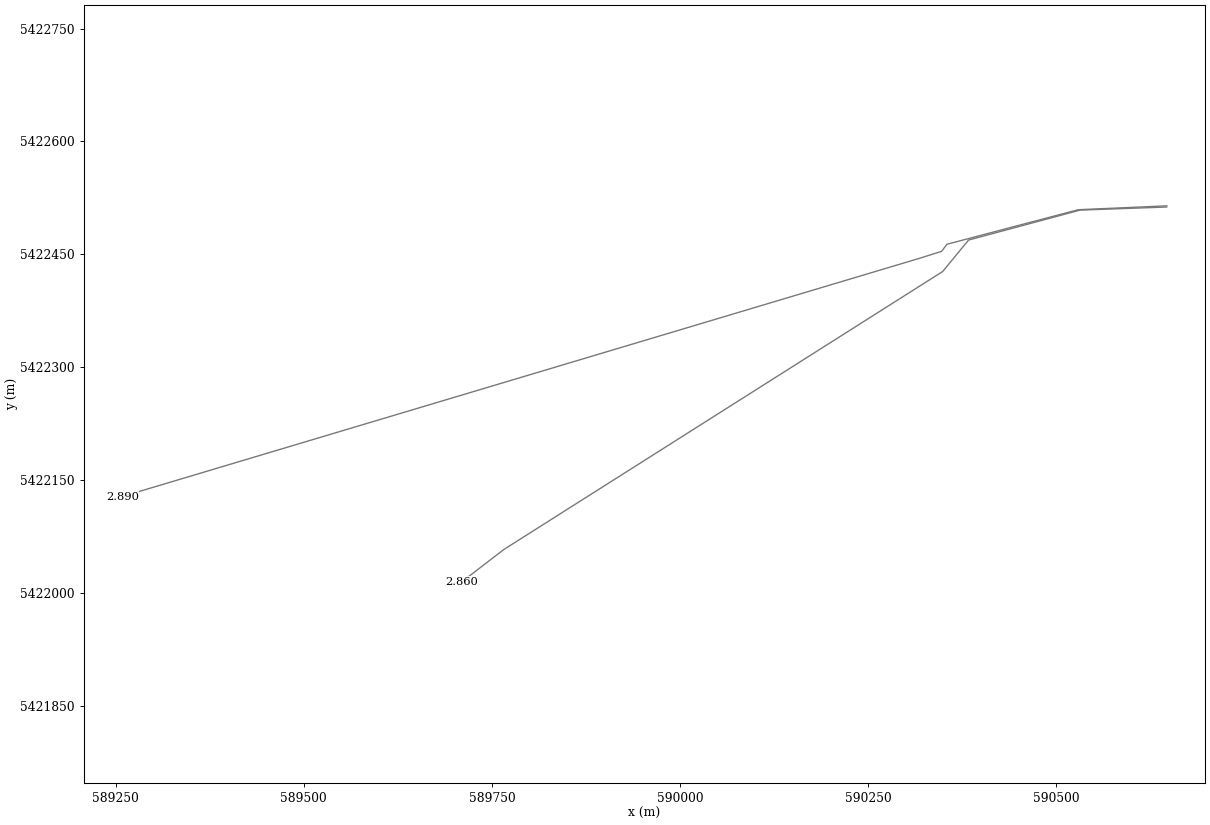
HEC-RAS study Exploits_FMM.prj: Exploits_FMM

--- Exploits_FMM.g01 (geometry) --- (continued)

Type RM Length L Ch R = 3 ,2.898   ,,,
Node Photo=.\Photos\WB-CR-2.JPG
BEGIN DESCRIPTION:
Wigwam Brook Newfoundland T'Railway Bridge
END DESCRIPTION:
Node Name=WB-CR-2
Bridge Culvert--1,0,-1,-1, 0
Deck Dist Width WeirC Skew NumUp NumDn MinLoCord MaxHiCord MaxSubmerge Is_Ogee
5.5,3.4,1.4,0, 396, 396, , , 0.98, 0, 3,3,,
    -144-141.002-137.004-126.012-121.015-119.017-116.019-112.021-100.029-95.0333
-90.0367-86.0394-84.0408-79.0442-77.0455-76.0462-74.0476-71.0588-69.0785-65.1179
-63.1377-60.1672-59.1771-55.2165 -51.256-47.2954-42.3447-41.3546-39.3743-35.4137
-32.4433-28.4827-26.5025-24.5222-23.5321-21.5518-20.5616-17.5912-14.6208 -6.7315
 -2.7922 -1.8073   .1623  3.1168  5.0865  7.0562  9.0258 11.9803 14.9348 20.8438
 24.7831 26.7528  31.677 33.6466 35.6163  37.586 45.4435    51.5  52.288 54.2435
      56 60.1102 66.9547 70.8659 74.7996 80.7342 83.7015 85.6797 87.6579 90.6251
101.5052 110.407116.3416 120.298 121.287 131.178133.1562135.1344143.0471147.0035
155.9054157.8876160.8609163.8342169.7808172.7541175.7274 181.674192.5761198.5227
 201.496203.4782204.4693207.4426210.4159215.3714217.3536223.3002227.2646228.2557
234.2023245.1044247.0866252.0421256.9976259.9709261.9531264.9264277.8396281.8137
283.8007292.7422295.7228298.7033301.6838303.6709309.6319 313.606318.5735327.5151
329.5021337.4502338.4437340.4307341.4242346.3918348.3788350.3658355.3333358.3139
362.2879364.2749367.2555370.2385375.2181380.1979382.1898384.1816387.1695389.1614
392.1492394.1411 396.133398.1249408.0843412.0681416.0519418.0438420.0356425.0153
427.0073431.9869433.9788438.9586441.9464442.9423447.9221452.9018456.8856459.8734
462.8612 466.845467.8409469.8328470.8287474.8126476.8044480.7882 484.772487.7598
489.7517494.7314495.7274497.7192500.7071 502.699506.6827509.6706513.6544514.6503
518.6369521.6332531.6207538.6121542.6071543.6058548.5996554.5922557.5884561.5835
 563.581565.5785569.5735573.5686574.5673577.5636583.5562586.5524588.5499590.5475
593.5438  596.54598.5375 600.535601.5338603.5313605.5288607.5264609.5239611.5214
615.5164618.5127622.5077624.5052628.5002630.4978634.4928636.4904639.4866641.4841
644.4804648.4754 654.468655.4667657.4642659.4618663.4568667.4518669.4493671.4468
674.4431676.4407 679.437681.4344683.4319 687.427692.3922693.3837695.3669699.3333
702.3081704.2913707.2661710.2409714.2073715.1989720.1569724.1232 727.098733.0476
734.0392 737.014738.9972745.9384749.9047751.8879758.8291760.8123763.7871766.7619
770.7283775.6863778.6611781.6353 783.618784.6094 786.592788.5747792.5401795.5141
798.4881800.4708802.4535803.4448804.4362807.4102810.3842814.3496819.3063 821.289
 824.263829.2197832.1937836.1591838.1418839.1331841.1158843.0984 846.075848.0601
854.0156 856.001 859.971 861.956 866.919 872.875 876.845  878.83 881.808 882.801
 885.778 887.763 889.749 890.741 895.704 898.682  901.66 904.637 908.608 910.593
 913.571 915.556 916.548 918.533 921.511 923.496 925.481 929.452 930.444 933.422
 935.407   936.4 938.385 942.355 946.326 951.289 953.274 955.262  957.25 963.215
 965.204 968.186 971.169 973.157 975.145 977.134 980.116 983.099 985.087 987.075
 989.064 992.046 994.035 997.0171002.982 1004.971006.9591008.9471011.9291013.918
1015.9061023.8591025.8481032.8071034.7951039.7661044.7371046.7251050.6941057.641
1066.571 1070.541075.5021078.479 1083.441084.4321089.3941095.348 1096.341100.309
1103.2861105.271 1109.241111.2251113.209  1116.21118.1981121.1961122.1951126.192
1128.1911137.1841140.181 1141.181143.1791148.1751151.1731152.172 1155.171160.166
1162.1641164.1631166.1611171.1571173.1561174.155
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                                                          72.405 72.402272.39525
  72.389
    -129-126.002-122.004-111.012-106.015-104.017-101.019-97.0217-85.0299-80.0333
-75.0367-71.0394-69.0408-64.0442-62.0455-61.0462-59.0476-56.0588-54.0785-50.1179
-48.1377-45.1672-44.1771-40.2165 -36.256-32.2954-27.3447-26.3546-24.3743-20.4137
-17.4433-13.4827-11.5025 -9.5222 -8.5321 -6.5518 -5.5616 -2.5912   .3792  8.2685
 12.2078 13.1927 15.1623 18.1168 20.0865 22.0562 24.0258 26.9803 29.9348 35.8438
 39.7831 41.7528  46.677 48.6466 50.6163  52.586 60.4435 66.3102  67.288 69.2435
 70.8102 75.1102 81.9547 85.8659 89.7996 95.7342 98.7015100.6797102.6579105.6251
116.5052 125.407131.3416 135.298 136.287 146.178148.1562150.1344158.0471162.0035
170.9054172.8876175.8609178.8342184.7808187.7541190.7274 196.674207.5761213.5227
 216.496218.4782219.4693222.4426225.4159230.3714232.3536238.3002242.2646243.2557
249.2023260.1044262.0866267.0421271.9976274.9709276.9531279.9264292.8396296.8137
298.8007307.7422310.7228313.7033316.6838318.6709324.6319 328.606333.5735342.5151
344.5021352.4502353.4437355.4307356.4242361.3918363.3788365.3658370.3333373.3139
377.2879379.2749382.2555385.2385390.2181395.1979397.1898399.1816402.1695404.1614
407.1492409.1411 411.133413.1249423.0843427.0681431.0519433.0438435.0356440.0153
442.0073446.9869448.9788453.9586456.9464457.9423462.9221467.9018471.8856474.8734
477.8612 481.845482.8409484.8328485.8287489.8126491.8044495.7882 499.772502.7598
504.7517509.7314510.7274512.7192515.7071 517.699521.6827524.6706528.6544529.6503
533.6369536.6332546.6207553.6121557.6071558.6058563.5996569.5922572.5884576.5835
 578.581580.5785584.5735588.5686589.5673592.5636598.5562601.5524603.5499605.5475
608.5438  611.54613.5375 615.535616.5338618.5313620.5288622.5264624.5239626.5214
630.5164633.5127637.5077639.5052643.5002645.4978649.4928651.4904654.4866656.4841
659.4804663.4754 669.468670.4667672.4642674.4618678.4568682.4518684.4493686.4468
689.4431691.4407 694.437696.4344698.4319 702.427707.3922708.3837710.3669714.3333
717.3081719.2913722.2661725.2409729.2073730.1989735.1569739.1232 742.098748.0476
749.0392 752.014753.9972760.9384764.9047766.8879773.8291775.8123778.7871781.7619
785.7283790.6863793.6611796.6353 798.618799.6094 801.592803.5747807.5401810.5141
813.4881815.4708817.4535818.4448819.4362822.4102825.3842829.3496834.3063 836.289
 839.263844.2197847.1937851.1591853.1418854.1331856.1158858.0984 861.075863.0601
869.0156 871.001 874.971 876.956 881.919 887.875 891.845  893.83 896.808 897.801
 900.778 902.763 904.749 905.741 910.704 913.682  916.66 919.637 923.608 925.593
 928.571 930.556 931.548 933.533 936.511 938.496 940.481 944.452 945.444 948.422
 950.407   951.4 953.385 957.355 961.326 966.289 968.274 970.262  972.25 978.215
 980.204 983.186 986.169 988.157 990.145 992.134 995.116 998.0991000.0871002.075
1004.0641007.0461009.0351012.0171017.982 1019.971021.9591023.9471026.9291028.918
1030.9061038.8591040.8481047.8071049.7951054.7661059.7371061.7251065.6941072.641
1081.571 1085.541090.5021093.479 1098.441099.4321104.3941110.348 1111.341115.309
1118.2861120.271 1124.241126.2251128.209  1131.21133.1981136.1961137.1951141.192
1143.1911152.1841155.181 1156.181158.1791163.1751166.1731167.172 1170.171175.166
1177.1641179.1631181.1611186.1571188.1561189.155
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                                                          72.40472.4005272.39357
  72.388
BR Coef=-1 , 0 , 0 ,, 0 ,,,0.8,-1,,0,
WSPro=,,,, 1 ,,,, 0 ,,,, 0 ,,,,-1 ,-1 ,-1 , 0 , 0 , 0 , 0 , 0
BC Design=,, 0 ,, 0 ,,,,,,
BC Use User HTab Curves=0
BC User HTab FreeFlow(D)= 0

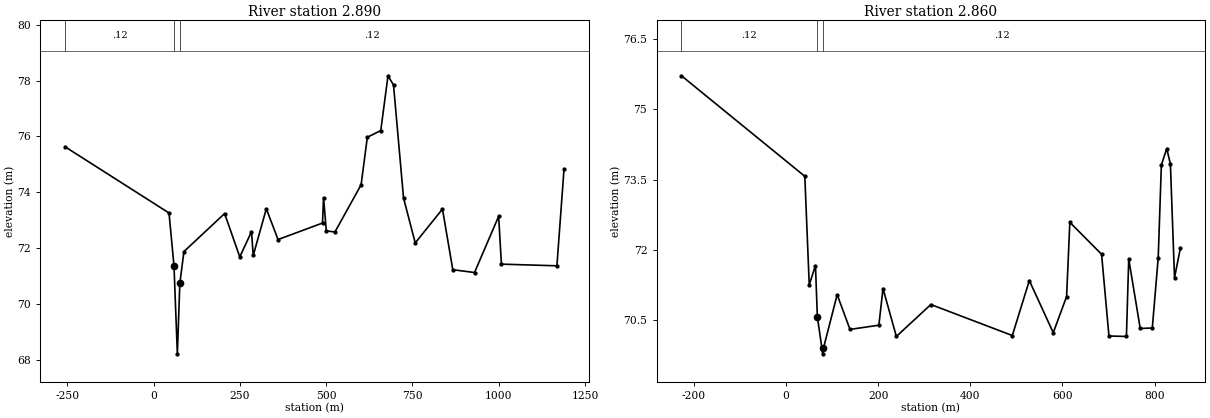
Type RM Length L Ch R = 1 ,2.890   ,24.28,29.72,40.78
BEGIN DESCRIPTION:
DS of Wigwam Brook Newfoundland T'Railway Bridge - WB07 (SEM 2019)
END DESCRIPTION:
XS GIS Cut Line= 6
  590646.6621036 5422514.5046831  590528.9269036 5422509.3497831
  590354.4420036 5422463.4542831  590347.3280036 5422454.0299831
  590318.3870036 5422444.9039831  589258.8969036 5422128.3050831
#Sta/Elev= 30
    -257   75.63   44.37   73.26   58.76   71.37   68.52   68.22   75.71   70.74
   87.59   71.88  205.49   73.24  249.45   71.69  283.42   72.59  288.42   71.74
  326.38   73.41  360.36   72.31  489.25    72.9  492.24   73.81  500.24   72.62
  525.22   72.58  601.15   74.27  619.14   75.97   658.1   76.21  679.09   78.17
  695.07   77.84  724.05    73.8  758.02   72.19  836.95    73.4  866.92   71.23
  929.87   71.13  999.81   73.14  1007.8   71.43 1168.67   71.37 1189.37   74.84
#Mann= 3 , 0 , 0
    -257     .12       0   58.76     .04       0   75.71     .12       0
Bank Sta=58.76,75.71
XS Rating Curve= 0 ,0
Exp/Cntr=0.3,0.1

Type RM Length L Ch R = 1 ,2.860   ,153.38,152.89,153.26
BEGIN DESCRIPTION:
WB06 (SEM 2019)
END DESCRIPTION:
XS GIS Cut Line= 6
  590646.3975036 5422512.9171831  590531.3578036 5422508.8315831
  590383.1908036 5422469.0381831  590348.7430036 5422427.2109831
  589765.7279036 5422057.8942831  589710.0985036 5422015.1363831
#Sta/Elev= 30
    -227   75.71   40.72   73.57   50.33   71.26   63.87   71.67   67.94   70.58
   79.54   69.79   81.16   69.91  110.98   71.05  138.77   70.31  201.47    70.4
  210.46   71.18  239.42   70.16  314.33   70.84  491.13   70.18  528.08   71.35
  580.02   70.24  608.99   71.01  615.98   72.59   684.9   71.91  700.88   70.17
  738.83   70.16  743.83   71.81   768.8   70.33  795.02   70.34  807.81   71.83
   814.7   73.81  826.34   74.16  834.29   73.83  843.22   71.41  856.14   72.05
#Mann= 3 , 0 , 0
    -227     .12       0   67.94     .04       0   81.16     .12       0
Bank Sta=67.94,81.16
XS Rating Curve= 0 ,0
Exp/Cntr=0.3,0.1