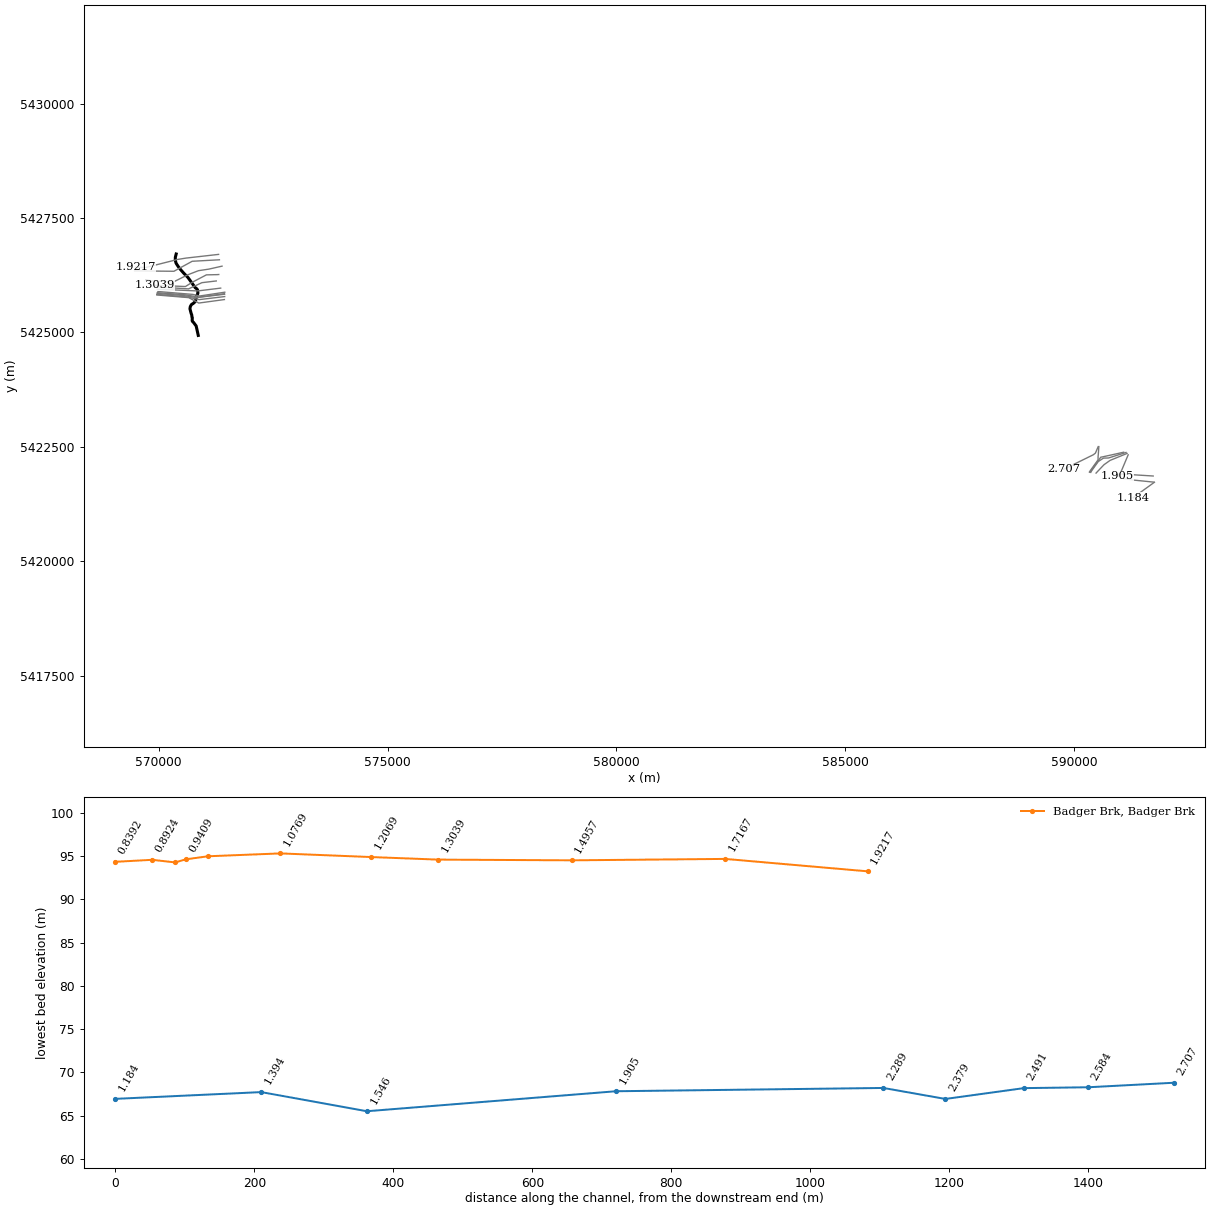
HEC-RAS study Exploits_FMM.prj: Exploits_FMM

--- Exploits_FMM.g01 (geometry) --- (continued)

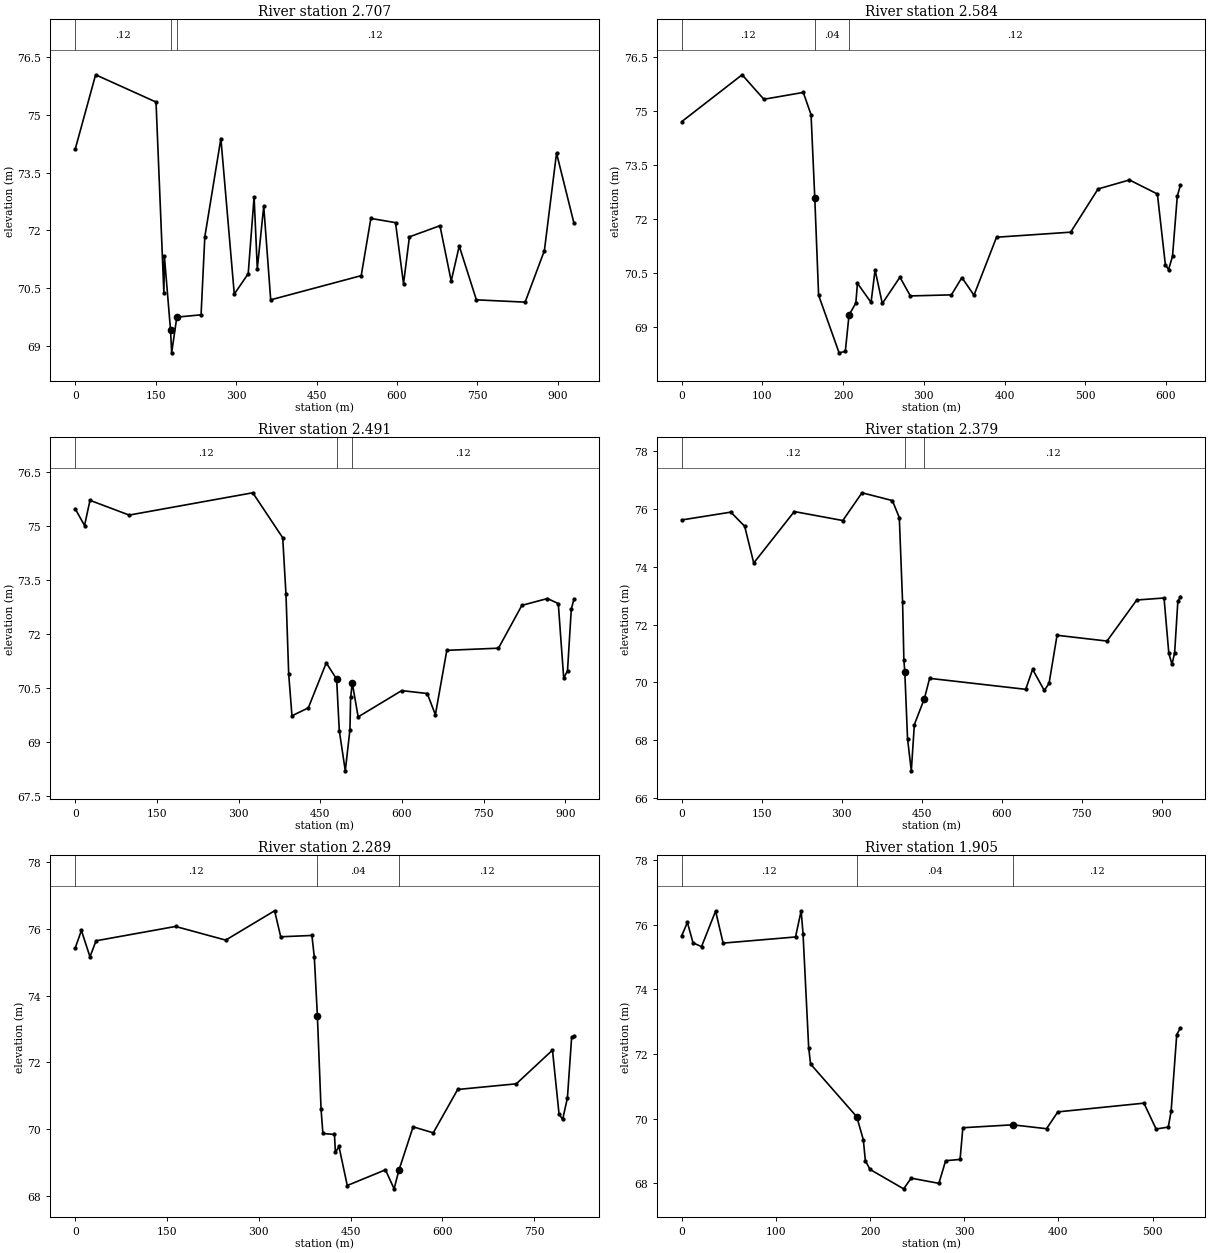
Type RM Length L Ch R = 1 ,2.707   ,129.04,122.82,125.65
BEGIN DESCRIPTION:
WB05 (SEM 2019)
END DESCRIPTION:
XS GIS Cut Line= 6
  590527.0437036 5422504.4631831  590467.2390036 5422365.1679831
  590422.6630036 5422329.5809831  589841.3779036 5422044.0696831
  589803.0290036 5422026.0365831589774.4238361375422012.58535385
#Sta/Elev= 30
       0   74.12    37.9   76.05  150.59   75.34  165.26   70.36  166.17   71.33
  177.66    69.4  179.77   68.81  189.37   69.74  234.61    69.8   241.6   71.83
  271.57   74.39  296.55   70.34  322.52   70.87  333.51   72.87  339.51      71
   351.5   72.63  364.48   70.19  533.33   70.82  551.31   72.31  597.27    72.2
  612.25   70.61  623.24   71.83  680.19   72.12  701.17   70.68  716.16   71.59
  748.13   70.19  839.04   70.13  874.97   71.47  897.64   74.01  930.24   72.18
#Mann= 3 , 0 , 0
       0     .12       0  177.66     .04       0  189.37     .12       0
Bank Sta=177.66,189.37
XS Rating Curve= 0 ,0
Exp/Cntr=0.3,0.1

Type RM Length L Ch R = 1 ,2.584   ,174.27,92.75,71.69
BEGIN DESCRIPTION:
WB04 (SEM 2019)
END DESCRIPTION:
XS GIS Cut Line= 6
  590542.1249036 5422507.6381831  590531.5320036 5422349.4479831
  590525.7900036 5422292.6219831  590524.6624036 5422217.1250831
  590358.6169036 5421986.3764831  590335.3717036 5421950.8947831
#Sta/Elev= 30
       0   74.71   74.79   76.01  101.71   75.33  150.57   75.52  160.19    74.9
  164.79    72.6  169.54   69.89  194.93   68.29  202.65   68.33  207.22   69.34
  215.66   69.67  217.65   70.22  234.54   69.69   239.5   70.59  248.45   69.66
   270.3   70.39  283.22   69.87  334.09    69.9  347.06   70.38  362.03   69.89
  389.98    71.5  481.81   71.64  515.75   72.84  554.67   73.09  589.26    72.7
  599.12   70.74  603.07    70.6     608   70.97  613.92   72.64  617.87   72.95
#Mann= 3 , 0 , 0
       0     .12       0  164.79     .04       0  207.22     .12       0
Bank Sta=164.79,207.22
XS Rating Curve= 0 ,0
Exp/Cntr=0.3,0.1

Type RM Length L Ch R = 1 ,2.491   ,55.37,112.9,116.52
BEGIN DESCRIPTION:
WB03 (SEM 2019)
END DESCRIPTION:
XS GIS Cut Line= 5
  591085.0510036 5422384.6066831  590620.2550036 5422282.1389831
  590585.1120036 5422276.3849831  590377.0103036 5421991.7617831
  590349.6592036 5421947.7197831
#Sta/Elev= 30
       0   75.47      17   75.01      27   75.71   98.99    75.3  325.97   75.92
  380.97   74.67  386.96    73.1  391.96   70.88  397.96   69.72  427.96   69.94
  460.96   71.19  480.01   70.74  484.86   69.31  495.91   68.19  504.41   69.33
  505.71   70.23  508.74   70.63  519.56   69.69  599.47   70.42  646.42   70.34
   661.4   69.75  682.38   71.54  777.27    71.6  820.22   72.79  867.15   72.98
  887.09   72.84  897.06   70.77  904.04   70.97  911.02   72.69     916   72.97
#Mann= 3 , 0 , 0
       0     .12       0  480.01     .04       0  508.74     .12       0
Bank Sta=480.01,508.74
XS Rating Curve= 0 ,0
Exp/Cntr=0.3,0.1

Type RM Length L Ch R = 1 ,2.379   ,80.97,89.26,127.2
BEGIN DESCRIPTION:
WB02 (SEM 2019)
END DESCRIPTION:
XS GIS Cut Line= 6
  591135.8511036 5422379.0503831  590752.4691036 5422258.4001831
  590642.9314036 5422256.0188831  590528.6312036 5422179.8187831
  590387.9893036 5421983.5383831  590366.0634036 5421944.5447831
#Sta/Elev= 30
       0   75.62   91.98   75.89  117.98    75.4  134.97   74.13  210.96   75.91
  301.94    75.6  337.93   76.56  394.92   76.29   407.9    75.7  414.04   72.77
  416.44   70.78  418.17   70.37  423.36   68.04  430.41   66.94  436.09   68.54
  454.95   69.44  464.67   70.14  644.87   69.76  657.82   70.45  679.73   69.72
   688.7   69.97  703.64   71.63  797.27   71.43  853.05   72.85  904.24   72.92
  913.19   71.01  919.15   70.62  924.12   71.03  930.09    72.8  935.06   72.97
#Mann= 3 , 0 , 0
       0     .12       0  418.17     .04       0  454.95     .12       0
Bank Sta=418.17,454.95
XS Rating Curve= 0 ,0
Exp/Cntr=0.3,0.1

Type RM Length L Ch R = 1 ,2.289   ,330.66,384.77,394.78
BEGIN DESCRIPTION:
WB01 (SEM 2019)
END DESCRIPTION:
XS GIS Cut Line= 5
  591158.0762036 5422357.6190831  590788.1879036 5422206.0125831
  590654.8377036 5422111.5560831  590510.9583036 5421959.9827831
  590481.4220036 5421928.6696831
#Sta/Elev= 30
       0   75.44    9.99   75.96   23.99   75.17   33.98   75.65   163.9   76.08
  245.85   75.67   325.8   76.55  335.79   75.77  386.76   75.81  390.76   75.15
  395.71    73.4  401.75   70.59  404.74   69.87  423.67   69.84  425.16    69.3
  430.97   69.48  444.56   68.31  506.98   68.78  521.12   68.21  528.99   68.77
  552.21   70.07  585.13   69.89  625.05   71.19  720.87   71.36  779.98   72.37
  790.74   70.45  796.61   70.29  804.44   70.94  811.29   72.75   815.2    72.8
#Mann= 3 , 0 , 0
       0     .12       0  395.71     .04       0  528.99     .12       0
Bank Sta=395.71,528.99
XS Rating Curve= 0 ,0
Exp/Cntr=0.3,0.1

Type RM Length L Ch R = 1 ,1.905   ,547.02,358.45,129.45
BEGIN DESCRIPTION:
NA04 (SEM 2019)
END DESCRIPTION:
XS GIS Cut Line= 3
  591183.2315036 5422327.8489831  591020.1759036 5421940.5919831
  590943.3854036 5421862.5237831
#Sta/Elev= 30
       0   75.66    5.99   76.07   11.98   75.44   20.97   75.32   35.95   76.42
   43.94   75.43  120.82   75.62  126.81   76.43  128.81   75.72   134.8    72.2
   136.8   71.69  185.85   70.06  192.82   69.35  195.01    68.7  199.97   68.43
  235.66   67.83  243.65   68.16   273.1      68  280.27    68.7   295.6   68.74
  298.56   69.72  351.38   69.81  387.44   69.69  399.42   70.21  490.87   70.48
  503.81   69.68  516.75   69.74  519.74   70.23  525.71    72.6  529.69   72.81
#Mann= 3 , 0 , 0
       0     .12       0  185.85     .04       0  351.38     .12       0
Bank Sta=185.85,351.38
XS Rating Curve= 0 ,0
Exp/Cntr=0.3,0.1

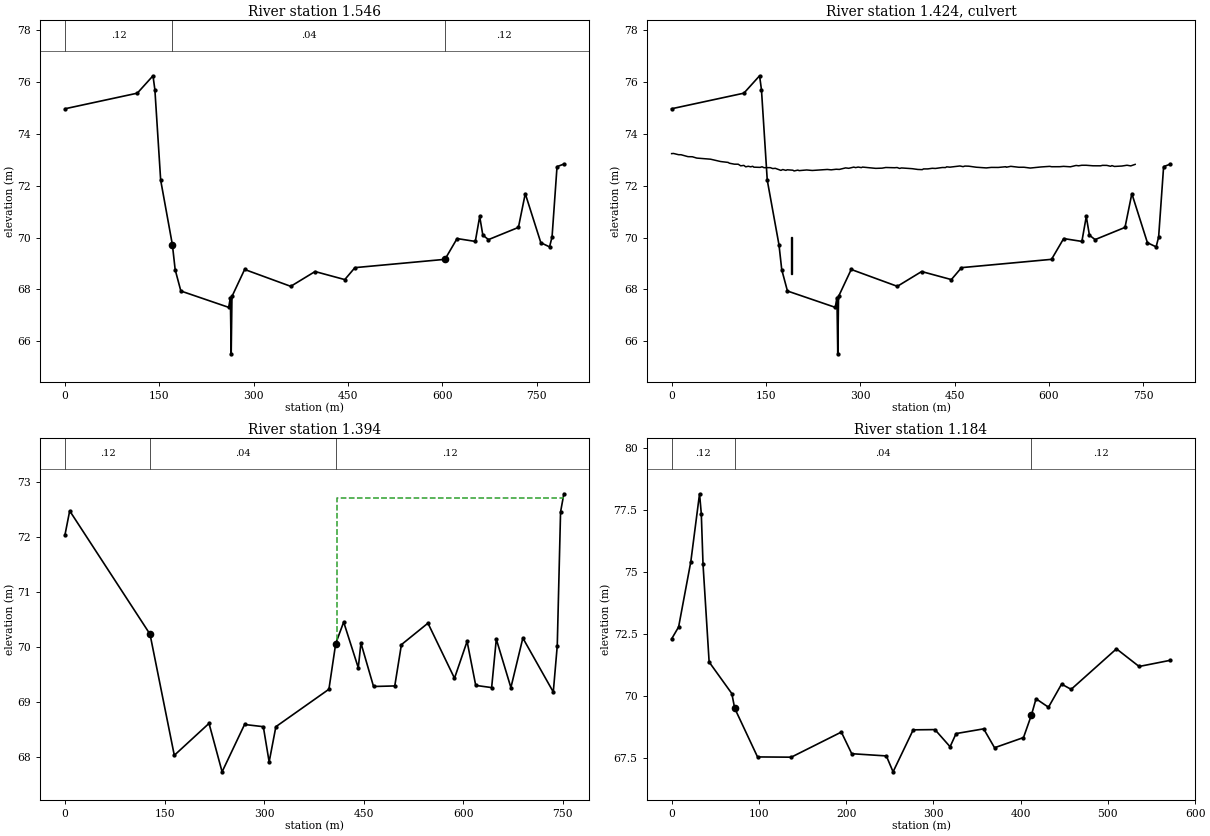
Type RM Length L Ch R = 1 ,1.546   ,144.01,151.96,265.45
BEGIN DESCRIPTION:
US of TCH - NA03 (SEM 2019)
END DESCRIPTION:
XS GIS Cut Line= 3
  591729.5972036 5421864.8272831  591021.8275036 5421908.9816831
  590957.1438036 5421855.1153831
#Sta/Elev= 30
       0   74.96   114.9   75.56  139.88   76.23  142.88   75.69  152.08   72.21
  170.73   69.72  175.14   68.76  184.18   67.94  260.29   67.31  262.92   67.69
  264.24   65.52  265.46   67.73   285.6   68.77  358.92   68.12   397.6   68.69
  444.88   68.38     461   68.84   604.2   69.16  623.48   69.96  652.46   69.85
  659.45   70.81  664.45   70.09  673.44   69.92  721.03   70.39  731.92   71.69
  756.68    69.8  770.54   69.64  774.51   70.02  782.43   72.73  793.32   72.83
#Mann= 3 , 0 , 0
       0     .12       0  170.73     .04       0   604.2     .12       0
Bank Sta=170.73,604.2
XS Rating Curve= 0 ,0
Exp/Cntr=0.3,0.1

Type RM Length L Ch R = 2 ,1.424   ,,,
Node Photo=.\Photos\WB-CR-1.JPG
BEGIN DESCRIPTION:
Trans Canada Highway at North Angle
END DESCRIPTION:
Node Name=WB-CR-1
Bridge Culvert--1,0,-1,-1, 0
Deck Dist Width WeirC Skew NumUp NumDn MinLoCord MaxHiCord MaxSubmerge Is_Ogee
100,24.4,1.4,0, 100, 100, , , 0.98, 0, 3,3,,
       0   2.997  10.987  14.983   25.97  32.962  39.953  61.928  77.909  89.895
  91.893  99.884 105.877 109.872 114.866 117.863 121.858 125.853  128.85 130.847
 140.836 143.832 146.829 156.817 160.813 164.808 173.797 176.794 181.788 183.786
 192.775 194.773 200.766 202.764  214.75 223.739 247.711 253.704 261.695 266.689
 276.677 281.672 289.662 292.659 296.654 301.648 303.646 324.621  334.61 340.603
 354.587 358.582 362.577 365.574 382.554 391.543 398.535 400.533 407.525 414.517
 419.511 430.498 435.492  437.49 442.484 458.465  463.46 466.456 472.449 484.435
 500.416 508.407 519.394  531.38 532.379 539.371 552.356 560.347 570.335 587.315
 601.299 604.295  617.28 623.273  634.26  643.25 647.245 652.239 659.231 670.218
 682.204 685.201 692.193 698.186 700.183 704.179 716.165 724.156 730.149  737.14
  73.232  73.238   73.19  73.189  73.115  73.111   73.06  73.017  72.927  72.893
  72.862  72.825  72.824  72.762  72.778  72.723  72.745  72.723  72.744   72.71
  72.702  72.726   72.69  72.692  72.656  72.666  72.586  72.619  72.586  72.609
  72.593  72.564  72.597  72.577  72.602  72.583  72.622  72.607   72.63  72.623
  72.682  72.666  72.712  72.693  72.714  72.693  72.713  72.664  72.672  72.697
  72.688  72.696  72.661   72.68  72.652  72.622  72.615  72.642  72.643  72.667
   72.66  72.697  72.695  72.723   72.71  72.756   72.73  72.752  72.748  72.708
  72.681  72.701  72.699  72.727  72.708  72.742  72.706  72.707  72.676  72.718
  72.741  72.727  72.728  72.741  72.724  72.776  72.763  72.783  72.783  72.763
  72.762   72.78  72.778  72.744   72.77  72.738  72.754  72.784  72.759  72.817
       0   2.997  10.987  14.983   25.97  32.962  39.953  61.928  77.909  89.895
  91.893  99.884 105.877 109.872 114.866 117.863 121.858 125.853  128.85 130.847
 140.836 143.832 146.829 156.817 160.813 164.808 173.797 176.794 181.788 183.786
 192.775 194.773 200.766 202.764  214.75 223.739 247.711 253.704 261.695 266.689
 276.677 281.672 289.662 292.659 296.654 301.648 303.646 324.621  334.61 340.603
 354.587 358.582 362.577 365.574 382.554 391.543 398.535 400.533 407.525 414.517
 419.511 430.498 435.492  437.49 442.484 458.465  463.46 466.456 472.449 484.435
 500.416 508.407 519.394  531.38 532.379 539.371 552.356 560.347 570.335 587.315
 601.299 604.295  617.28 623.273  634.26  643.25 647.245 652.239 659.231 670.218
 682.204 685.201 692.193 698.186 700.183 704.179 716.165 724.156 730.149  737.14
  73.232  73.238   73.19  73.189  73.115  73.111   73.06  73.017  72.927  72.893
  72.862  72.825  72.824  72.762  72.778  72.723  72.745  72.723  72.744   72.71
  72.702  72.726   72.69  72.692  72.656  72.666  72.586  72.619  72.586  72.609
  72.593  72.564  72.597  72.577  72.602  72.583  72.622  72.607   72.63  72.623
  72.682  72.666  72.712  72.693  72.714  72.693  72.713  72.664  72.672  72.697
  72.688  72.696  72.661   72.68  72.652  72.622  72.615  72.642  72.643  72.667
   72.66  72.697  72.695  72.723   72.71  72.756   72.73  72.752  72.748  72.708
  72.681  72.701  72.699  72.727  72.708  72.742  72.706  72.707  72.676  72.718
  72.741  72.727  72.728  72.741  72.724  72.776  72.763  72.783  72.783  72.763
  72.762   72.78  72.778  72.744   72.77  72.738  72.754  72.784  72.759  72.817
BR Coef=-1 , 0 , 0 ,, 0 ,,,0.8,-1,,0,
WSPro=,,,, 1 ,,,, 0 ,,,, 0 ,,,,-1 ,-1 ,-1 , 0 , 0 , 0 , 0 , 0
Culvert=2,1.4,1.6,24.4,0.014,0.5,1,8,3,68.606,190,68.606,190,Culvert #1  , 0 ,100
     190     190
BC Culvert Barrel=1,Culvert,0
Culvert Bottom n=0.014
Culvert Bottom Depth=1.4
BC Design=,, 0 ,, 0 ,,,,,,
BC HTab HWMax=74
BC Use User HTab Curves=0
BC User HTab FreeFlow(D)= 0

Type RM Length L Ch R = 1 ,1.394   ,102.55,210.08,310.23
BEGIN DESCRIPTION:
DS of TCH - NA02 (SEM 2019)
END DESCRIPTION:
XS GIS Cut Line= 4
  591741.2389036 5421731.2123831  591320.5505036 5421774.0749831
  591023.9861036 5421818.7055831  591017.0288036 5421846.7611831
#Sta/Elev= 30
       0   72.04       7   72.47  128.03   70.23  164.64   68.03  216.96   68.61
  236.66   67.73  270.52   68.59  298.78   68.55  307.56   67.91   317.7   68.55
  397.62   69.23  407.87   70.06  419.87   70.45  441.87   69.62  445.86   70.07
  464.86   69.28  496.86   69.29  506.86   70.04  546.86   70.43  586.86   69.43
  605.85    70.1  618.85    69.3  642.85   69.26  649.85   70.14  671.85   69.26
  689.85   70.16  735.73   69.18  741.71   70.02  746.69   72.45  751.68   72.78
#Mann= 3 , 0 , 0
       0     .12       0  128.03     .04       0  407.87     .12       0
#XS Ineff= 2 , 0
                          409.76            72.7
Permanent Ineff=
       F       T
Bank Sta=128.03,407.87
XS Rating Curve= 0 ,0
Exp/Cntr=0.3,0.1

Type RM Length L Ch R = 1 ,1.184   ,649.29,1184.04,868
BEGIN DESCRIPTION:
North Angle - NA01 (SEM 2019)
END DESCRIPTION:
XS GIS Cut Line= 3
591756.5847035985421728.56658309591389.3423035985421463.45348309
591295.4150035995421390.69298309
#Sta/Elev= 30
       0    72.3       8   72.78      22   75.41      32   78.14      34   77.34
   35.99    75.3   42.99   71.37   68.99    70.1   72.27   69.51   98.46   67.55
  137.12   67.54  194.52   68.55  206.43   67.68  246.11   67.59  253.82   66.95
  276.88   68.64  301.81   68.65  319.16   67.96  326.04   68.49  357.66   68.68
  370.12   67.92  403.31   68.33  412.44   69.24  417.67   69.89  431.94   69.55
  446.94   70.48  457.93   70.27  509.85    71.9  535.81   71.19  571.75   71.44
#Mann= 3 , 0 , 0
       0     .12       0   72.27     .04       0  412.44     .12       0
Bank Sta=72.27,412.44
XS Rating Curve= 0 ,0
Exp/Cntr=0.3,0.1

River Reach=Badger Brk      ,Badger Brk
Reach XY= 30
     570382.3974    5426714.7412     570363.7238    5426642.2364
     570363.2736    5426580.0099      570380.008    5426514.2004
     570424.7418    5426444.3103     570479.6389    5426373.2943
     570543.4582    5426300.4861     570641.2846      5426200.18
     570800.4117    5425976.8899     570824.7512     5425960.703
     570849.2496      5425932.45     570857.1987    5425859.5457
     570844.2978    5425826.3609     570823.2081    5425788.6188
     570807.2691    5425697.6227     570792.4086    5425668.2214
     570750.9888    5425631.4814     570721.3674    5425615.2237
     570707.6528     5425595.996     570690.9096    5425565.3002
     570683.2893     5425517.577     570710.7069    5425411.9142
     570721.8377    5425386.6647     570726.9116    5425338.4788
     570735.2763     5425325.121     570731.4901    5425258.8212
     570740.4263    5425239.2619     570760.1978     5425221.455
     570819.0139    5425142.8716      570864.899    5424936.1873

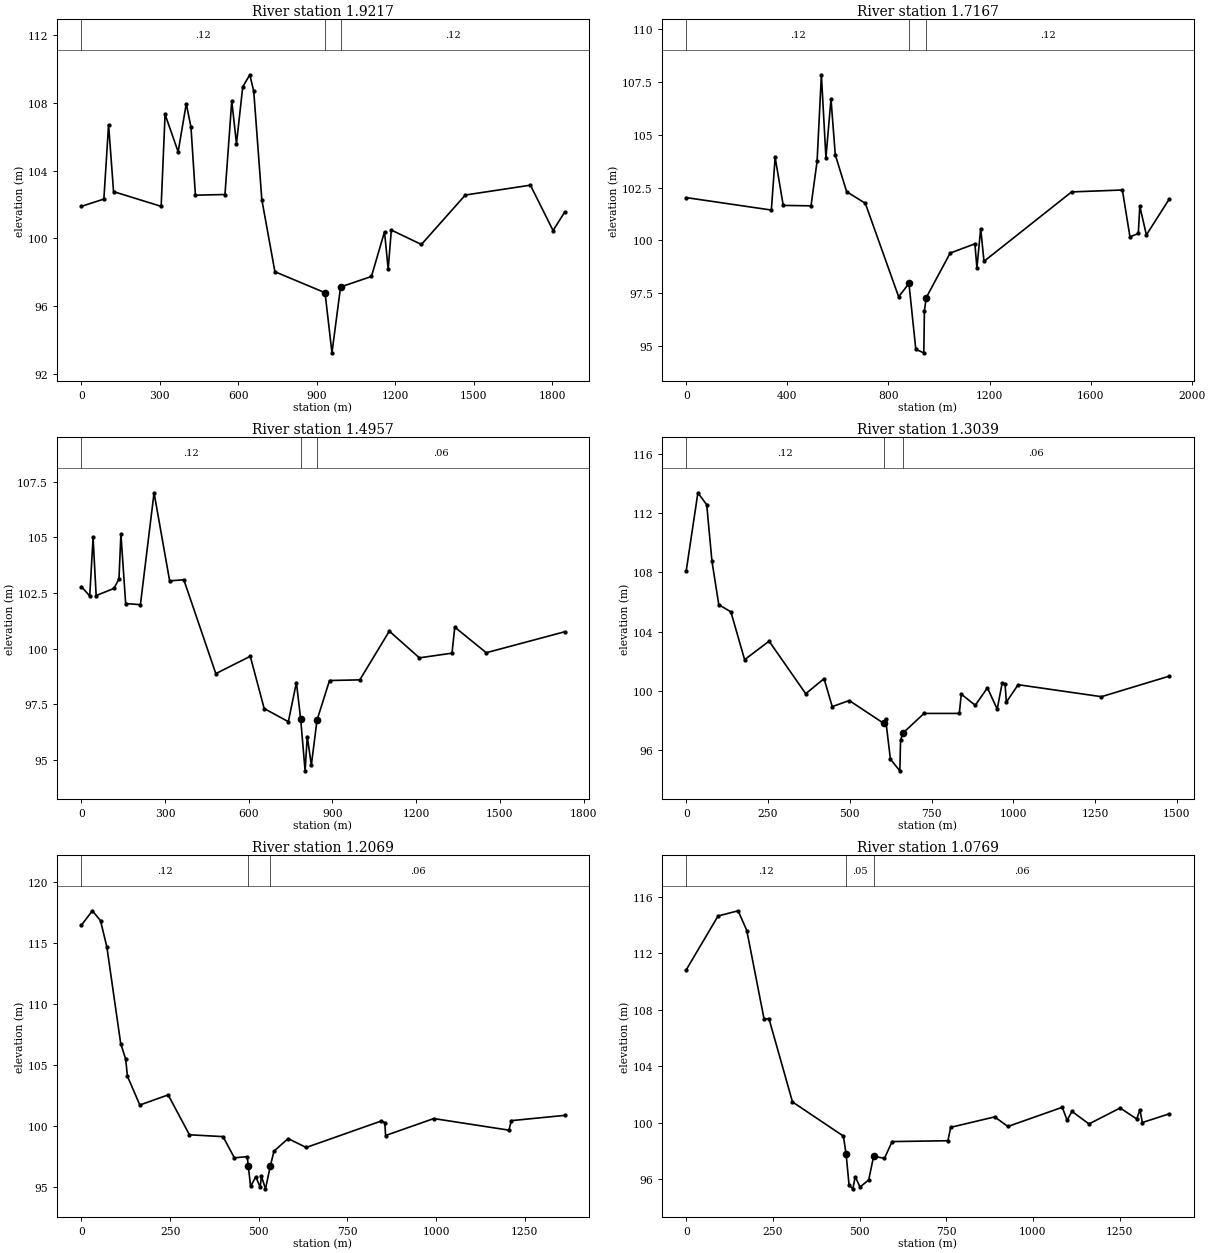
Type RM Length L Ch R = 1 ,1.9217  ,197.74,204.95,213.43
BEGIN DESCRIPTION:
BB06A (SEM 2019)
END DESCRIPTION:
XS GIS Cut Line= 6
  571308.9118036 5426706.1733831  570593.0028036 5426624.9547831
  570394.3130036 5426592.2669831  570328.3320036 5426574.0269831
  569709.8947036 5426418.0764831  569492.0791036 5426427.9283831
#Sta/Elev= 30
       0  101.89   85.94  102.32  103.93  106.72  122.92  102.76  304.79  101.89
  319.78  107.32  369.74  105.11  400.72  107.95  418.71  106.57   435.7  102.55
  548.62  102.59   574.6  108.11  592.59   105.6  616.57  108.95  643.56  109.66
  658.55  108.69  689.52  102.28  739.44   98.03  930.99   96.79  957.44   93.24
  990.36   97.13 1108.28   97.75 1158.27  100.39 1172.26   98.18 1184.26  100.49
 1299.22   99.64 1467.17  102.56 1715.73  103.14 1802.34  100.46 1846.15  101.54
#Mann= 3 , 0 , 0
       0     .12       0  930.99     .05       0  990.36     .12       0
Bank Sta=930.99,990.36
XS Rating Curve= 0 ,0
Exp/Cntr=0.3,0.1

Type RM Length L Ch R = 1 ,1.7167  ,220.41,220.98,223.48
BEGIN DESCRIPTION:
BB05 (SEM 2016)
END DESCRIPTION:
XS GIS Cut Line= 4
  571327.2238036 5426588.3872831  570732.3214036 5426555.8672831
  570332.7896036 5426337.2788831  569472.5343036 5426345.8957831
#Sta/Elev= 30
       0  102.03  336.88  101.44  351.88  103.94  383.87  101.66  493.83  101.64
  517.82  103.75  534.81  107.85  552.81  103.92   572.8   106.7  589.79  104.06
  634.74  102.31  708.65  101.76  840.48   97.33  881.21   97.96 908.381   94.84
 940.072  94.674  942.35   96.66  949.65   97.29 1044.22    99.4 1142.13   99.84
 1150.13    98.7 1165.12  100.56 1178.11   99.01 1524.82   102.3 1725.66  102.39
 1755.64  100.17 1788.61  100.33  1794.6  101.62 1820.58  100.26 1911.51  101.97
#Mann= 3 , 0 , 0
       0     .12       0  881.21     .05       0  949.65     .12       0
Bank Sta=881.21,949.65
XS Rating Curve= 0 ,0
Exp/Cntr=0.3,0.1

Type RM Length L Ch R = 1 ,1.4957  ,191.68,191.83,196.23
BEGIN DESCRIPTION:
BB05A (SEM 2019)
END DESCRIPTION:
XS GIS Cut Line= 6
  571384.6265036 5426449.3026831  571098.3751036 5426384.8446831
  570868.6799036 5426350.0741831  570639.1779036 5426261.4737831
  570324.3048036 5426104.8151831  569716.9908036 5426137.1507831
#Sta/Elev= 30
       0  102.79   29.94  102.37   41.92     105    52.9  102.39  116.77  102.71
  134.73  103.14  141.72  105.15  158.69  102.03  211.58  101.98  260.48  107.01
  316.35  103.05   367.2   103.1  481.86   98.88  605.41   99.66  655.21   97.31
  741.86   96.72  770.74   98.48   786.1   96.83  801.92   94.51  809.67   96.05
  824.29   94.77  844.64   96.79   889.4   98.57  998.08    98.6 1103.77  100.79
 1211.59   99.59 1328.44    99.8 1338.42  100.97 1451.27   99.82 1731.89  100.76
#Mann= 3 , 0 , 0
       0     .12       0   786.1     .05       0  844.64     .06       0
Bank Sta=786.1,844.64
XS Rating Curve= 0 ,0
Exp/Cntr=0.3,0.1

Type RM Length L Ch R = 1 ,1.3039  ,101.12,96.99,92.76
BEGIN DESCRIPTION:
BB04 (SEM 2016)
END DESCRIPTION:
XS GIS Cut Line= 6
  571312.8846036 5426266.6835831  571279.2574036 5426264.0965831
  571042.6509036 5426258.9089831  570732.5781036 5426096.7021831
  570584.6871036 5426004.0439831  569903.2756036 5426032.4634831
#Sta/Elev= 30
       0  108.09   35.72  113.37   62.69  112.56   78.66  108.76   99.63  105.81
  136.58  105.33  178.52   102.1  253.41  103.35  365.37    99.8  421.36  100.82
  446.36   98.93  498.35   99.34  604.39   97.79  609.33   98.12 624.219  95.381
 652.977  94.593  655.23   96.66   662.3   97.14  727.03   98.47  834.79   98.47
  840.78   99.77  883.72   99.02  920.66   100.2  950.62   98.76   965.6   100.5
  974.59  100.48  978.58   99.23 1014.53  100.41 1269.15    99.6 1476.84  100.99
#Mann= 3 , 0 , 0
       0     .12       0  604.39     .05       0   662.3     .06       0
Bank Sta=604.39,662.3
XS Rating Curve= 0 ,0
Exp/Cntr=0.3,0.1

Type RM Length L Ch R = 1 ,1.2069  ,150.42,129.99,115.78
BEGIN DESCRIPTION:
BB04A (SEM 2019)
END DESCRIPTION:
XS GIS Cut Line= 4
  571258.0140036 5426125.9812831  570944.7676036 5426088.3940831
  570653.7215036 5425952.7864831  569929.9179036 5425997.2709831
#Sta/Elev= 30
       0   116.5   30.95  117.68   53.91  116.87   71.88   114.7  110.82  106.79
   124.8  105.53  129.79  104.12  164.74  101.76  244.61  102.59  304.51   99.32
  399.25   99.17  431.16   97.43  467.44   97.53  470.37   96.77  476.94   95.09
  491.54   95.88  503.93   95.02  507.43   95.93  518.87   94.89  532.75   96.79
  542.85   97.98  582.73   99.01  633.59   98.28  845.34  100.45  855.33  100.32
  857.33   99.26  993.18  100.65 1204.94    99.7 1211.93  100.48 1361.76  100.91
#Mann= 3 , 0 , 0
       0     .12       0  470.37     .05       0  532.75     .06       0
Bank Sta=470.37,532.75
XS Rating Curve= 0 ,0
Exp/Cntr=0.3,0.1

Type RM Length L Ch R = 1 ,1.0769  ,121.67,104.07,95.79
BEGIN DESCRIPTION:
BB04B (SEM 2019)
END DESCRIPTION:
XS GIS Cut Line= 4
  571354.7469036 5425969.5420831  570892.8970036 5425912.7989831
  570832.4320036 5425908.6779831  569965.5408036 5425946.0643831
#Sta/Elev= 30
       0  110.83   91.87  114.65  149.78  115.02  174.75  113.62  224.67  107.34
  238.65  107.38  306.55  101.47  453.34   99.05  461.37   97.75  469.77   95.57
  480.69   95.31  487.49   96.17  501.39   95.44  526.41   95.94  540.53   97.61
  571.91   97.48   593.9   98.66  754.85   98.72  762.85   99.67   889.8  100.41
  927.79   99.73 1084.74  101.09 1098.73  100.17 1112.73   100.8 1161.71   99.91
 1251.68  101.04 1299.66  100.26 1308.66  100.93 1315.66  100.01 1393.63  100.63
#Mann= 3 , 0 , 0
       0     .12       0  461.37     .05       0  540.53     .06       0
Bank Sta=461.37,540.53
XS Rating Curve= 0 ,0
Exp/Cntr=0.3,0.1

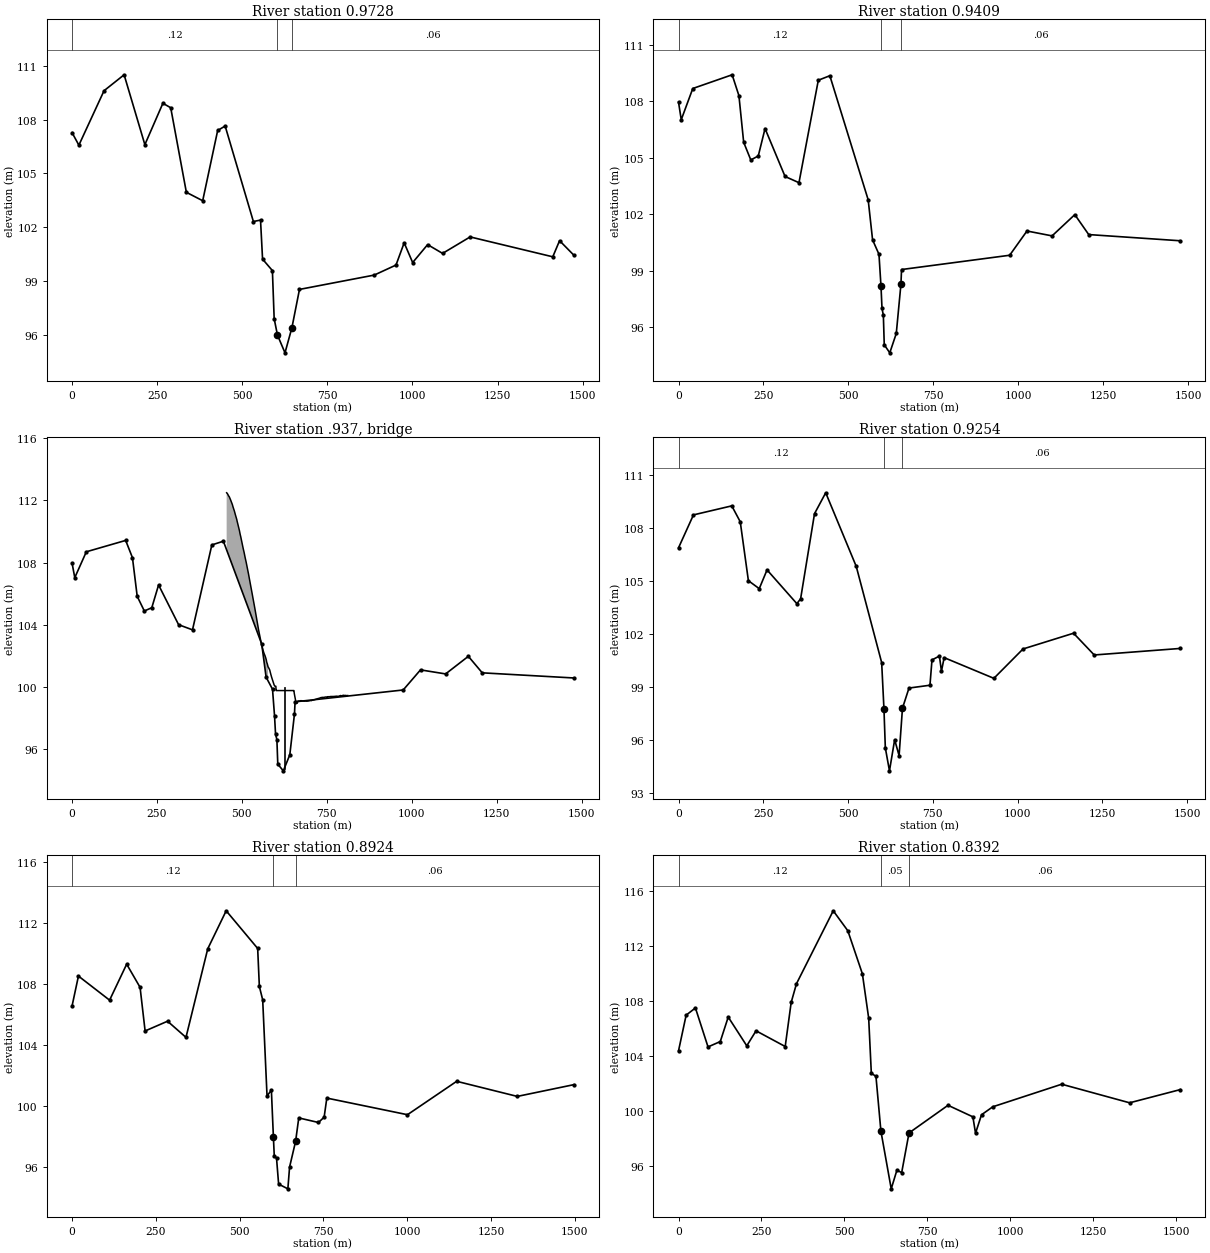
Type RM Length L Ch R = 1 ,0.9728  ,31.05,31.96,33.49
BEGIN DESCRIPTION:
BB04C (SEM 2019)
END DESCRIPTION:
XS GIS Cut Line= 4
  571444.9355036 5425880.3426831  570894.6006036 5425797.1113831
  570745.4148036 5425831.9637831  569983.8026036 5425895.4246831
#Sta/Elev= 30
       0  107.27   19.99  106.57   93.93  109.61  152.89   110.5  213.84   106.6
  266.81  108.91  289.79  108.66  335.75  103.94  383.72  103.47  427.69  107.39
  449.67  107.64  532.61  102.31   553.6  102.39  559.58  100.21  588.49   99.57
  593.66   96.89  603.35   95.97  625.49   94.98  645.88   96.39  668.01   98.52
  887.62   99.32  951.56   99.88  975.53  101.12 1000.51  100.02 1044.46  101.02
 1088.42  100.53 1169.34  101.45 1412.09  100.34 1432.07  101.24 1474.03  100.43
#Mann= 3 , 0 , 0
       0     .12       0  603.35     .05       0  645.88     .06       0
Bank Sta=603.35,645.88
XS Rating Curve= 0 ,0
Exp/Cntr=0.3,0.1

Type RM Length L Ch R = 1 ,0.9409  ,14.05,15.45,18.19
BEGIN DESCRIPTION:
US of Badger Brook Footbridge - BB03 (SEM 2016)
END DESCRIPTION:
XS GIS Cut Line= 5
  571436.8805036 5425847.1186831  570876.5547036 5425772.9754831
  570779.8029036 5425789.5026831  570588.0976036 5425822.2227831
  569970.7594036 5425869.6644831
#Sta/Elev= 30
       0  107.96    7.99  107.03   41.94  108.69  157.78  109.42  177.75  108.31
  191.73  105.83   212.7  104.89  234.67   105.1  254.64  106.56  313.56  104.01
   354.5  103.68  411.42  109.13  445.38  109.37  558.22  102.77  571.16  100.64
     590   99.87  595.95   98.16  598.92   96.99  602.89   96.63 605.529  95.058
 621.799  94.629 640.919  95.659  654.64   98.28  656.42   99.06  974.68   99.82
 1025.62  101.11 1099.52  100.85 1166.43  101.98 1207.37  100.92 1477.01  100.59
#Mann= 3 , 0 , 0
       0     .12       0  595.95     .05       0  654.64     .06       0
Bank Sta=595.95,654.64
XS Rating Curve= 0 ,0
Exp/Cntr=0.3,0.1

Type RM Length L Ch R = 3 ,.937    ,,,
Node Photo=.\Photos\BB-CR-3.JPG
BEGIN DESCRIPTION:
Badger Brook Footbridge
END DESCRIPTION:
Node Name=BB-CR-3
Bridge Culvert--1,0,-1,-1, 0
Deck Dist Width WeirC Skew NumUp NumDn MinLoCord MaxHiCord MaxSubmerge Is_Ogee
10,1.3,1.4,0, 100, 100, , , 0.98, 0, 3,3,,
     455 456.982 460.945 462.927  466.89 471.844 473.826 477.789 480.762 484.725
 485.716 492.652 494.633 496.615 503.551 506.523 509.496 512.468 519.404 530.231
 538.105 548.932 555.822 557.821 561.818 564.816 567.814 569.813 571.812 572.811
  574.81 576.808 578.807 581.805 584.803 587.801 594.797 596.783 599.746 600.734
 601.721 602.709 603.696 604.684 605.671 610.609 615.546 624.434 628.384 629.372
 631.347 632.334 636.284 638.259 642.209 644.185 647.147 649.122  650.11 651.097
 652.085 653.072  654.06  658.01 660.972 662.947 664.923  669.86 673.829 678.815
 683.801 686.792 688.787 693.772 701.749 704.741 706.735 709.727 723.687 727.675
 732.661 738.644 740.638 745.624 748.615 750.609 751.607 753.601 755.595 760.581
 770.552 778.529 783.515 790.495 793.487 798.472 800.467 805.427 808.343 811.258
 112.478 112.432 112.274 112.212 112.005 111.721 111.567 111.304 111.064 110.769
 110.666 110.047 109.825 109.646 108.915 108.635 108.311 108.021 107.259 105.985
 105.046 103.685 102.934 102.744  102.39 102.182 102.023 101.896 101.742  101.61
 101.486 101.309 101.238 101.103  100.84 100.609 100.141 100.065 100.061  99.782
  99.782  99.782  99.782  99.782  99.782  99.782  99.782  99.782  99.782  99.782
  99.782  99.782  99.782  99.782  99.782  99.782  99.782  99.782  99.782  99.782
  99.782  99.782  99.596  99.137  98.971  98.977  99.113  99.111  99.135  99.112
  99.102  99.113  99.101  99.106   99.14  99.136  99.163  99.169  99.267  99.289
  99.332  99.348  99.338  99.368  99.362  99.327  99.371  99.393  99.378    99.4
  99.403  99.421   99.41  99.463  99.441  99.482  99.467   99.47  99.457  99.464
                                                                          98.982
  98.982  98.982  98.982  98.982  98.982  98.982  98.982  98.982  98.982  98.982
  98.982  98.982  98.982  98.982  98.982  98.982  98.982  98.982  98.982  98.982
  98.982  98.982
     460 461.982 465.945 467.927  471.89 476.844 478.826 482.789 485.762 489.725
 490.716 497.652 499.633 501.615 508.551 511.523 514.496 517.468 524.404 535.231
 543.105 553.932 560.822 562.821 566.818 569.816 572.814 574.813 576.812 577.811
  579.81 581.808 583.807 586.805 589.803 592.801 599.797 601.783 604.746 605.734
 606.721 607.709 608.696 609.684 610.671 615.609 620.546 629.434 633.384 634.372
 636.347 637.334 641.284 643.259 647.209 649.185 652.147 654.122  655.11 656.097
 657.085 658.072  659.06  663.01 665.972 667.947 669.923  674.86 678.829 683.815
 688.801 691.792 693.787 698.772 706.749 709.741 711.735 714.727 728.687 732.675
 737.661 743.644 745.638 750.624 753.615 755.609 756.607 758.601 760.595 765.581
 775.552 783.529 788.515 795.495 798.487 803.472 805.467 810.427 813.343 816.258
 112.478 112.432 112.274 112.212 112.005 111.721 111.567 111.304 111.064 110.769
 110.666 110.047 109.825 109.646 108.915 108.635 108.311 108.021 107.259 105.985
 105.046 103.685 102.934 102.744  102.39 102.182 102.023 101.896 101.742  101.61
 101.486 101.309 101.238 101.103  100.84 100.609 100.141 100.065 100.061  99.782
  99.782  99.782  99.782  99.782  99.782  99.782  99.782  99.782  99.782  99.782
  99.782  99.782  99.782  99.782  99.782  99.782  99.782  99.782  99.782  99.782
  99.782  99.782  99.596  99.137  98.971  98.977  99.113  99.111  99.135  99.112
  99.102  99.113  99.101  99.106   99.14  99.136  99.163  99.169  99.267  99.289
  99.332  99.348  99.338  99.368  99.362  99.327  99.371  99.393  99.378    99.4
  99.403  99.421   99.41  99.463  99.441  99.482  99.467   99.47  99.457  99.464
                                                                          98.982
  98.982  98.982  98.982  98.982  98.982  98.982  98.982  98.982  98.982  98.982
  98.982  98.982  98.982  98.982  98.982  98.982  98.982  98.982  98.982  98.982
  98.982  98.982
Pier Skew, UpSta & Num, DnSta & Num=  ,624.25, 2 ,631.25, 2 , 0 , 0 , 0 ,,
     2.2     2.2
       0     100
     2.2     2.2
       0     100
BR Coef=-1 , 0 , 0 ,, 0 ,,,0.8,-1,,0,
WSPro=,,,, 1 ,,,, 0 ,,,, 0 ,,,,-1 ,-1 ,-1 , 0 , 0 , 0 , 0 , 0
BC Design=,, 0 ,, 0 ,,,,,,
BC HTab HWMax=106
BC Use User HTab Curves=0
BC User HTab FreeFlow(D)= 0

Type RM Length L Ch R = 1 ,0.9254  ,35.97,33.06,29
BEGIN DESCRIPTION:
02YO019 Badger Brook Below Footbridge - BB03A (SEM 2019)
END DESCRIPTION:
XS GIS Cut Line= 5
  571439.6576036 5425835.4555831  570845.8720036 5425764.7429831
  570766.6315036 5425772.0116831  570543.1302036 5425807.5026831
  569969.1254036 5425852.6449831
#Sta/Elev= 30
       0  106.88      44  108.74  156.99  109.25  181.99  108.35  205.99  105.02
  237.99  104.57  260.99  105.63  348.99  103.72  359.99     104  400.99  108.81
  433.99  109.99  523.98  105.83  598.97  100.39  605.72   97.77  609.76   95.57
  621.99   94.27  637.26   96.03  650.35   95.13   660.3   97.81  679.55   98.95
  741.36   99.11  747.34  100.54  769.27  100.76  775.25    99.9  783.23  100.67
  929.85    99.5 1015.81  101.16 1164.76  102.05 1225.73  100.82 1479.63  101.19
#Mann= 3 , 0 , 0
       0     .12       0  605.72     .05       0   660.3     .06       0
Bank Sta=605.72,660.3
XS Rating Curve= 0 ,0
Exp/Cntr=0.3,0.1

Type RM Length L Ch R = 1 ,0.8924  ,58.47,53.16,43.45
BEGIN DESCRIPTION:
BB03B (SEM 2019)
END DESCRIPTION:
XS GIS Cut Line= 4
  571442.6350036 5425784.8015831  570886.6962036 5425718.2957831
  570636.6574036 5425773.9431831  569957.7985036 5425833.2438831
#Sta/Elev= 30
       0  106.56      19  108.52  111.98  106.94  162.97   109.3  202.96  107.78
  217.96  104.92  284.95  105.56  339.94   104.5  404.93  110.31  459.92   112.8
   553.9  110.33   558.9  107.84  568.87  106.96  581.83  100.66  594.79  101.04
  600.85   97.96  603.47    96.7   610.1    96.6  616.42   94.88  643.99   94.57
  649.13      96  667.04   97.68  676.52   99.22  735.33   98.92  752.27   99.27
  760.24  100.52 1000.91   99.43 1147.79  101.62 1328.63  100.63 1497.49   101.4
#Mann= 3 , 0 , 0
       0     .12       0  600.85     .05       0  667.04     .06       0
Bank Sta=600.85,667.04
XS Rating Curve= 0 ,0
Exp/Cntr=0.3,0.1

Type RM Length L Ch R = 1 ,0.8392  ,31,26.62,20.23
BEGIN DESCRIPTION:
BB03C (SEM 2019)
END DESCRIPTION:
XS GIS Cut Line= 4
  571436.1329036 5425719.4961831  570876.0476036 5425643.0251831
  570656.8206036 5425761.5106831  569960.8786036 5425819.0884831
#Sta/Elev= 30
       0  104.37   22.97  106.96   50.94  107.48   88.89  104.65  125.84  105.04
  149.81  106.82  205.74  104.73   233.7  105.82  321.59  104.68  339.57  107.88
  355.55  109.24  466.41  114.54  510.35  113.09   554.3  109.96  573.26  106.74
  581.23  102.74  595.19  102.51  610.14   98.53  641.23   94.34  658.29   95.69
  672.75   95.52  694.87    98.4  812.49  100.41  887.41   99.57   895.4   98.38
  913.39   99.72  947.35   100.3 1155.16  101.94 1359.96  100.59 1512.82  101.55
#Mann= 3 , 0 , 0
       0     .12       0  610.14     .05       0  694.87     .06       0
Bank Sta=610.14,694.87
XS Rating Curve= 0 ,0
Exp/Cntr=0.3,0.1