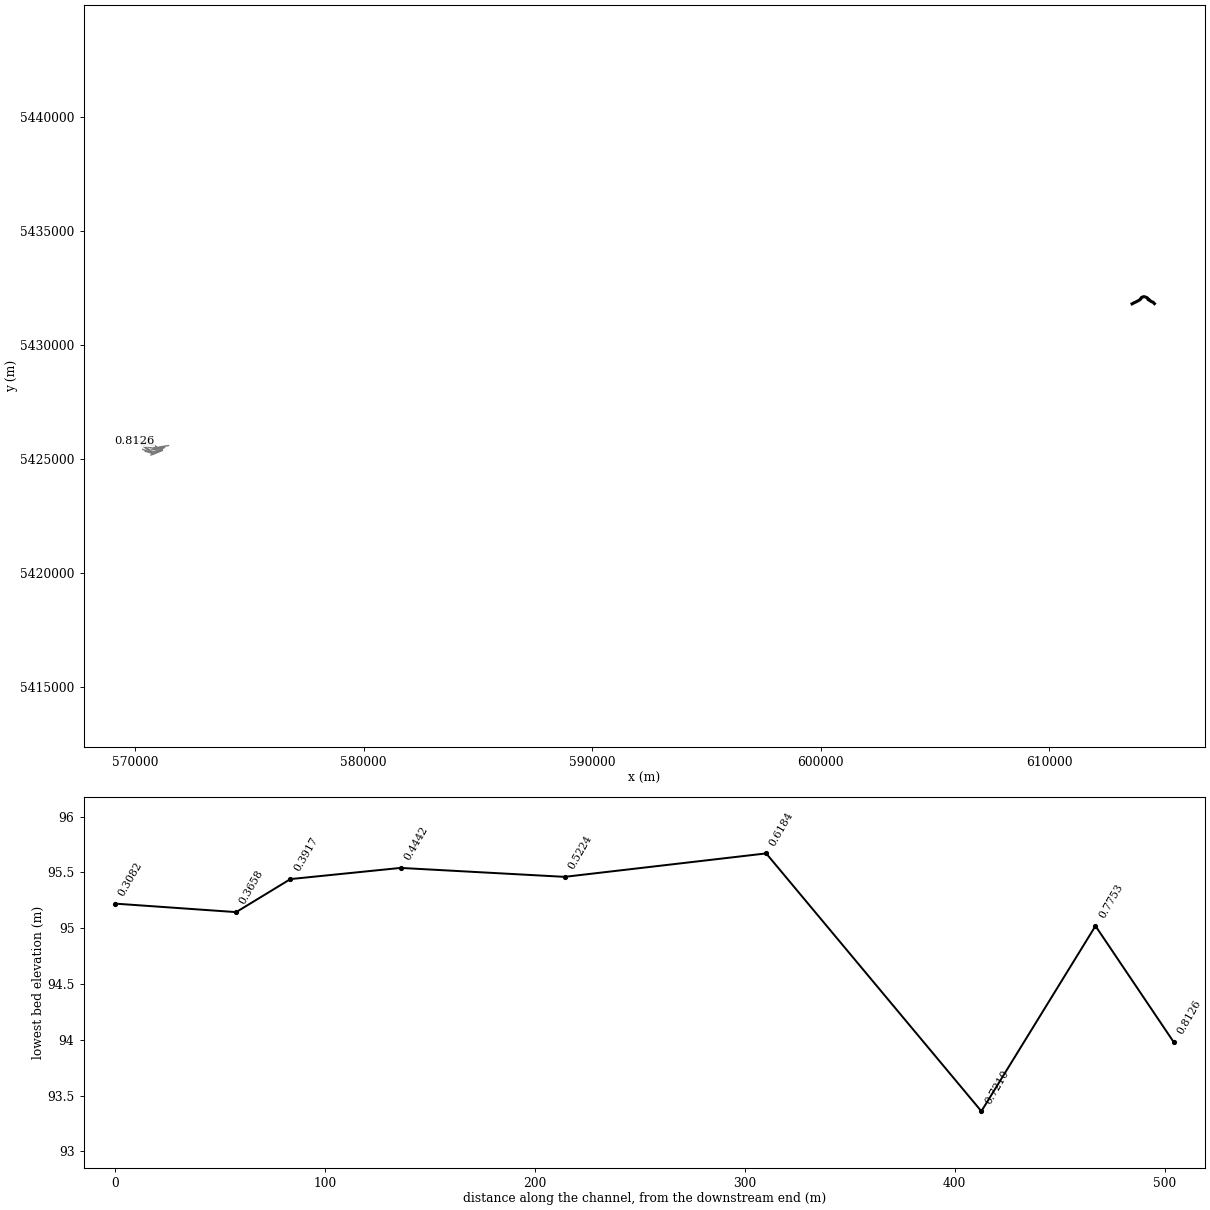
HEC-RAS study Exploits_FMM.prj: Exploits_FMM

--- Exploits_FMM.g01 (geometry) --- (continued)

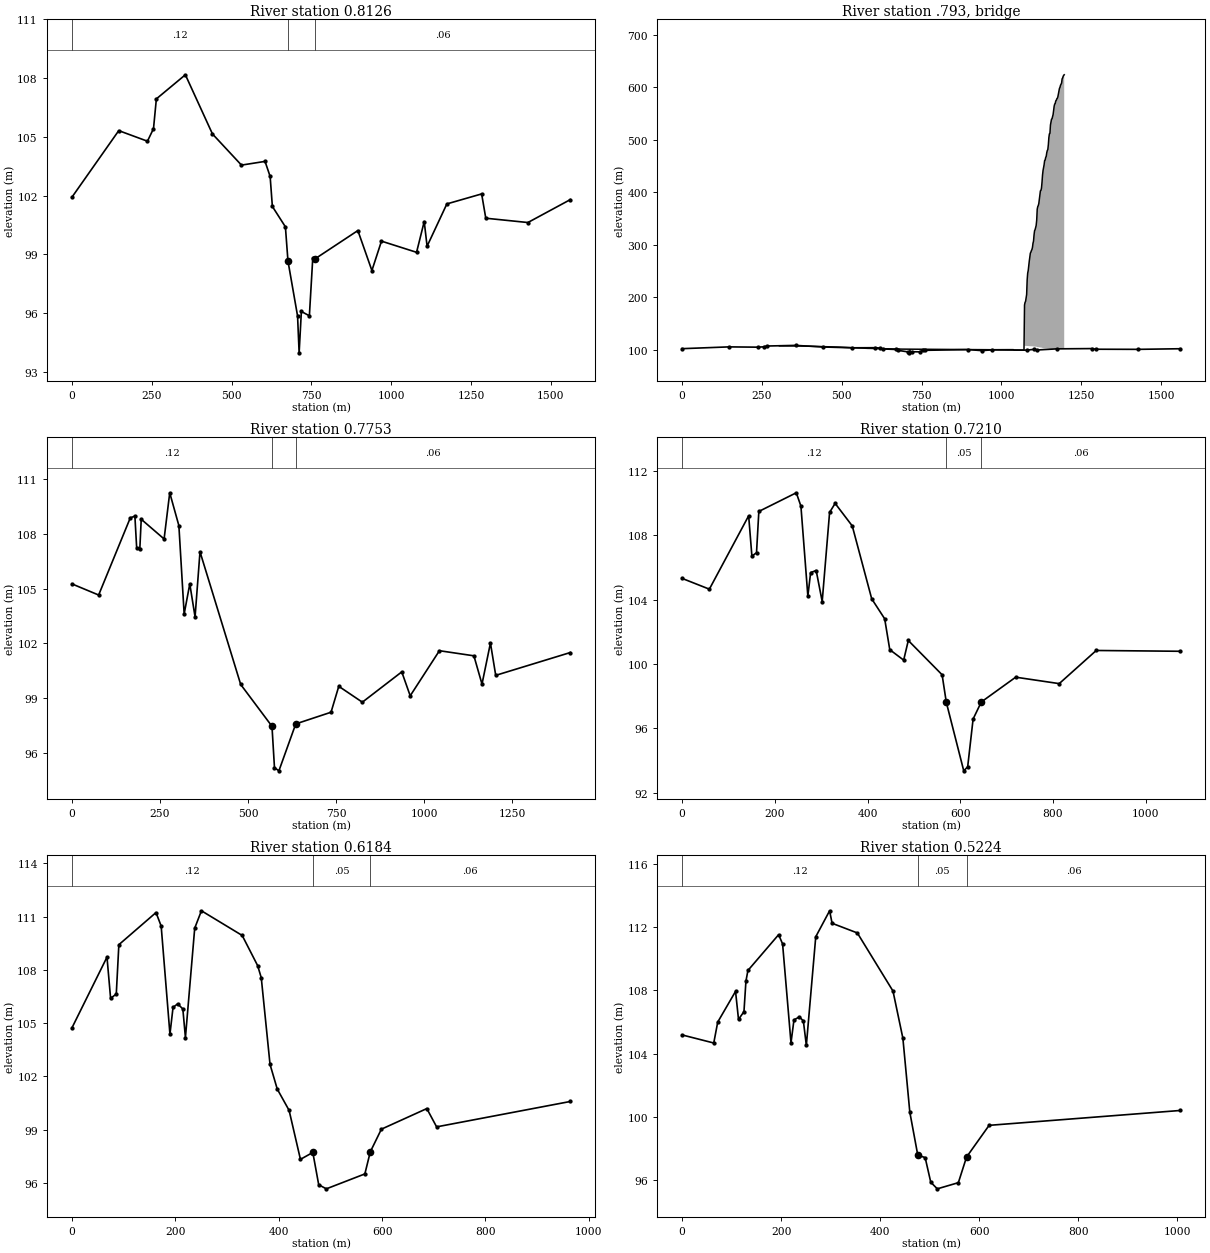
Type RM Length L Ch R = 1 ,0.8126  ,38.46,37.26,37.32
BEGIN DESCRIPTION:
US of Badger Brook TCH Bridge - BB03D (SEM 2019)
END DESCRIPTION:
XS GIS Cut Line= 6
  571453.8272036 5425609.9846831  570965.4253036 5425528.7775831
  570860.9780036 5425602.2767831  570758.8660036 5425683.5759831
  570658.4694036 5425749.7428831  569973.5592036 5425807.8825831
#Sta/Elev= 30
       0  101.92  146.74  105.32  236.57  104.78  255.54  105.42  264.52  106.94
  355.36  108.17   440.2  105.15  531.03  103.56  604.86  103.75  620.83  102.98
  627.81  101.45  668.66  100.41  676.63   98.67  706.73   95.86  711.62   93.98
  718.65   96.09  743.73   95.87  754.34   98.82  760.87   98.77  895.57  100.22
  939.53   98.18   969.5   99.68  1079.4   99.11 1103.37  100.68 1112.37   99.42
 1174.31  101.58  1283.2  102.09 1296.19  100.85 1428.06  100.63 1560.94   101.8
#Mann= 3 , 0 , 0
       0     .12       0  676.63     .05       0  760.87     .06       0
Bank Sta=676.63,760.87
XS Rating Curve= 0 ,0
Exp/Cntr=0.3,0.1

Type RM Length L Ch R = 3 ,.793    ,,,
Node Photo=.\Photos\BB-CR-02.JPG
BEGIN DESCRIPTION:
Badger Brook TCH Bridge
END DESCRIPTION:
Node Name=BB-CR-2
Bridge Culvert--1,0,-1,-1, 0
Deck Dist Width WeirC Skew NumUp NumDn MinLoCord MaxHiCord MaxSubmerge Is_Ogee
13,8.9,1.4,0, 246, 246, , , 0.98, 0, 3,3,,
     305 309.986 311.981 318.961 324.945 352.867 365.832 370.818 379.793 388.768
 395.749 403.727 405.721 408.713 410.707 414.696 422.674 426.663  438.63 446.608
 448.602 452.591  456.58 466.552 487.494 492.481 494.475 498.464 506.442 513.423
 522.398 523.395 527.384 538.353 552.303 561.267 566.247 572.224 580.192 581.188
 586.168  588.16 595.133 599.117 601.109 610.073 624.018  630.99 631.986 647.923
 653.899 658.879 659.875  663.86 667.844 675.812  683.78  687.76 688.755  693.73
 694.725  697.71 698.705  701.69 706.665  711.64  717.61   719.6  723.58  725.57
  727.56  735.52  737.51 740.495 742.485  743.48 746.465  747.46 752.434 753.429
 754.424 758.404 765.369 782.284 792.234 805.169  820.09  839.97 841.958 848.916
 880.724 888.677 907.563 914.521 922.473 934.401 936.389 945.335 952.919 956.404
 956.404 958.061 959.719 961.377 963.035 964.693 966.351 968.009 969.666 971.324
 972.982  974.64 976.298 977.956 979.614 981.271 982.929 984.587 986.245 987.903
 989.561 991.218 992.876 994.534 996.192  997.85 999.5081001.1661002.8231004.481
1006.1391007.7971009.4551011.1131012.7711014.4281016.0861017.7441019.402 1021.06
1022.7181024.3751026.0331027.6911029.3491031.0071032.6651034.323 1035.981037.638
1039.2961040.9541042.612 1044.271045.9281047.5851049.2431050.9011052.5591054.217
1055.8751057.533 1059.191060.8481062.5061064.1641065.822 1067.481069.1381070.795
1072.4531074.1111075.7691077.4271079.0851080.743  1082.41084.0581085.7161087.374
1089.032 1090.691092.3481094.0051095.6631097.3211098.9791100.6371102.2951103.953
 1105.611107.2681108.9261110.5841112.242  1113.91115.5571117.2151118.8731120.531
1122.1891123.8471125.5051127.162 1128.821130.4781132.1361133.7941135.452 1137.11
1138.7671140.4251142.0831143.7411145.3991147.0571148.7151150.372 1152.031153.688
1155.3461157.0041158.662 1160.321161.9771163.6351165.2931166.9511168.6091170.267
1171.9251173.582 1175.241176.8981178.5561180.2141181.872 1183.531185.1871186.845
1188.5031190.1611191.8191193.4771195.1341196.792
 107.249 107.255 107.234 107.226   107.2 107.102  107.02 106.962 106.894 106.774
 106.704 106.567 106.564 106.495  106.49 106.411 106.303 106.212 106.032 105.842
 105.826 105.725 105.677 105.472 104.964 104.832 104.812 104.699  104.52 104.318
 104.099 104.047 103.952 103.634 103.272 103.028 102.915  102.75 102.569 102.528
 102.452   102.4 102.292 102.203 102.189 102.024   101.8 101.668 101.668 101.398
 101.315 101.272 101.293 101.223 101.203 101.105 101.082 101.071 101.068 101.053
 101.051 101.042 101.039 101.031 101.016 101.002 100.985 100.979 100.968 100.962
 100.956 100.933 100.928 100.919 100.913 100.911 100.902 100.899 100.885 100.882
 100.754 100.748 100.784 100.726 100.656 100.619 100.604 100.479 100.448 100.415
 100.228  100.17 100.073 100.057  99.994  99.934  99.898  99.879  99.918  99.916
   99.92  99.925  99.931  99.937  99.936  99.941  99.951  99.957  99.963   99.96
  99.962  99.962  99.964  99.971  99.972  99.979  99.986   99.99  99.994     100
 100.007 100.004 100.015 100.024 100.017 100.013 100.017 100.017 100.027 100.042
  100.05 100.062 100.062 100.053 100.053  100.06 100.057 100.069 100.068 100.067
 100.074 100.061  100.06 100.065 100.068 100.072 100.067 100.068 100.077 100.073
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                                                  99.282  99.271  99.268  99.253
  99.251  99.242  99.239  99.231  99.216  99.202  99.185  99.179  99.168  99.162
  99.156  99.133  99.128  99.119  99.113  99.111  99.102  99.099  99.085  99.082
     185 189.986 191.981 198.961 204.945 232.867 245.832 250.818 259.793 268.768
 275.749 283.727 285.721 288.713 290.707 294.696 302.674 306.663  318.63 326.608
 328.602 332.591  336.58 346.552 367.494 372.481 374.475 378.464 386.442 393.423
 402.398 403.395 407.384 418.353 432.303 441.267 446.247 452.224 460.192 461.188
 466.168  468.16 475.133 479.117 481.109 490.073 504.018  510.99 511.986 527.923
 533.899 538.879 539.875  543.86 547.844 555.812  563.78  567.76 568.755  573.73
 574.725  577.71 578.705  581.69 586.665  591.64  597.61   599.6  603.58  605.57
  607.56  615.52  617.51 620.495 622.485  623.48 626.465  627.46 632.434 633.429
 634.424 638.404 645.369 662.284 672.234 685.169  700.09  719.97 721.958 728.916
 760.724 768.677 787.563 794.521 802.473 814.401 816.389 825.335 832.919 836.404
 836.404 838.061 839.719 841.377 843.035 844.693 846.351 848.009 849.666 851.324
 852.982  854.64 856.298 857.956 859.614 861.271 862.929 864.587 866.245 867.903
 869.561 871.218 872.876 874.534 876.192  877.85 879.508 881.166 882.823 884.481
 886.139 887.797 889.455 891.113 892.771 894.428 896.086 897.744 899.402  901.06
 902.718 904.376 906.033 907.691 909.349 911.007 912.665 914.323 915.981 917.638
 919.296 920.954 922.612  924.27 925.928 927.585 929.243 930.901 932.559 934.217
 935.875 937.533  939.19 940.848 942.506 944.164 945.822  947.48 949.138 950.795
 952.453 954.111 955.769 957.427 959.085 960.743   962.4 964.058 965.716 967.374
 969.032  970.69 972.348 974.005 975.663 977.321 978.979 980.637 982.295 983.953
  985.61 987.268 988.926 990.584 992.242   993.9 995.558 997.215 998.8731000.531
1002.1891003.8471005.5051007.162 1008.821010.4781012.1361013.7941015.452 1017.11
1018.7671020.4251022.0831023.7411025.3991027.0571028.7151030.372 1032.031033.688
1035.3461037.0041038.662 1040.321041.9771043.6351045.2931046.9511048.6091050.267
1051.9251053.582 1055.241056.8981058.5561060.2141061.872 1063.531065.1871066.845
1068.5031070.1611071.8191073.4771075.1341076.792
 107.249 107.255 107.234 107.226   107.2 107.102  107.02 106.962 106.894 106.774
 106.704 106.567 106.564 106.495  106.49 106.411 106.303 106.212 106.032 105.842
 105.826 105.725 105.677 105.472 104.964 104.832 104.812 104.699  104.52 104.318
 104.099 104.047 103.952 103.634 103.272 103.028 102.915  102.75 102.569 102.528
 102.452   102.4 102.292 102.203 102.189 102.024   101.8 101.668 101.668 101.398
 101.315 101.272 101.293 101.223 101.203 101.105 101.082 101.071 101.068 101.053
 101.051 101.042 101.039 101.031 101.016 101.002 100.985 100.979 100.968 100.962
 100.956 100.933 100.928 100.919 100.913 100.911 100.902 100.899 100.885 100.882
 100.754 100.748 100.784 100.726 100.656 100.619 100.604 100.479 100.448 100.415
 100.228  100.17 100.073 100.057  99.994  99.934  99.898  99.879  99.918  99.916
   99.92  99.925  99.931  99.937  99.936  99.941  99.951  99.957  99.963   99.96
  99.962  99.962  99.964  99.971  99.972  99.979  99.986   99.99  99.994     100
 100.007 100.004 100.015 100.024 100.017 100.013 100.017 100.017 100.027 100.042
  100.05 100.062 100.062 100.053 100.053  100.06 100.057 100.069 100.068 100.067
 100.074 100.061  100.06 100.065 100.068 100.072 100.067 100.068 100.077 100.073
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                                                  99.282  99.271  99.268  99.253
  99.251  99.242  99.239  99.231  99.216  99.202  99.185  99.179  99.168  99.162
  99.156  99.133  99.128  99.119  99.113  99.111  99.102  99.099  99.085  99.082
Pier Skew, UpSta & Num, DnSta & Num=  ,713.45, 3 ,594.45, 3 , 3 , 3 , 0 ,,
    1.38    1.38    2.59
       0    95.4   101.1
    1.38    1.38    2.59
       0    95.4   101.1
BR Coef=-1 , 0 , 0 ,, 0 ,,,0.8,-1,,0,
WSPro=,,,, 1 ,,,, 0 ,,,, 0 ,,,,-1 ,-1 ,-1 , 0 , 0 , 0 , 0 , 0
BC Design=,, 0 ,, 0 ,,,,,,
BC HTab HWMax=107
BC Use User HTab Curves=0
BC User HTab FreeFlow(D)= 0

Type RM Length L Ch R = 1 ,0.7753  ,49.06,54.37,66.47
BEGIN DESCRIPTION:
DS of Badger Brook TCH Bridge - BB02 (SEM 2016)
END DESCRIPTION:
XS GIS Cut Line= 5
  571291.7718036 5425553.7127831  570930.0307036 5425493.2930831
  570857.8325036 5425557.5163831  570648.9210036 5425724.5733831
  569967.0463036 5425784.4468831
#Sta/Elev= 30
       0  105.26   75.95  104.65  165.89  108.88  178.88  108.97  183.88  107.25
  192.87  107.17  196.87   108.8  261.82  107.72  277.81  110.25  303.79  108.45
  318.78  103.61  334.77  105.26  349.76  103.45  363.75  107.02  479.35   99.75
  568.18   97.46  575.25  95.196 587.834   95.02  635.66   97.59  735.87   98.23
  757.85   99.65   824.8   98.78  936.72  100.44   960.7   99.13 1043.64   101.6
 1141.57  101.32 1164.56   99.77 1188.54  102.02 1203.53  100.25 1415.38   101.5
#Mann= 3 , 0 , 0
       0     .12       0  568.18     .05       0  635.66     .06       0
Bank Sta=568.18,635.66
XS Rating Curve= 0 ,0
Exp/Cntr=0.3,0.1

Type RM Length L Ch R = 1 ,0.7210  ,97.07,102.56,116.89
BEGIN DESCRIPTION:
BB02A (SEM 2019)
END DESCRIPTION:
XS GIS Cut Line= 5
  571267.0254036 5425527.1883831  570914.4535036 5425470.8661831
  570736.9240036 5425595.2409831  570631.5749036 5425645.6255831
  570249.0164036 5425682.7771831
#Sta/Elev= 30
       0  105.32   58.84  104.65  143.61  109.21   150.6   106.7  160.57  106.92
  165.56  109.48  246.34  110.64  256.31  109.81  271.27  104.22  277.26  105.68
  289.22  105.81  302.19  103.88  318.15  109.42  330.11  109.98  367.03  108.58
  408.99  104.05  436.95  102.81  447.94  100.89  477.91  100.24   487.9  101.46
  560.82   99.33  569.86   97.62  607.48   93.36  615.96   93.61  627.67   96.58
  645.36   97.64  719.53   99.18  813.38   98.78  893.24  100.84 1074.94  100.79
#Mann= 3 , 0 , 0
       0     .12       0  569.86     .05       0  645.36     .06       0
Bank Sta=569.86,645.36
XS Rating Curve= 0 ,0
Exp/Cntr=0.3,0.1

Type RM Length L Ch R = 1 ,0.6184  ,83.08,96.04,122.15
BEGIN DESCRIPTION:
BB02B (SEM 2019)
END DESCRIPTION:
XS GIS Cut Line= 5
  571196.4541036 5425504.7467831  570871.7068036 5425456.0267831
  570735.1320036 5425503.4669831  570642.3830036 5425516.7479831
  570268.6150036 5425651.7830831
#Sta/Elev= 30
       0  104.73   67.87  108.72   74.86   106.4   85.84  106.64   90.83  109.42
  162.69  111.23  172.67  110.47  189.64  104.38  195.63  105.89  204.61  106.09
   214.6   105.8  219.59  104.19  237.55  110.35  250.53  111.33  329.38  109.94
  359.29  108.24  366.27  107.56  383.22  102.68  397.18  101.29  420.11  100.09
  442.05   97.33  465.98   97.72  477.39    95.9  492.16   95.67  566.66   96.51
  577.12   97.75  598.61   99.03  686.48  100.19  705.45   99.16  964.07  100.59
#Mann= 3 , 0 , 0
       0     .12       0  465.98     .05       0  577.12     .06       0
Bank Sta=465.98,577.12
XS Rating Curve= 0 ,0
Exp/Cntr=0.3,0.1

Type RM Length L Ch R = 1 ,0.5224  ,89.47,78.16,55.47
BEGIN DESCRIPTION:
BB02C (SEM 2019)
END DESCRIPTION:
XS GIS Cut Line= 5
  571237.5709036 5425502.1812831  570752.7620036 5425426.1249831
  570638.7351036 5425404.1022831  570493.1912036 5425515.4818831
  570303.4755036 5425618.8007831
#Sta/Elev= 30
       0  105.18   63.97  104.67   71.96  105.99  107.94  107.93  113.94  106.16
  124.93  106.65  128.93  108.58  132.93  109.25   194.9  111.51  202.89  110.93
  219.88  104.68  225.88  106.13  236.87  106.32  244.87  106.06  250.87  104.52
  269.86  111.38  297.84  113.02  302.84  112.23  353.81  111.62  425.77  107.95
  445.76  104.97  459.76   100.3  475.75    97.6  490.74   97.43  502.01   95.88
  515.22   95.46  557.75   95.85   574.3   97.47  619.82   99.47 1006.17  100.41
#Mann= 3 , 0 , 0
       0     .12       0  475.75     .05       0   574.3     .06       0
Bank Sta=475.75,574.3
XS Rating Curve= 0 ,0
Exp/Cntr=0.3,0.1

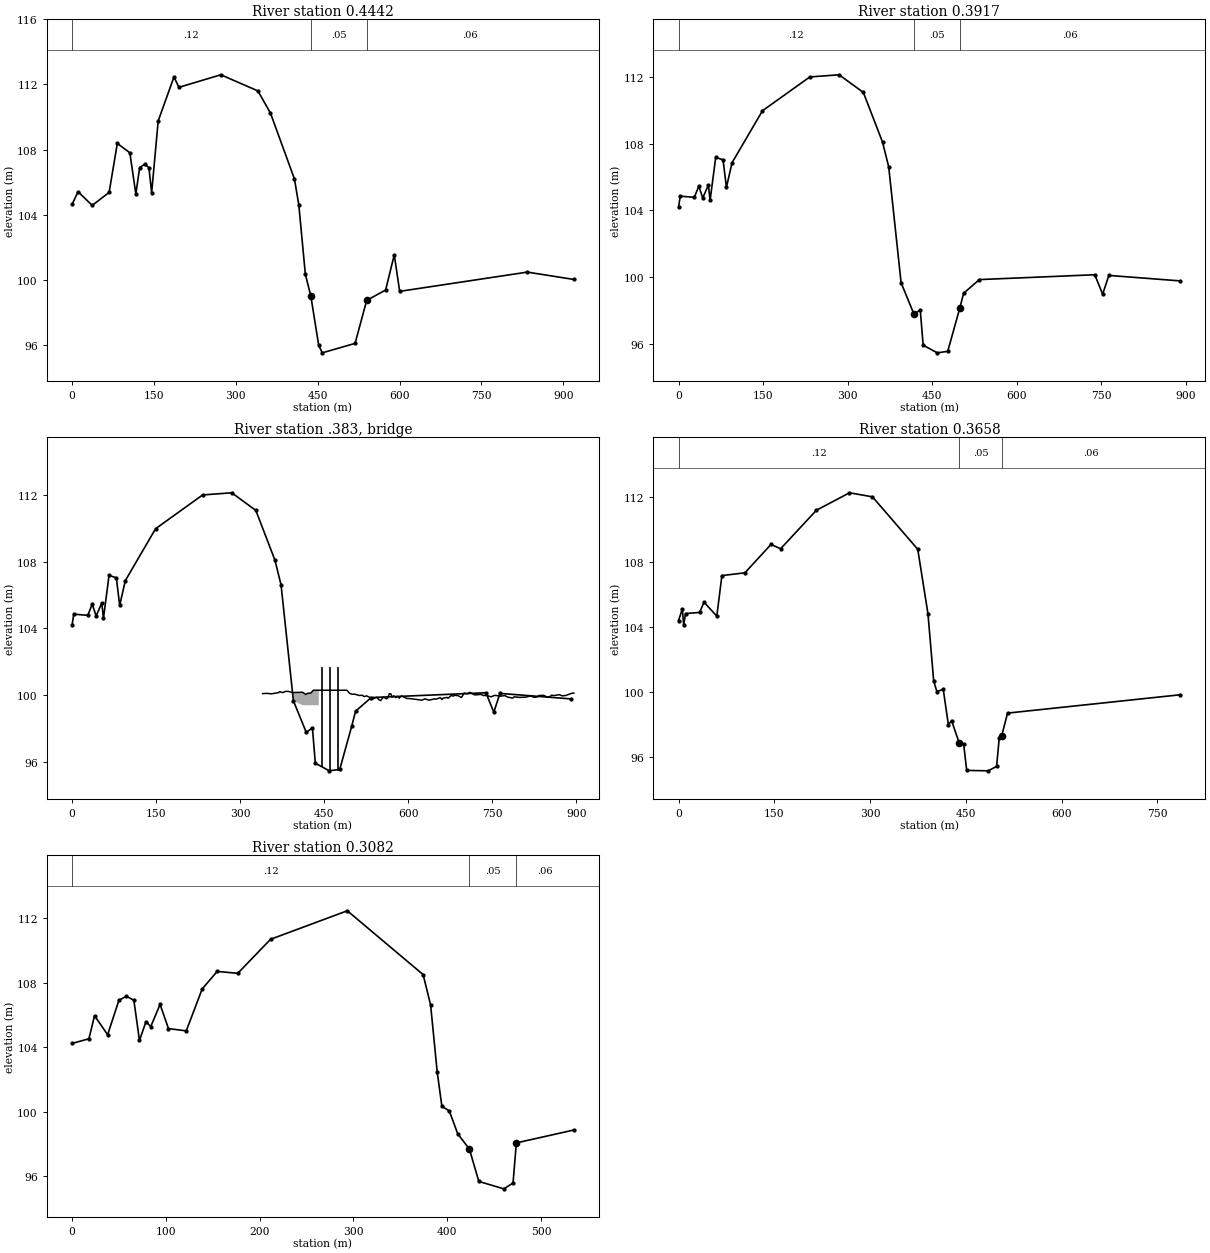
Type RM Length L Ch R = 1 ,0.4442  ,48.45,52.49,52.53
BEGIN DESCRIPTION:
Sunset Dr - BB02D (SEM 2019)
END DESCRIPTION:
XS GIS Cut Line= 6
  571185.3666036 5425462.8027831  570761.3830036 5425332.9131831
  570675.9460036 5425355.9979831  570603.2346036 5425365.3165831
  570427.5679036 5425516.7339831  570361.5645036 5425565.8887831
#Sta/Elev= 30
       0  104.64   10.99  105.42   36.95  104.58   67.91  105.38   82.89  108.38
  105.86  107.81  116.85  105.28  123.84   106.9  132.83   107.1  140.82   106.9
  145.81  105.35   157.8  109.76  186.76  112.46  195.75  111.82  272.65  112.59
  340.56   111.6  363.53  110.24  407.48   106.2  415.47  104.61  427.45  100.36
  437.44   99.03  451.94      96  458.51   95.54  518.61   96.12  539.86   98.76
  574.53   99.39  590.38  101.55  600.29   99.31  834.16  100.49  919.46  100.04
#Mann= 3 , 0 , 0
       0     .12       0  437.44     .05       0  539.86     .06       0
Bank Sta=437.44,539.86
XS Rating Curve= 0 ,0
Exp/Cntr=0.3,0.1

Type RM Length L Ch R = 1 ,0.3917  ,39.49,25.87,32.12
BEGIN DESCRIPTION:
US of Badger Brook T'Railway Bridge - BB02E (SEM 2019)
END DESCRIPTION:
XS GIS Cut Line= 4
  571155.5483036 5425428.1316831  570791.1355036 5425275.7784831
  570682.7561036 5425307.5697831  570325.1607036 5425443.5344831
#Sta/Elev= 30
       0  104.18       3  104.85      28  104.78      36  105.45      43  104.74
      53  105.52      56   104.6      66  107.18      79  107.03      85  105.38
   94.99  106.86  148.99  109.98  232.99  112.01  284.98  112.14  327.98  111.08
  361.98   108.1  372.98  106.61  394.98   99.65  417.97   97.75  428.96   98.02
  434.12    95.9   459.1   95.44  477.75   95.53  499.06   98.12  505.93   99.02
   533.9   99.84  738.67  100.13  752.65   98.96  763.64  100.09   890.5   99.76
#Mann= 3 , 0 , 0
       0     .12       0  417.97     .05       0  499.06     .06       0
Bank Sta=417.97,499.06
XS Rating Curve= 0 ,0
Exp/Cntr=0.3,0.1

Type RM Length L Ch R = 3 ,.383    ,,,
Node Photo=.\Photos\BB-CR-01.JPG
BEGIN DESCRIPTION:
Badger Brook T'Railway Bridge
END DESCRIPTION:
Node Name=BB-CR-1
Bridge Culvert--1,0,-1,-1, 0
Deck Dist Width WeirC Skew NumUp NumDn MinLoCord MaxHiCord MaxSubmerge Is_Ogee
17,3.3,1.4,0, 97, 97, , , 0.98, 0, 3,3,,
     340 347.807 355.614 368.427 370.401 376.224 380.907 386.526 393.956 411.416
 417.285  420.22     426 430.675 433.424 435.257 440.232 460.131 465.105  472.07
  474.06 479.034 482.019 484.009 485.999 487.989 488.984 490.974 494.959 499.947
 503.938 512.917 517.905 520.898 525.886  536.79 543.691 547.634 550.592 555.521
 561.437 563.368 566.265 569.162 571.094 573.991 577.901 580.846 583.791 587.717
 597.533 603.423 624.037 629.911 636.755 646.533 649.467 657.289 660.222 662.178
 669.083 671.069 677.027 680.006 682.985 688.943 694.901 699.866 704.832 709.796
 718.734 729.657 734.622  740.58 747.531 754.482 764.412 772.356 777.321 786.258
 789.237 798.179 810.102  818.05 825.005 830.967 832.954 841.896 847.857 853.819
 855.806  859.78 869.716 874.684 880.645 892.568 895.549
 100.079 100.093 100.065 100.135 100.194 100.138 100.214 100.207 100.141 100.159
 100.027 100.094 100.113 100.281 100.281 100.281 100.281 100.281 100.281 100.281
 100.281 100.281 100.281 100.281 100.281 100.281 100.281  100.27 100.101 100.037
 100.048  99.965   99.98  99.902  99.941  99.757  99.862  99.706  99.662  99.864
  99.767  99.819 100.076 100.052  99.861  99.944  99.841  99.915   99.81  99.941
  99.787  99.779  99.685  99.763  99.685  99.758  99.746  99.834  99.721  99.806
  99.851  99.797  99.978  99.922  99.982  99.953  99.845 100.113 100.065 100.155
  99.998 100.032  99.961  99.966  99.884  99.974  99.926  99.959  99.871  99.809
  99.886  99.852  99.867  99.941  99.851  99.888  99.963  99.974  99.869  99.914
  99.988  99.958 100.016  99.941  99.963 100.107 100.104
                          99.381  99.381  99.381  99.381  99.381  99.381  99.381
  99.381  99.381  99.381  99.381  99.381  99.381  99.381
     354 361.807 369.614 382.427 384.401 390.224 394.907 400.526 407.956 425.416
 431.285  434.22     440 444.675 447.424 449.257 454.232 474.131 479.105  486.07
  488.06 493.034 496.019 498.009 499.999 501.989 502.984 504.974 508.959 513.947
 517.938 526.917 531.905 534.898 539.886  550.79 557.691 561.634 564.592 569.521
 575.437 577.368 580.265 583.162 585.094 587.991 591.901 594.846 597.791 601.717
 611.533 617.423 638.037 643.911 650.755 660.533 663.467 671.289 674.222 676.178
 683.083 685.069 691.027 694.006 696.985 702.943 708.901 713.866 718.832 723.796
 732.734 743.657 748.622  754.58 761.531 768.482 778.412 786.356 791.321 800.258
 803.237 812.179 824.102  832.05 839.005 844.967 846.954 855.896 861.857 867.819
 869.806  873.78 883.716 888.684 894.645 906.568 909.549
 100.079 100.093 100.065 100.135 100.194 100.138 100.214 100.207 100.141 100.159
 100.027 100.094 100.113 100.281 100.281 100.281 100.281 100.281 100.281 100.281
 100.281 100.281 100.281 100.281 100.281 100.281 100.281  100.27 100.101 100.037
 100.048  99.965   99.98  99.902  99.941  99.757  99.862  99.706  99.662  99.864
  99.767  99.819 100.076 100.052  99.861  99.944  99.841  99.915   99.81  99.941
  99.787  99.779  99.685  99.763  99.685  99.758  99.746  99.834  99.721  99.806
  99.851  99.797  99.978  99.922  99.982  99.953  99.845 100.113 100.065 100.155
  99.998 100.032  99.961  99.966  99.884  99.974  99.926  99.959  99.871  99.809
  99.886  99.852  99.867  99.941  99.851  99.888  99.963  99.974  99.869  99.914
  99.988  99.958 100.016  99.941  99.963 100.107 100.104
                          99.381  99.381  99.381  99.381  99.381  99.381  99.381
  99.381  99.381  99.381  99.381  99.381  99.381  99.381
Pier Skew, UpSta & Num, DnSta & Num=  ,444.5, 2 ,464.5, 2 , 0 , 0 , 0 ,,
     2.2     2.2
       0   101.7
     2.2     2.2
       0   101.7
Pier Skew, UpSta & Num, DnSta & Num=  ,459, 2 ,479, 2 , 0 , 0 , 0 ,,
     2.2     2.2
       0   101.7
     2.2     2.2
       0   101.7
Pier Skew, UpSta & Num, DnSta & Num=  ,473.5, 2 ,493.5, 2 , 0 , 0 , 0 ,,
     2.2     2.2
       0   101.7
     2.2     2.2
       0   101.7
BR Coef=-1 , 0 , 0 ,, 0 ,,,0.8,-1,,0,
WSPro=,,,, 1 ,,,, 0 ,,,, 0 ,,,,-1 ,-1 ,-1 , 0 , 0 , 0 , 0 , 0
BC Design=,, 0 ,, 0 ,,,,,,
BC HTab HWMax=107
BC Use User HTab Curves=0
BC User HTab FreeFlow(D)= 0

Type RM Length L Ch R = 1 ,0.3658  ,32.87,57.6,73.77
BEGIN DESCRIPTION:
DS of Badger Brook T'Railway Bridge - BB01 (SEM 2016)
END DESCRIPTION:
XS GIS Cut Line= 5
  571170.5725036 5425420.6496831  570780.8770036 5425249.5959831
  570678.3962036 5425285.4941831  570587.9176036 5425318.7818831
  570436.7640036 5425354.2499831
#Sta/Elev= 30
       0   104.4    5.99  105.12    7.99  104.12   10.99  104.83   32.97   104.9
   39.96  105.53   59.94  104.67   67.93  107.17   103.9  107.34  144.86  109.09
  159.84  108.82  215.79  111.19  267.74  112.27   303.7  112.02  374.63  108.79
  390.62  104.82  399.61  100.67   404.6  100.03  414.59  100.16  422.59   97.98
  427.58   98.24  439.81   96.83   446.5    96.8 451.268  95.172  484.97  95.144
 498.109   95.42  502.29   97.18  505.84   97.26  515.24    98.7  785.84   99.83
#Mann= 3 , 0 , 0
       0     .12       0  439.81     .05       0  505.84     .06       0
Bank Sta=439.81,505.84
XS Rating Curve= 0 ,0
Exp/Cntr=0.3,0.1

Type RM Length L Ch R = 1 ,0.3082  ,113.57,308.24,88.7
BEGIN DESCRIPTION:
Beothuck St - BB01A (SEM 2019)
END DESCRIPTION:
XS GIS Cut Line= 4
  571182.8069036 5425392.3022831  570791.3750036 5425231.5079831
  570740.0146036 5425212.1882831  570686.2015036 5425193.6251831
#Sta/Elev= 30
       0  104.24   17.96  104.53   23.95  105.96   37.93  104.78    49.9  106.91
   57.89  107.17   65.87  106.92   71.86  104.43   78.85  105.59   83.84  105.28
   93.82  106.66   102.8  105.16  121.76  105.02  138.73  107.62   154.7  108.71
  176.65  108.59  211.59   110.7  293.43  112.47  374.27  108.51  382.25  106.63
  389.24  102.49  394.23  100.35  402.21  100.05  411.19   98.63  423.57   97.69
  433.67   95.68  460.31   95.22  470.13   95.58  473.65   98.07  534.97   98.87
#Mann= 3 , 0 , 0
       0     .12       0  423.57     .05       0  473.65     .06       0
Bank Sta=423.57,473.65
XS Rating Curve= 0 ,0
Exp/Cntr=0.3,0.1

River Reach=BF1             ,BF1
Reach XY= 30
  613620.4437036 5431822.7639831  613642.2718036 5431832.2889831
  613692.6750036 5431865.2296831  613771.2565036 5431897.7734831
  613864.1254036 5431948.1766831  613899.0505036 5431961.6704831
  613911.7505036 5431975.9579831  613943.1037036 5431995.0079831
  613955.8037036 5431998.5798831  614004.2225036 5432040.6487831
  614005.4132036 5432062.8737831  614022.0820036 5432093.8300831
  614042.3226036 5432108.1176831  614120.5072036 5432137.8832831
  614167.3385036 5432135.1051831  614254.6512036 5432102.5613831
  614302.6731036 5432072.3987831  614317.8867036 5432040.7810831
  614315.7700036 5432023.3184831  614319.2096036 5432013.2642831
  614326.8826036 5432004.5330831     614347.2555    5432010.6185
     614359.4264    5432003.7393     614365.2472    5431995.2726
     614399.9606    5431981.4084     614417.4756    5431951.9669
     614479.7057    5431914.0785     614505.7408    5431911.1152
  614535.8509036 5431899.4932831  614598.8519133  5431833.881883