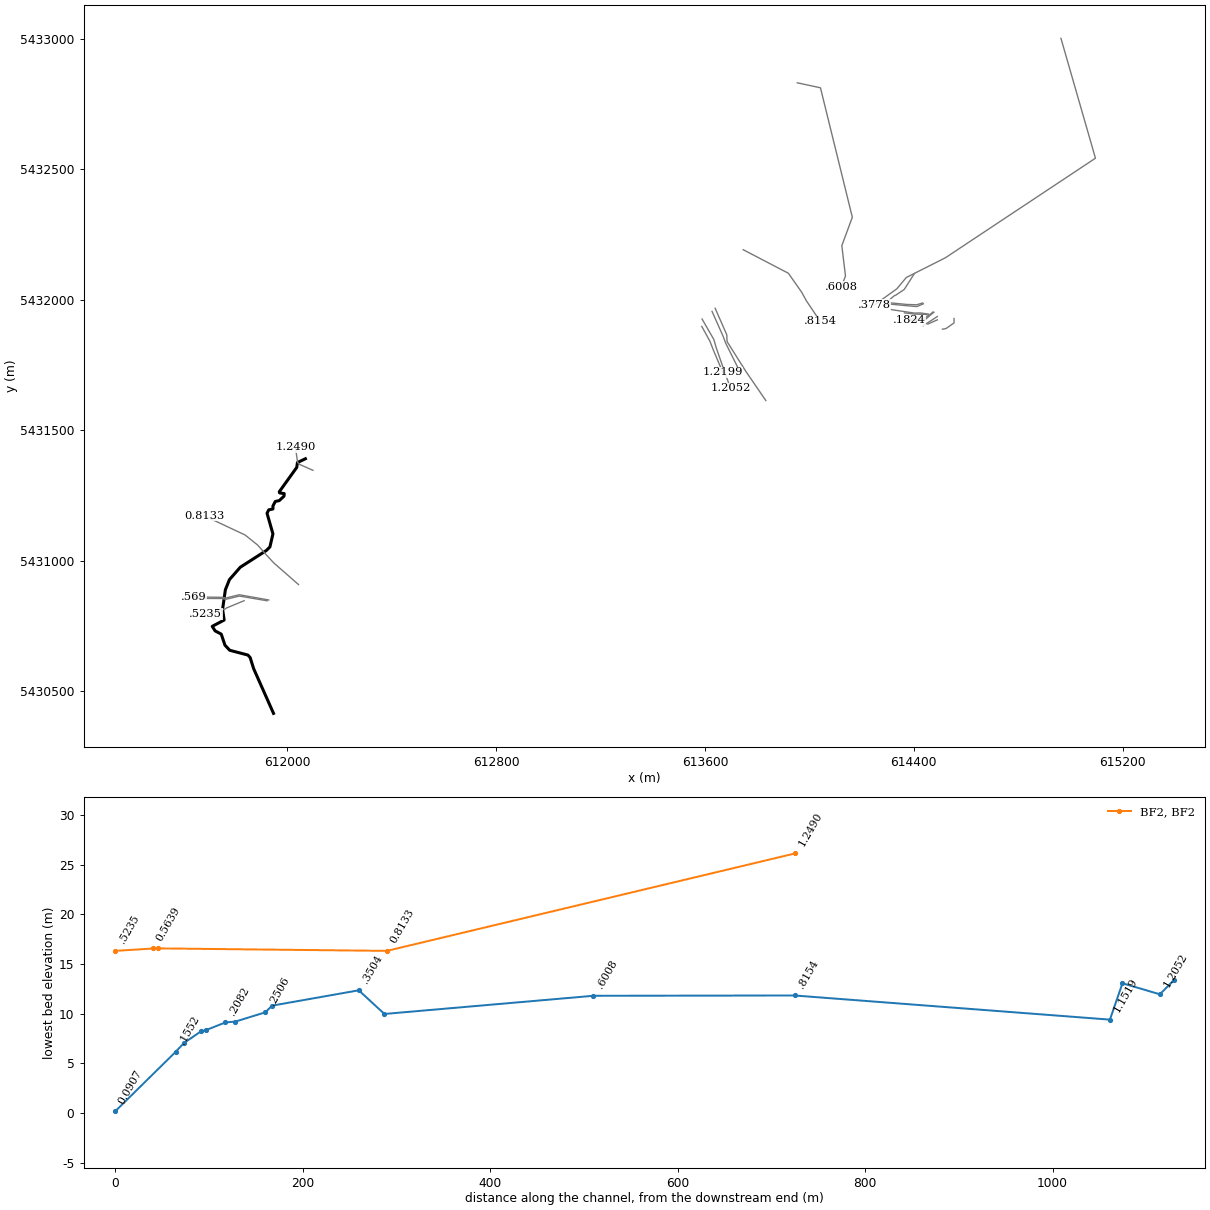
HEC-RAS study Exploits_FMM.prj: Exploits_FMM

--- Exploits_FMM.g01 (geometry) --- (continued)

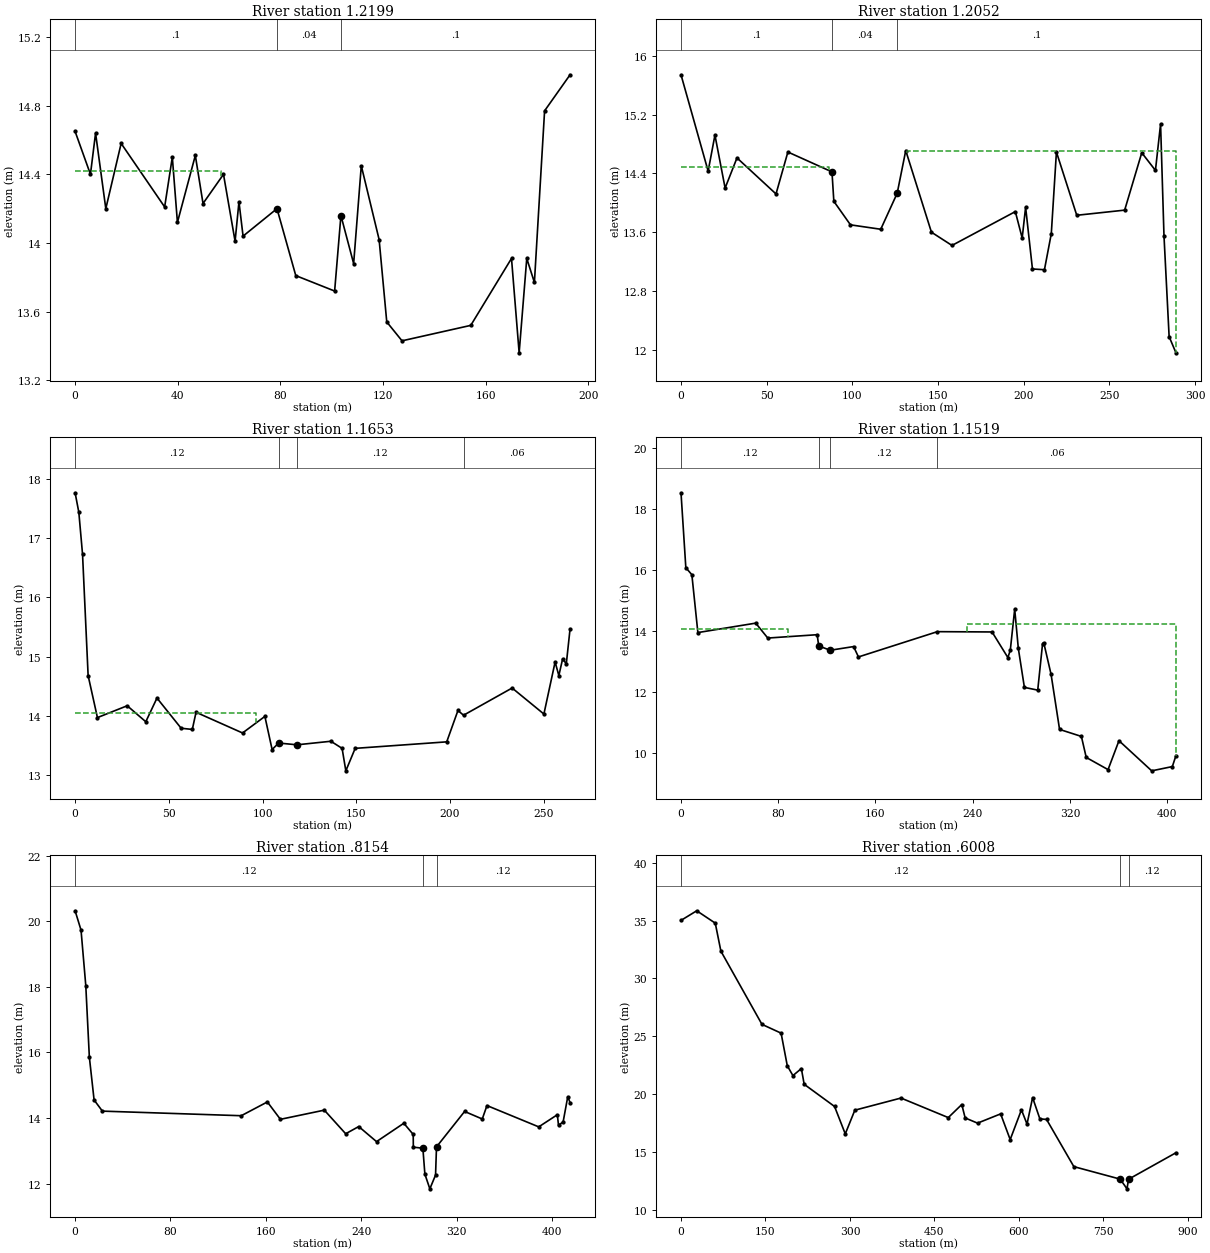
Type RM Length L Ch R = 1 ,1.2199  ,15.46,14.76,14.41
BEGIN DESCRIPTION:
BF1_13 (SEM 2019)
END DESCRIPTION:
XS GIS Cut Line= 4
613587.5312035985431898.65378309613618.6198035985431841.76818309
613633.1719035985431804.72648309613667.5678035985431723.36698309
#Sta/Elev= 30
       0   14.65    5.98    14.4    7.98   14.64   11.97    14.2   17.95   14.58
   34.91   14.21    37.9    14.5   39.89   14.12   46.87   14.51   49.87   14.23
   57.85    14.4   62.37   14.01   63.88   14.24   65.48   14.04    78.7    14.2
   86.03   13.81  101.18   13.72  103.63   14.16  108.59   13.88  111.57   14.45
  118.52   14.02   121.5   13.54  127.45   13.43  154.25   13.52  170.13   13.91
  173.11   13.36  176.08   13.91  179.06   13.77  183.03   14.77  192.96   14.98
#Mann= 3 , 0 , 0
       0      .1       0    78.7     .04       0  103.63      .1       0
#XS Ineff= 2 , 0
           56.78   14.42  111.68           14.44
Permanent Ineff=
       F       F
Bank Sta=78.7,103.63
XS Rating Curve= 0 ,0
Exp/Cntr=0.3,0.1

Type RM Length L Ch R = 1 ,1.2052  ,39.19,39.88,40.19
BEGIN DESCRIPTION:
BF1_12 (SEM 2019)
END DESCRIPTION:
XS GIS Cut Line= 5
  613588.5559036 5431926.8275831  613633.5352036 5431848.7753831
  613642.7956036 5431817.0252831  613675.5105036 5431722.7296831
  613697.9857036 5431660.8120831
#Sta/Elev= 30
       0   15.74   15.84   14.43    19.8   14.92   25.74    14.2   32.67   14.61
   55.44   14.12   62.37   14.69    88.1   14.42   89.19   14.02   98.89    13.7
  116.56   13.64  126.16   14.13  131.15   14.71  146.14    13.6  158.13   13.42
   195.1   13.88   199.1   13.52   201.1   13.94  205.09    13.1  212.09   13.09
  216.09   13.58  219.08   14.69  230.95   13.83   258.9    13.9  268.88   14.68
  276.86   14.44  279.86   15.07  281.85   13.55  284.85   12.18  288.84   11.96
#Mann= 3 , 0 , 0
       0      .1       0    88.1     .04       0  126.16      .1       0
#XS Ineff= 2 , 0
           86.35   14.49  131.59            14.7
Permanent Ineff=
       F       F
Bank Sta=88.1,126.16
XS Rating Curve= 0 ,0
Exp/Cntr=0.3,0.1

Type RM Length L Ch R = 1 ,1.1653  ,14.66,13.36,11.9
BEGIN DESCRIPTION:
BF1_11 (SEM 2019)
END DESCRIPTION:
XS GIS Cut Line= 4
613626.9206035985431955.93188309613669.2540035985431860.68168309
613679.1759035985431834.22328309613737.7902035985431716.39268309
#Sta/Elev= 30
       0   17.77    1.99   17.44    3.97   16.73    6.95   14.68   11.91   13.97
    27.8   14.17   37.72    13.9   43.68    14.3   56.58   13.79   62.54   13.77
   64.53   14.06   89.34   13.71  101.26   13.99  105.12   13.43  108.61   13.54
  118.38   13.51  136.48   13.57  142.46   13.45  144.46   13.07  149.44   13.45
  198.29   13.56  204.28   14.09  207.27   14.01  233.19   14.47  250.14   14.03
  256.12   14.91  258.11   14.68  260.11   14.96   262.1   14.88   264.1   15.47
#Mann= 4 ,-1 , 0
       0     .12       0  108.61     .04       0  118.38     .12       0
  207.27     .06       0
#XS Ineff= 2 , 0
           96.29   14.04
Permanent Ineff=
       F       F
Bank Sta=108.61,118.38
XS Rating Curve= 0 ,0
Exp/Cntr=0.3,0.1

Type RM Length L Ch R = 1 ,1.1519  ,332.77,336.54,338.81
BEGIN DESCRIPTION:
BF1_10 (SEM 2019)
END DESCRIPTION:
XS GIS Cut Line= 5
  613638.8269036 5431967.8380831  613683.4092036 5431866.1055831
  613684.4676036 5431840.1763831  613756.8430036 5431725.5436831
  613832.9235036 5431614.3776831
#Sta/Elev= 30
       0   18.54    3.97   16.08    8.93   15.85   13.88   13.95   61.49   14.26
    71.4   13.77  112.07   13.88  113.31   13.51  122.82   13.37  142.02   13.49
  146.02   13.15  210.99   13.98  255.97   13.97  268.97   13.13  270.97   13.37
  274.59   14.72  277.58   13.43  282.57   12.15  293.55   12.06  297.54   13.59
  298.54   13.61  304.52   12.58  311.51   10.77  329.47   10.54  333.46    9.85
  351.42    9.45   360.4    10.4  387.34    9.41  404.31    9.55   407.3    9.91
#Mann= 4 ,-1 , 0
       0     .12       0  113.31     .04       0  122.82     .12       0
  210.99     .06       0
#XS Ineff= 2 , 0
           88.38   14.06  235.08           14.22
Permanent Ineff=
       F       F
Bank Sta=113.31,122.82
XS Rating Curve= 0 ,0
Exp/Cntr=0.3,0.1

Type RM Length L Ch R = 1 ,.8154   ,217.93,214.57,212.34
BEGIN DESCRIPTION:
BF1_09 (SEM 2019)
END DESCRIPTION:
XS GIS Cut Line= 6
613746.2150035985432192.35038309613919.2764035985432102.15788309
613970.1851035985432029.65148309613988.0445035985431997.10768309
614029.2779035985431935.63238309614040.3000035985431918.50608309
#Sta/Elev= 30
       0   20.32    4.98   19.73    8.96   18.04   11.95   15.86   15.93   14.55
    22.9   14.21   139.4   14.07   161.3   14.49  172.25   13.96  209.09   14.24
  227.01   13.52  237.96   13.74  252.89   13.28  275.78   13.84  283.67    13.5
  283.77   13.11  291.77   13.08  293.45   12.29  297.62   11.84  302.41   12.26
  303.21   13.12  326.79    14.2   341.6   13.97  345.54   14.38  388.97   13.73
  404.59    14.1  405.56   13.78  409.44   13.88  413.32   14.65  415.26   14.47
#Mann= 3 , 0 , 0
       0     .12       0  291.77     .04       0  303.21     .12       0
Bank Sta=291.77,303.21
XS Rating Curve= 0 ,0
Exp/Cntr=0.3,0.1

Type RM Length L Ch R = 1 ,.6008   ,242.44,223.01,186.22
BEGIN DESCRIPTION:
BF1_08 (SEM 2019)
END DESCRIPTION:
XS GIS Cut Line= 6
613953.4903035985432831.86838309614042.2429035995432812.78198309
614164.3982035985432316.82348309614124.1149035985432207.80018309
614138.2135035985432091.39658309614122.3384035985432050.91528309
#Sta/Elev= 30
       0   35.02   27.93   35.85   60.85   34.78   70.83   32.36  143.76   26.03
  177.74   25.27  188.74   22.45  198.74    21.6  213.73   22.21  218.73   20.85
   272.7   18.93   291.7   16.56  308.69   18.61  390.65   19.66  474.62   17.97
  498.61    19.1   504.6   17.94  526.59   17.49  567.58   18.29  584.57   16.07
  604.54   18.64  614.46   17.41  624.37    19.7  637.27   17.86  649.17   17.81
  697.62   13.73  779.88   12.65  791.99   11.81  794.78   12.64  878.96   14.93
#Mann= 3 , 0 , 0
       0     .12       0  779.88     .04       0  794.78     .12       0
Bank Sta=779.88,794.78
XS Rating Curve= 0 ,0
Exp/Cntr=0.3,0.1

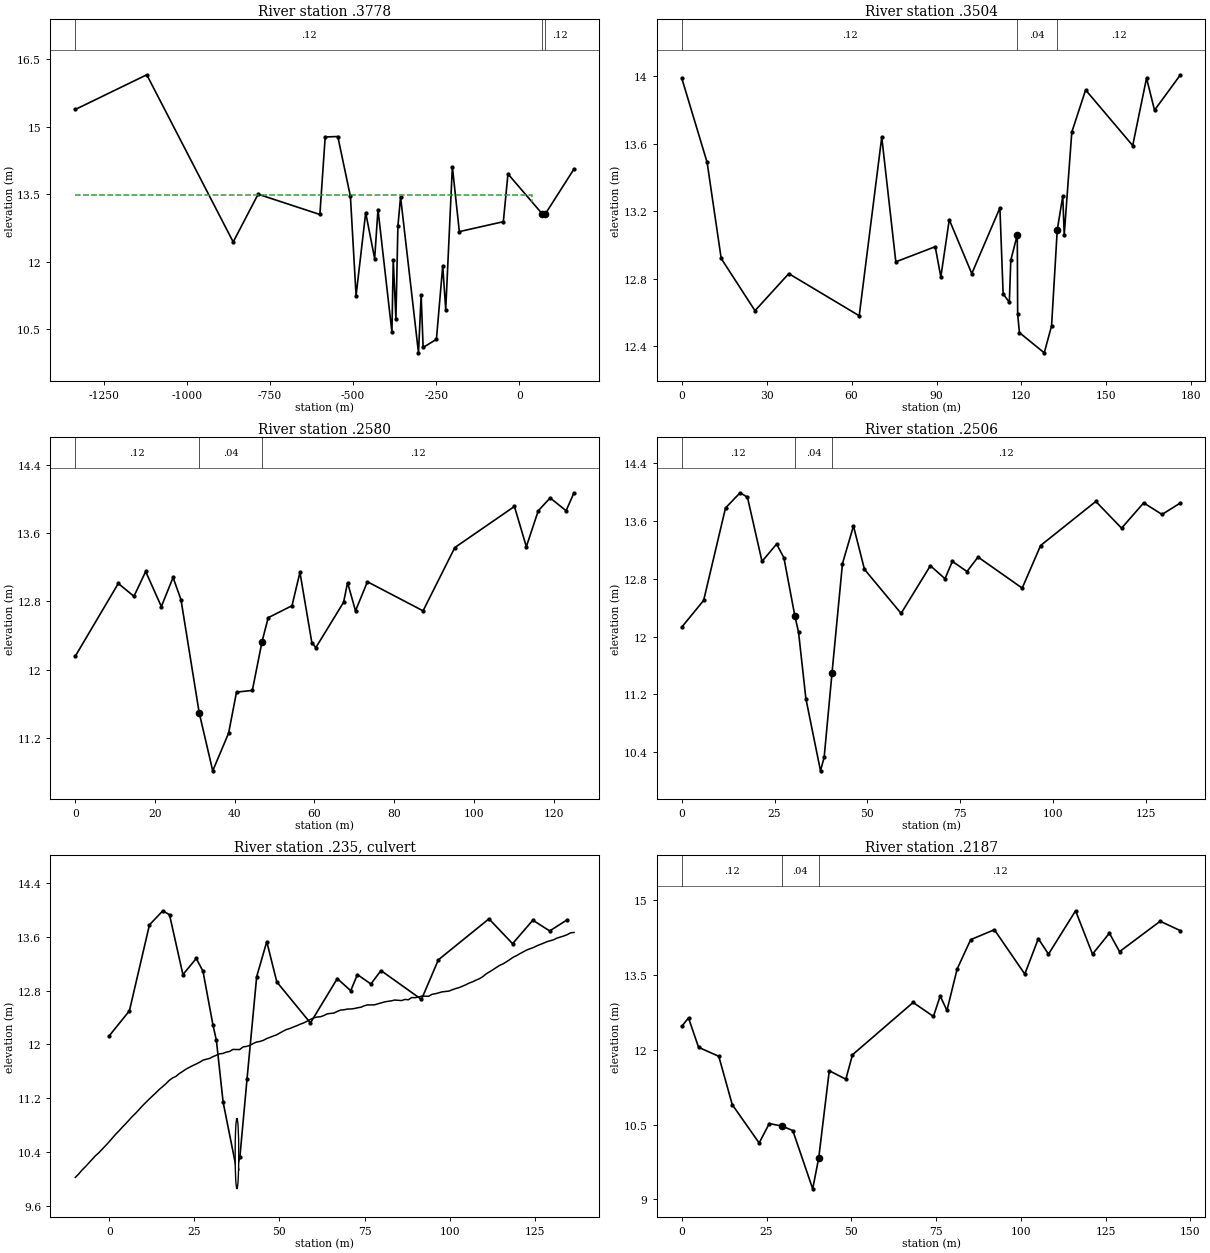
Type RM Length L Ch R = 1 ,.3778   ,24.85,27.39,26.57
BEGIN DESCRIPTION:
BF1_07 (SEM 2019)
END DESCRIPTION:
XS GIS Cut Line= 6
  614963.7549036 5433002.2522831  615095.9513036 5432542.9627831
  614520.9352036 5432161.4327831  614371.1665036 5432085.8660831
  614335.2721036 5432042.7302831  614248.9418036 5431980.6681831
#Sta/Elev= 30
 -1335.5   15.38-1120.53   16.15 -860.57   12.44 -785.66    13.5 -599.91   13.05
 -583.93   14.77 -545.99   14.78 -508.04   13.45 -491.06   11.25  -462.1   13.09
 -435.14   12.07 -425.15   13.16 -383.21   10.44 -379.21   12.04 -371.22   10.74
 -365.23   12.79 -357.24   13.44 -303.31    9.98-295.319   11.26 -289.33    10.1
 -249.38   10.28 -230.41   11.91 -221.42   10.94 -201.45   14.11 -180.47   12.67
  -48.13   12.89-34.2099   13.95   68.11   13.07   77.95   13.06  164.43   14.06
#Mann= 3 , 0 , 0
 -1335.5     .12       0   68.11     .04       0   77.95     .12       0
#XS Ineff= 2 , 0
           37.03   13.49
Permanent Ineff=
       F       F
Bank Sta=68.11,77.95
XS Rating Curve= 0 ,0
Exp/Cntr=0.3,0.1

Type RM Length L Ch R = 1 ,.3504   ,93.05,92.36,83.17
BEGIN DESCRIPTION:
BF1_06 (SEM 2019)
END DESCRIPTION:
XS GIS Cut Line= 6
614402.3058035985432101.01818309614363.1285035985432039.84888309
614330.1486035995432017.65088309614325.1877035985432015.99728309
614308.9819035995432002.43728309614288.1459035995431971.34868309
#Sta/Elev= 30
       0   13.99    8.96   13.49   13.93   12.92   25.87   12.61   37.81   12.83
   62.69   12.58   70.65   13.64   75.62    12.9   89.54   12.99   91.52   12.81
    94.5   13.15  102.46   12.83  112.39   13.22  113.53   12.71  115.72   12.66
  116.24   12.91  118.53   13.06  118.66   12.59  119.28   12.48  128.05   12.36
  130.64   12.52  132.65   13.09   134.6   13.29  135.11   13.06  137.79   13.67
  142.67   13.92   159.3   13.59  164.19   13.99  167.01    13.8  176.18   14.01
#Mann= 3 , 0 , 0
       0     .12       0  118.53     .04       0  132.65     .12       0
Bank Sta=118.53,132.65
XS Rating Curve= 0 ,0
Exp/Cntr=0.3,0.1

Type RM Length L Ch R = 1 ,.2580   ,8.55,7.47,13.26
BEGIN DESCRIPTION:
n/a
END DESCRIPTION:
XS GIS Cut Line= 4
     614433.8533     5431988.162     614410.3054    5431981.2828
     614373.5282    5431982.6058     614310.0281    5431988.6912
#Sta/Elev= 30
       0   12.16   10.79   13.01   14.72   12.86   17.66   13.15   21.59   12.74
   24.53   13.08   26.52   12.82   31.08    11.5   34.48   10.82   38.46   11.26
   40.45   11.74   44.42   11.76   46.85   12.33    48.4   12.61   54.37   12.75
   56.36   13.14   59.34   12.32   60.34   12.26   67.31   12.79   68.31   13.02
    70.3   12.69   73.29   13.03   87.25   12.69   95.22   13.43  110.17   13.91
  113.16   13.44  116.15   13.86  119.14   14.01  123.13   13.86  125.12   14.07
#Mann= 3 , 0 , 0
       0     .12       0   31.08     .04       0   46.85     .12       0
Bank Sta=31.08,46.85
XS Rating Curve= 0 ,0
Exp/Cntr=0.3,0.1

Type RM Length L Ch R = 1 ,.2506   ,31.869,31.91,32.899
BEGIN DESCRIPTION:
n/a
END DESCRIPTION:
XS GIS Cut Line= 4
     614436.7638     5431984.987     614411.3637    5431974.4037
     614363.2094     5431978.637      614305.001    5431984.4578
#Sta/Elev= 30
       0   12.13     5.9    12.5   11.79   13.78   15.72   13.99   17.69   13.93
   21.62   13.04   25.55   13.28   27.52   13.09   30.45   12.29   31.46   12.06
   33.44   11.14   37.38   10.14   38.37   10.33   40.47   11.49    43.3   13.01
   46.26   13.53   49.22   12.93   59.09   12.32   66.98   12.98   70.92    12.8
    72.9   13.04   76.85    12.9   79.82    13.1   91.72   12.67   96.68   13.26
  111.55   13.87  118.49    13.5  124.44   13.85   129.4   13.69  134.36   13.85
#Mann= 3 , 0 , 0
       0     .12       0   30.45     .04       0   40.47     .12       0
Bank Sta=30.45,40.47
XS Rating Curve= 0 ,0
Exp/Cntr=0.3,0.1

Type RM Length L Ch R = 2 ,.235    ,,,
Node Photo=.\Photos\BF1-CR-2.jpg
BEGIN DESCRIPTION:
Sunset Drive 2 Culvert
END DESCRIPTION:
Node Name=BF1-CR-2
Bridge Culvert--1,0,-1,-1, 0
Deck Dist Width WeirC Skew NumUp NumDn MinLoCord MaxHiCord MaxSubmerge Is_Ogee
7,18,1.4,0, 149, 149, , , 0.98, 0, 3,3,,
     -10-9.01426-8.02852-7.04278-6.05704 -5.0713-4.08556-3.09982-2.11409-1.12835
-.142613.84312521.8288642.8146033.800341 4.786085.7718196.7575577.7432968.729034
9.71477310.7005111.6862512.6719913.6577314.64347 15.629216.6149417.6006818.58642
19.57216 20.557921.5436422.5293823.5151124.5008525.4865926.4723327.4580728.44381
29.4295530.4152931.4010232.38676 33.372534.3582435.3439836.3297237.3154638.30119
39.2869340.2726741.2584142.2441543.2298944.2156345.20137 46.187147.1728448.15858
49.1443250.13006 51.115852.1015453.0872754.0730155.0665856.0601557.0537158.04728
59.0408460.0344161.0279862.0215563.0151164.0086765.0022465.9958166.9893867.98294
68.9765169.9700870.9636571.9572172.9507873.94434 74.937975.9314776.9250477.91861
78.9121779.9057480.8993181.8928882.88644   83.8884.8735785.86714 86.860787.85427
88.8478489.8414190.8349791.8285492.8221193.8156794.80923 95.802896.7963797.78994
 98.783599.77707100.7706101.7642102.7578103.7513104.7449105.7385 106.732107.7256
108.7192109.7127110.7063111.6999112.6934 113.687114.6806115.6741116.6677117.6613
118.6548119.6484 120.642121.6355122.6291123.6227124.6162125.6098126.6034127.5969
128.5905129.5841130.5776131.5712132.5648133.5583134.5519135.5455 136.539
   10.02   10.07  10.129  10.179  10.233  10.285  10.342  10.386  10.438  10.492
  10.545  10.604  10.661  10.712  10.767  10.818  10.874  10.928  10.976  11.031
  11.085  11.136  11.185  11.231  11.279  11.328  11.372  11.414  11.465  11.501
  11.524  11.566  11.598  11.632  11.659  11.685  11.708  11.733  11.764  11.779
  11.791  11.817  11.839   11.86  11.866  11.885  11.896  11.926  11.924  11.924
  11.963   11.97  11.985  12.013  12.035  12.044   12.06  12.086  12.106  12.125
  12.143  12.171  12.199  12.223  12.238  12.259  12.278  12.301  12.319  12.344
  12.371  12.395  12.408  12.412   12.43  12.455  12.462  12.467  12.492  12.512
  12.516  12.527  12.528  12.534  12.546  12.554  12.576  12.589  12.588   12.59
  12.605  12.619  12.633  12.642  12.649  12.661  12.657  12.653   12.67  12.665
  12.698  12.696  12.706  12.721  12.718  12.717  12.746  12.755  12.768  12.783
  12.788  12.794  12.814  12.832  12.846  12.867  12.888  12.914  12.932  12.957
  12.978  13.008   13.05   13.08  13.111  13.145  13.177  13.199   13.23  13.263
  13.298  13.322  13.351  13.378  13.406  13.424  13.443  13.468  13.488  13.508
   13.53  13.544  13.559  13.584  13.599  13.615  13.635  13.662  13.667
       77.9857398.9714789.95721610.9429611.9286912.9144313.9001714.8859115.87165
16.8573917.8431218.82886 19.814620.8003421.7860822.7718223.75756 24.743325.72903
26.7147727.7005128.6862529.6719930.6577331.64347 32.629233.6149434.6006835.58642
36.57216 37.557938.5436439.5293840.5151141.5008542.4865943.4723344.4580745.44381
46.4295547.4152848.4010249.38676 50.372551.3582452.3439853.3297254.3154655.30119
56.2869357.2726758.2584159.2441560.2298961.2156362.20137 63.187164.1728465.15858
66.1443267.13006 68.115869.1015370.0872771.0730172.0665873.0601474.0537175.04728
76.0408577.0344178.0279879.0215580.0151181.0086782.0022482.9958183.9893884.98294
85.9765186.9700887.9636588.9572189.9507890.94434 91.937992.9314793.9250494.91861
95.9121796.9057497.8993198.8928899.88644  100.88101.8736102.8671103.8607104.8543
105.8478106.8414 107.835108.8285109.8221110.8157111.8092112.8028113.7964114.7899
115.7835116.7771117.7706118.7642119.7578120.7513121.7449122.7385 123.732124.7256
125.7192126.7127127.7063128.6999129.6934 130.687131.6806132.6741133.6677134.6613
135.6548136.6484 137.642138.6355139.6291140.6227141.6162142.6098143.6034144.5969
145.5905146.5841147.5776148.5712149.5648150.5583151.5519152.5455 153.539
   10.02   10.07  10.129  10.179  10.233  10.285  10.342  10.386  10.438  10.492
  10.545  10.604  10.661  10.712  10.767  10.818  10.874  10.928  10.976  11.031
  11.085  11.136  11.185  11.231  11.279  11.328  11.372  11.414  11.465  11.501
  11.524  11.566  11.598  11.632  11.659  11.685  11.708  11.733  11.764  11.779
  11.791  11.817  11.839   11.86  11.866  11.885  11.896  11.926  11.924  11.924
  11.963   11.97  11.985  12.013  12.035  12.044   12.06  12.086  12.106  12.125
  12.143  12.171  12.199  12.223  12.238  12.259  12.278  12.301  12.319  12.344
  12.371  12.395  12.408  12.412   12.43  12.455  12.462  12.467  12.492  12.512
  12.516  12.527  12.528  12.534  12.546  12.554  12.576  12.589  12.588   12.59
  12.605  12.619  12.633  12.642  12.649  12.661  12.657  12.653   12.67  12.665
  12.698  12.696  12.706  12.721  12.718  12.717  12.746  12.755  12.768  12.783
  12.788  12.794  12.814  12.832  12.846  12.867  12.888  12.914  12.932  12.957
  12.978  13.008   13.05   13.08  13.111  13.145  13.177  13.199   13.23  13.263
  13.298  13.322  13.351  13.378  13.406  13.424  13.443  13.468  13.488  13.508
   13.53  13.544  13.559  13.584  13.599  13.615  13.635  13.662  13.667
BR Coef=-1 , 0 , 0 ,, 0 ,,,0.8,-1,,0,
WSPro=,,,, 1 ,,,, 0 ,,,, 0 ,,,,-1 ,-1 ,-1 , 0 , 0 , 0 , 0 , 0
Culvert=1,1.05,,20,0.011,0.5,1,2,1,9.85,37.5,9.35,39,Culvert #1  , 0 ,8
    37.5      39
BC Culvert Barrel=1,Barrel,0
Culvert Bottom n=0.011
BC Design=,, 0 ,, 0 ,,,,,,
BC Use User HTab Curves=0
BC User HTab FreeFlow(D)= 0

Type RM Length L Ch R = 1 ,.2187   ,10.221,10.44,8.818
BEGIN DESCRIPTION:
n/a
END DESCRIPTION:
XS GIS Cut Line= 4
     614456.0784    5431945.8286     614424.5929    5431950.0619
     614402.1033    5431949.5328     614310.2927    5431963.2911
#Sta/Elev= 30
       0   12.47    1.99   12.64    4.96   12.05   10.92   11.87   14.89    10.9
   22.83   10.13   25.81   10.52   29.54   10.47   32.75   10.38   38.62    9.21
    40.4    9.83   43.51   11.58    48.4   11.41   50.35    11.9   68.24   12.95
   74.23   12.67   76.23   13.08   78.22   12.79   81.22   13.62   85.21   14.21
    92.2   14.41  101.18   13.52  105.17   14.23  108.17   13.92  116.16   14.79
  121.15   13.92  126.14   14.34  129.13   13.97  141.11   14.58   147.1   14.39
#Mann= 3 , 0 , 0
       0     .12       0   29.54     .04       0    40.4     .12       0
Bank Sta=29.54,40.4
XS Rating Curve= 0 ,0
Exp/Cntr=0.3,0.1

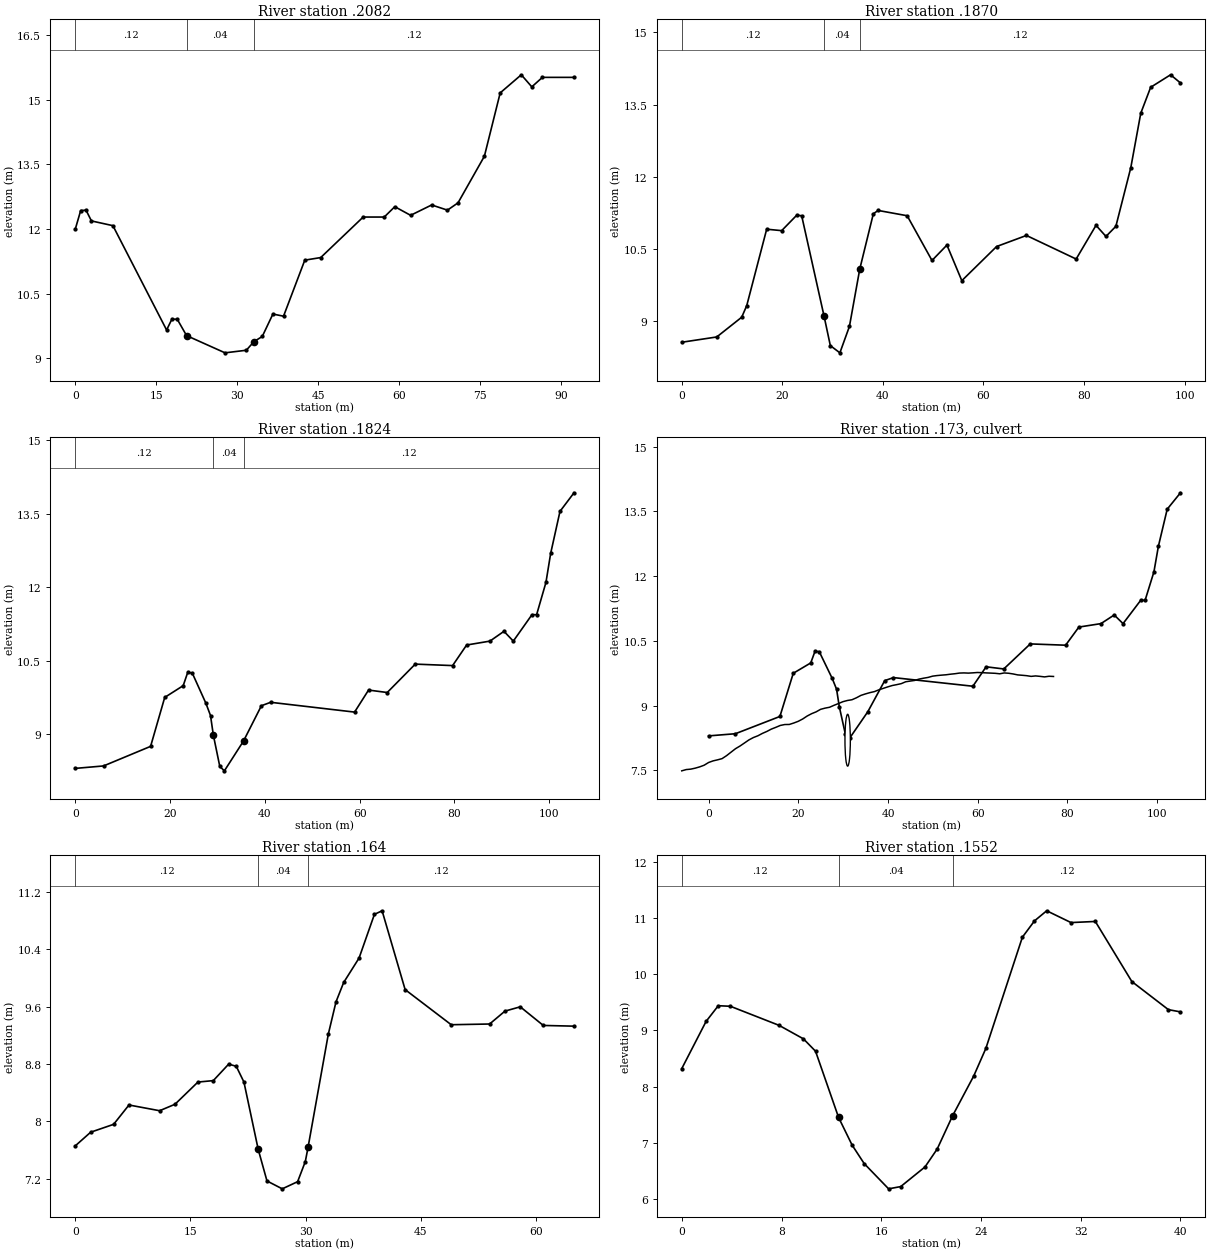
Type RM Length L Ch R = 1 ,.2082   ,17.902,21.24,25.174
BEGIN DESCRIPTION:
n/a
END DESCRIPTION:
XS GIS Cut Line= 4
     614456.0784    5431941.5953     614440.4679    5431944.7703
     614405.0137     5431945.564     614364.2678    5431950.3265
#Sta/Elev= 30
       0      12       1   12.43    1.99   12.44    2.99   12.19    6.97   12.08
   16.92    9.66    17.9    9.91   18.89    9.91   20.62    9.53   27.75    9.13
   31.69    9.19   33.11    9.39   34.65    9.51   36.62   10.03   38.59    9.98
   42.53   11.28   45.48   11.34   53.35   12.28   57.25   12.28   59.21   12.52
   62.14   12.32   66.04   12.56   68.97   12.44   70.93   12.61   75.81   13.69
   78.74   15.16   82.65   15.58    84.6    15.3   86.56   15.52   92.42   15.52
#Mann= 3 , 0 , 0
       0     .12       0   20.62     .04       0   33.11     .12       0
Bank Sta=20.62,33.11
XS Rating Curve= 0 ,0
Exp/Cntr=0.3,0.1

Type RM Length L Ch R = 1 ,.1870   ,4.027,4.62,5.479
BEGIN DESCRIPTION:
n/a
END DESCRIPTION:
XS GIS Cut Line= 4
     614473.4869    5431953.6745     614455.2979    5431938.2483
     614438.6291    5431929.1201     614382.4035    5431925.5563
#Sta/Elev= 30
       0    8.56    6.96    8.67   11.92    9.08   12.92    9.32   16.89   10.91
   19.87   10.88   22.86    11.2   23.85   11.19   28.31     9.1   29.55    8.49
   31.45    8.34   33.35    8.89    35.4   10.08    38.1   11.23   39.05    11.3
   44.83   11.19   49.77   10.26   52.74   10.58    55.7    9.84   62.62   10.55
   68.55   10.78   78.44   10.29   82.39   10.99   84.37   10.76   86.34   10.97
   89.31   12.19   91.29   13.32   93.26   13.86   97.22   14.12   99.19   13.95
#Mann= 3 , 0 , 0
       0     .12       0   28.31     .04       0    35.4     .12       0
Bank Sta=28.31,35.4
XS Rating Curve= 0 ,0
Exp/Cntr=0.3,0.1

Type RM Length L Ch R = 1 ,.1824   ,18.741,18.4,17.99
BEGIN DESCRIPTION:
n/a
END DESCRIPTION:
XS GIS Cut Line= 5
     614477.0731    5431952.7475     614460.5895    5431939.9681
     614456.8125    5431935.6664     614443.2593    5431924.4899
     614382.2727    5431921.1826
#Sta/Elev= 30
       0     8.3    5.96    8.35   15.89    8.75   18.87    9.75   22.77    9.99
   23.72   10.26   24.67   10.25   27.56    9.63   28.53    9.38   29.13    8.98
   30.49    8.34   31.46    8.25    35.5    8.86   39.27    9.58   41.22    9.65
   58.93    9.45   61.88     9.9   65.82    9.85   71.73   10.43   79.61    10.4
   82.57   10.82   87.49    10.9   90.45    11.1   92.42    10.9   96.36   11.44
   97.34   11.44   99.31    12.1   100.3   12.69  102.27   13.55  105.23   13.93
#Mann= 3 , 0 , 0
       0     .12       0   29.13     .04       0    35.5     .12       0
Bank Sta=29.13,35.5
XS Rating Curve= 0 ,0
Exp/Cntr=0.3,0.1

Type RM Length L Ch R = 2 ,.173    ,,,
Node Photo=.\Photos\BF1-CR-1.jpg
BEGIN DESCRIPTION:
Sunset Drive 1 Culvert
END DESCRIPTION:
Node Name=BF1-CR-1
Bridge Culvert--1,0,-1,-1, 0
Deck Dist Width WeirC Skew NumUp NumDn MinLoCord MaxHiCord MaxSubmerge Is_Ogee
6.5,6,1.4,0, 84, 84, , , 0.98, 0, 3,3,,
      -6-5.00105 -4.0021-3.00315-2.00421-1.00526  -.0063.99262811.9915752.990522
3.9894694.9884165.987362 6.986317.9852568.984203 9.98315 10.982111.9810412.97999
13.9789414.9778815.9768316.9757817.9747318.9736719.9726220.9715721.9705122.96946
23.9684124.96735 25.966326.9652527.9641928.9631429.9620930.9610331.9599832.95893
33.9578734.9568235.9557736.9547237.9536638.9526139.95156 40.950541.9494542.94839
43.9473444.9462945.9452446.9441847.9431348.9420849.9410250.9399751.9389252.93787
53.9368154.9357655.9347156.93365 57.932658.9315559.9304960.9294461.9283962.92733
63.9262864.9252265.9241766.9231267.9220768.9210169.9199670.9189171.91785 72.9168
73.91575 74.914775.9136476.91259
  7.4906  7.5202  7.5299  7.5525  7.5824  7.6209  7.6842  7.7213  7.7456  7.7735
  7.8418  7.9227  8.0033   8.065  8.1356  8.2072   8.262  8.3025  8.3575  8.4029
  8.4572  8.4979  8.5418   8.563  8.5645  8.5978  8.6371  8.6913    8.76  8.8145
  8.8567  8.9153  8.9429   8.963  9.0084  9.0495  9.0928  9.1203   9.137  9.1825
  9.2379  9.2717  9.3015  9.3252  9.3663  9.4008  9.4351  9.4666   9.487  9.5097
  9.5535  9.5694  9.5845  9.6154  9.6362  9.6541  9.6834  9.6972  9.7067  9.7152
  9.7287  9.7397  9.7547  9.7584  9.7538  9.7599   9.768  9.7643  9.7586  9.7539
  9.7491   9.738  9.7577    9.75  9.7341  9.7123  9.7039  9.6943  9.6782  9.6886
  9.6786   9.666  9.6811   9.676
      -7-6.00105 -5.0021-4.00316-3.00421-2.00526-1.00631  -.0073.99157491.990522
2.9894693.9884154.987362 5.986316.9852567.984203 8.983159.98209710.9810411.97999
12.9789413.9778814.9768315.9757816.9747317.9736718.9726219.9715720.9705121.96946
22.9684123.96735 24.966325.9652526.9641927.9631428.9620929.9610330.9599831.95893
32.9578733.9568234.9557735.9547236.9536637.9526138.95156 39.950540.9494541.94839
42.9473443.9462944.9452445.9441846.9431347.9420848.9410249.9399750.9389251.93787
52.9368153.9357654.9347155.93365 56.932657.9315558.9304959.9294460.9283961.92733
62.9262863.9252364.9241765.9231266.9220767.9210168.9199669.9189170.91785 71.9168
72.91575 73.914774.9136475.91259
  7.4906  7.5202  7.5299  7.5525  7.5824  7.6209  7.6842  7.7213  7.7456  7.7735
  7.8418  7.9227  8.0033   8.065  8.1356  8.2072   8.262  8.3025  8.3575  8.4029
  8.4572  8.4979  8.5418   8.563  8.5645  8.5978  8.6371  8.6913    8.76  8.8145
  8.8567  8.9153  8.9429   8.963  9.0084  9.0495  9.0928  9.1203   9.137  9.1825
  9.2379  9.2717  9.3015  9.3252  9.3663  9.4008  9.4351  9.4666   9.487  9.5097
  9.5535  9.5694  9.5845  9.6154  9.6362  9.6541  9.6834  9.6972  9.7067  9.7152
  9.7287  9.7397  9.7547  9.7584  9.7538  9.7599   9.768  9.7643  9.7586  9.7539
  9.7491   9.738  9.7577    9.75  9.7341  9.7123  9.7039  9.6943  9.6782  9.6886
  9.6786   9.666  9.6811   9.676
BR Coef=-1 , 0 , 0 ,, 0 ,,,0.8,-1,,0,
WSPro=,,,, 1 ,,,, 0 ,,,, 0 ,,,,-1 ,-1 ,-1 , 0 , 0 , 0 , 0 , 0
Culvert=1,1.2,,9,0.024,0.9,1,2,3,7.6,31,7.4,28,Culvert #1  , 0 ,5
      31      28
BC Culvert Barrel=1,Barrel #1,0
Culvert Bottom n=0.024
BC Design=,, 0 ,, 0 ,,,,,,
BC Use User HTab Curves=0
BC User HTab FreeFlow(D)= 0

Type RM Length L Ch R = 1 ,.164    ,9.916,8.79,7.607
BEGIN DESCRIPTION:
n/a
END DESCRIPTION:
XS GIS Cut Line= 3
     614490.1436    5431936.3697     614466.7279    5431921.1032
     614435.6128    5431901.1007
#Sta/Elev= 30
       0    7.66       2    7.85    4.99    7.96    6.99    8.23   10.98    8.15
   12.98    8.24   15.97    8.55   17.97    8.57   19.97     8.8   20.96    8.77
   21.96    8.55   23.82    7.61   24.96    7.17   26.95    7.06   28.95    7.16
   29.95    7.44   30.31    7.64   32.95    9.22   33.95    9.67   34.95    9.94
   36.95   10.28   38.95   10.89   39.95   10.94   42.95    9.84   48.95    9.35
   53.95    9.36   55.95    9.54   57.94     9.6   60.94    9.34   64.94    9.33
#Mann= 3 , 0 , 0
       0     .12       0   23.82     .04       0   30.31     .12       0
Bank Sta=23.82,30.31
XS Rating Curve= 0 ,0
Exp/Cntr=0.3,0.1

Type RM Length L Ch R = 1 ,.1552   ,65.655,64.53,63.544
BEGIN DESCRIPTION:
n/a
END DESCRIPTION:
XS GIS Cut Line= 2
     614490.3464     5431923.567     614453.7349    5431907.4528
#Sta/Elev= 25
       0    8.32    1.95    9.16    2.93    9.44     3.9    9.43    7.81    9.09
    9.76    8.85   10.73    8.63   12.58    7.45   13.66    6.96   14.63    6.63
   16.59    6.18   17.56    6.22   19.51    6.57   20.49    6.89   21.72    7.48
   23.42    8.19   24.39    8.68   27.32   10.66   28.29   10.95   29.27   11.13
   31.22   10.92   33.17   10.94    36.1    9.87   39.03    9.37      40    9.33
#Mann= 3 , 0 , 0
       0     .12       0   12.58     .04       0   21.72     .12       0
Bank Sta=12.58,21.72
XS Rating Curve= 0 ,0
Exp/Cntr=0.3,0.1

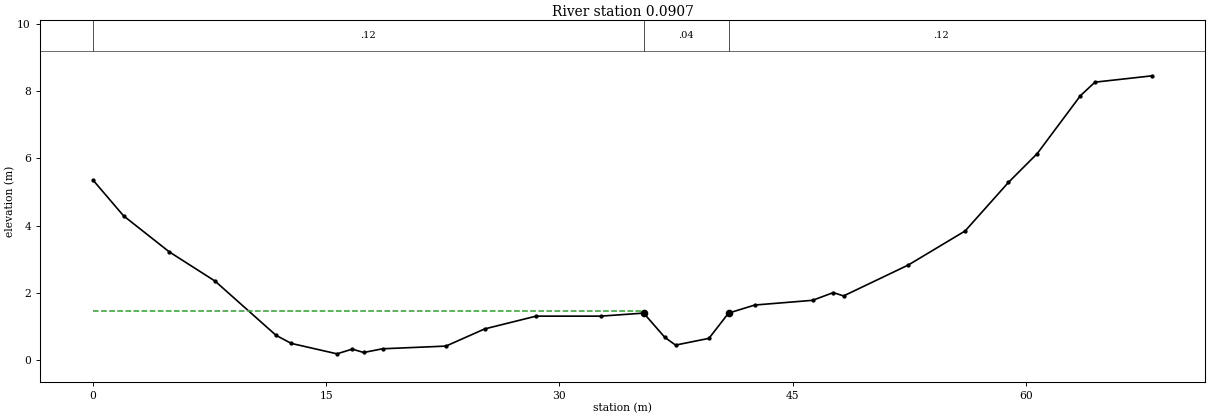
Type RM Length L Ch R = 1 ,0.0907  ,0.48,90.66,3.43
BEGIN DESCRIPTION:
BF1_01 (SEM 2019)
END DESCRIPTION:
XS GIS Cut Line= 5
614553.9892035985431928.64488309614554.2538035985431911.97608309
614527.2663035985431892.92608309614521.7100035995431889.75108309
614509.8037035995431887.89898309
#Sta/Elev= 30
       0    5.35    1.96    4.29     4.9    3.22    7.85    2.35   11.77     .74
   12.75      .5   15.69     .19   16.67     .33   17.41     .23   18.62     .34
    22.7     .42   25.19     .93    28.5    1.31   32.66    1.31   35.42     1.4
   36.78     .68   37.47     .45   39.62     .65   40.88     1.4   42.57    1.64
   46.29    1.78   47.62    2.01   48.28    1.91   52.45    2.83    56.1    3.84
   58.88    5.28   60.74    6.14   63.52    7.86   64.45    8.26   68.15    8.45
#Mann= 3 , 0 , 0
       0     .12       0   35.42     .04       0   40.88     .12       0
#XS Ineff= 2 , 0
           35.32    1.45
Permanent Ineff=
       F       F
Bank Sta=35.42,40.88
XS Rating Curve= 0 ,0
Exp/Cntr=0.3,0.1

River Reach=BF2             ,BF2
Reach XY= 30
612068.6919035995431391.31098309612038.2648035995431376.75888309
612035.6189035985431358.23798309611968.5469035985431264.70758309
611970.1344035985431260.34198309611987.5970035985431257.96068309
611986.8032035995431248.03878309611968.5469035985431230.97318309
611953.4656035985431227.79818309611944.3375035985431210.33558309
611944.3375035985431198.82618309611928.4625035985431195.65118309
611921.7156035985431182.55428309611944.3375035985431103.57598309
611932.8281035985431053.56968309611918.9374035985431039.67898309
611819.3216035985430975.78198309611777.6497035995430928.15688309
611762.1715035985430889.65998309611751.4559035985430814.65048309
611757.4090035995430773.37538309611711.7683035985430749.16588309
611722.8808035985430731.70338309611746.2965035985430719.40028309
611760.5840035985430676.93448309611778.8403035985430657.48758309
611848.2936035985430639.23128309611857.0248035985430629.70628309
611870.5186035985430586.84368309611946.6080034565430415.72603256

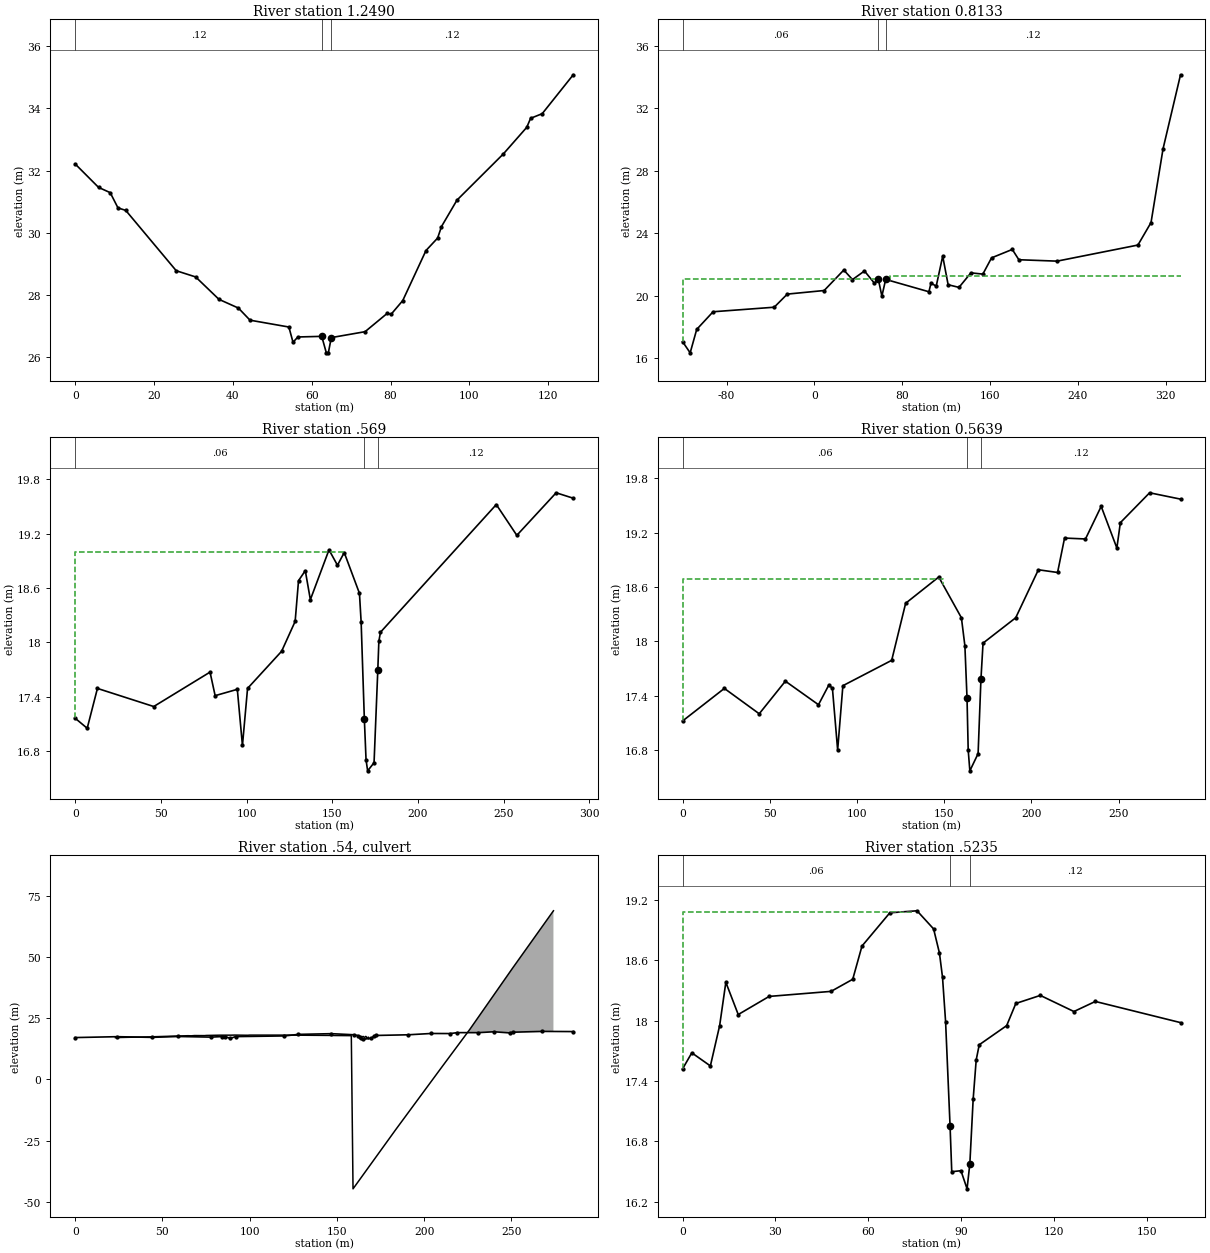
Type RM Length L Ch R = 1 ,1.2490  ,429.1,435.67,433.77
BEGIN DESCRIPTION:
BF2_15 (SEM 2019)
END DESCRIPTION:
XS GIS Cut Line= 5
612097.7603035985431347.06918309612048.1509035985431368.89728309
612039.2211035985431376.83488309612037.5675035995431386.75678309
612030.2914035985431436.36618309
#Sta/Elev= 30
       0   32.21    5.91   31.46    8.87   31.29   10.84    30.8   12.81   30.72
   25.62   28.78   30.55   28.58   36.46   27.86   41.39   27.58   44.34   27.19
    54.2   26.97   55.25   26.48   56.49   26.65   62.54   26.67    63.7   26.14
   64.23   26.15   64.96   26.63   73.53   26.82   79.16   27.41   80.14   27.38
   83.09   27.82   88.99   29.43   91.94   29.83   92.92    30.2   96.85   31.05
  108.65   32.54  114.55   33.39  115.53   33.68  118.48   33.83  126.35   35.08
#Mann= 3 , 0 , 0
       0     .12       0   62.54     .04       0   64.96     .12       0
Bank Sta=62.54,64.96
XS Rating Curve= 0 ,0
Exp/Cntr=0.3,0.1

Type RM Length L Ch R = 1 ,0.8133  ,239.85,244.35,246.44
BEGIN DESCRIPTION:
BF2_14 (SEM 2019)
END DESCRIPTION:
XS GIS Cut Line= 6
  612042.3721036  5430909.238583  611947.3837036 5430992.4194831
  611917.8433036 5431024.2768831  611885.7625036 5431060.6570831
  611837.9985036 5431099.0441831  611680.4250036 5431173.1458831
#Sta/Elev= 30
  -120.1   17.05 -113.14   16.33 -107.18   17.83-92.2599   18.96  -36.59   19.25
  -24.66   20.09    8.93   20.32   26.79   21.63   34.73   21.02   45.64   21.57
   54.77   20.78    58.3   21.03   61.49   19.96   64.97   21.03  104.34   20.24
  106.23   20.79  110.99    20.6   116.9   22.52  121.84   20.69  131.72   20.52
  142.59   21.45  153.47   21.37  161.39   22.41  180.29   22.95  186.26   22.29
  221.09    22.2  294.72   23.23  306.66   24.67   317.6   29.39  333.52   34.13
#Mann= 3 , 0 , 0
  -120.1     .06       0    58.3     .04       0   64.97     .12       0
#XS Ineff= 2 , 0
           57.51   21.04   68.68           21.27
Permanent Ineff=
       F       F
Bank Sta=58.3,64.97
XS Rating Curve= 0 ,0
Exp/Cntr=0.3,0.1

Type RM Length L Ch R = 1 ,.569    ,5.17,5.06,4.92
BEGIN DESCRIPTION:
n/a
END DESCRIPTION:
XS GIS Cut Line= 5
  611928.1530036 5430850.2826831  611815.4352036 5430870.2355831
  611763.5767036 5430857.8000831  611749.8184036 5430860.4459831
  611641.0744036 5430861.7688831
#Sta/Elev= 30
       0   17.16    6.97   17.05   12.94   17.49   45.79   17.29   78.64   17.67
   81.62   17.41   94.56   17.48   97.55   16.86  100.53   17.49   120.4    17.9
   128.3   18.23  130.27   18.68  134.22   18.79  137.18   18.47  148.05   19.02
  152.99   18.85  156.94   18.99  165.82   18.54  166.81   18.22  168.68   17.15
  169.67    16.7   170.6   16.58  174.34   16.67  176.52   17.69  177.14   18.01
  178.07   18.11  245.66   19.52  257.64   19.18  280.58   19.65  290.56   19.59
#Mann= 3 , 0 , 0
       0     .06       0  168.68     .04       0  176.52     .12       0
#XS Ineff= 2 , 0
          156.88      19
Permanent Ineff=
       F       F
Bank Sta=168.68,176.52
XS Rating Curve= 0 ,0
Exp/Cntr=0.3,0.1

Type RM Length L Ch R = 1 ,0.5639  ,39.7,40.39,41.25
BEGIN DESCRIPTION:
US of Kings Road Culvert - n/a
END DESCRIPTION:
XS GIS Cut Line= 6
  611922.0997036 5430847.1581831  611815.6998036 5430865.2084831
  611763.2409036 5430852.5639831  611748.4955036 5430855.9479831
  611671.5016036 5430856.2125831  611640.0161036 5430855.9479831
#Sta/Elev= 30
       0   17.12   23.98   17.48   43.97    17.2   58.96   17.56   77.94    17.3
   83.94   17.52   85.94   17.48   88.93    16.8   91.93   17.51  119.91   17.79
  127.91   18.42  146.89   18.71  159.88   18.26  161.88   17.95   163.1   17.37
  163.77    16.8  164.72   16.57  169.45   16.76  171.07   17.58  172.28   17.98
  191.01   18.26  204.01   18.79  215.01   18.76  219.01   19.14  231.01   19.13
  240.01   19.49     249   19.03     251   19.31  267.78   19.64  285.49   19.57
#Mann= 3 , 0 , 0
       0     .06       0   163.1     .04       0  171.07     .12       0
#XS Ineff= 2 , 0
          149.47   18.69
Permanent Ineff=
       F       F
Bank Sta=163.1,171.07
XS Rating Curve= 0 ,0
Exp/Cntr=0.3,0.1

Type RM Length L Ch R = 2 ,.54     ,,,
Node Photo=.\Photos\BF2-CR-4.jpg
BEGIN DESCRIPTION:
Kings Road Culvert
END DESCRIPTION:
Node Name=BF2-CR-4
Bridge Culvert--1,0,-1,-1, 0
Deck Dist Width WeirC Skew NumUp NumDn MinLoCord MaxHiCord MaxSubmerge Is_Ogee
3.9,34,1.4,0, 258, 258, , , 0.98, 0, 3,3,,
      2323.9738124.9476225.9214326.8952527.8690628.8428729.8166830.79049 31.7643
32.7381133.7119334.6857435.6595536.6333637.6071738.5809839.5547940.5286141.50242
42.4762343.4500444.4238545.3976646.3714847.34529 48.319149.2929150.2667251.24053
52.2143453.1881554.1619655.1357856.0812357.0266857.9721458.9175959.8630460.80849
61.75395 62.699463.6448564.5903165.5357666.4812167.4451668.4091169.3730670.33701
71.3009672.2649173.22885 74.192875.15675 76.120777.08465 78.048679.0125579.96046
80.9083881.8562982.8042183.7521284.7000485.6479586.5958687.5437888.4916989.43961
90.3875291.3354392.2833593.2312694.1791895.12709  96.07597.0229298.0124799.00204
99.99159100.9812101.9707102.9603103.9498104.9394 105.929106.9185107.9081108.8976
109.8872110.8768111.8663112.8559113.8454 114.835115.8246116.8141117.8037118.7932
119.7828120.7724121.7619122.7515 123.741124.7306125.7201126.7097127.6993128.6888
129.6784 130.668131.6575132.6471133.6366134.6262135.6158136.6053137.5949138.5844
 139.574140.5636141.5531142.5427143.5322144.5218145.5031146.4845147.4658148.4471
149.4285150.4098151.3911152.3725153.3538154.3351155.3165156.2978157.2791158.2605
159.2418160.2231161.2045162.1858163.1671164.1485165.1298166.1111167.0925168.0738
169.0551170.0365171.0178171.9991172.9804173.9618174.9439 175.926176.9082177.8903
178.8725179.8546180.8367181.8188 182.801183.7831184.7652185.7474186.7295187.7116
188.6938189.6759190.6581191.6402192.6223193.6044194.5866195.5687196.5508 197.533
198.5235199.5141200.5047201.4952202.4858203.4763204.4669205.4575 206.448207.4386
208.4291209.4197210.4102211.4008212.3914213.3819214.3725215.3631216.3536217.3442
218.3347219.3253220.3158221.3064 222.297223.2875224.2781225.2686226.2345227.2005
228.1664229.1323230.0982231.0641  232.03232.9959233.9618234.9277235.8937236.8596
237.8255238.7914239.7573240.7232241.6891 242.655 243.621244.5869245.5528246.5187
247.4846248.4719249.4592250.4465251.4337 252.421253.4083254.3956255.3829256.3701
257.3574258.3447 259.332260.3193261.3065262.2938263.2811264.2684265.2557 266.243
267.2303268.2175269.2048270.1921271.1794272.1667273.1539274.1412
  17.109  17.129  17.144  17.166  17.175  17.198   17.21   17.23  17.241  17.262
  17.269  17.277  17.281  17.292   17.32   17.34  17.354  17.366  17.365  17.387
  17.403  17.423  17.432  17.437  17.457  17.482    17.5  17.523  17.576  17.647
   17.65   17.67  17.686  17.704  17.708  17.714  17.729  17.758   17.78    17.8
  17.833  17.838   17.88   17.88  17.848  17.835  17.888  17.941  17.939  17.947
  17.939  17.909  17.928  17.918  17.986  17.996   18.02  18.047  18.042   18.05
  18.066  18.101  18.095  18.093  18.092  18.099  18.082  18.071  18.091  18.104
  18.134   18.14  18.125  18.121  18.094   18.07  18.045  18.016  18.069  18.067
  18.126  18.124  18.136  18.119  18.125  18.122  18.104  18.096  18.112  18.112
  18.098  18.111  18.083    18.1  18.103  18.105  18.107  18.104  18.101  18.092
  18.096  18.098  18.126  18.111  18.123  18.123  18.099  18.111    18.1  18.082
  18.075  18.091  18.066  18.066  18.049  18.059  18.046  18.035  18.032  18.033
  18.024  18.017  18.004  18.001  18.004  18.016  17.993  17.974   17.98   17.96
  17.948  17.947  17.944  17.933  17.936  17.943   17.93  17.929   17.92  17.896
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   -54.5-53.5261-52.5523-51.5785-50.6047-49.6309-48.6571-47.6833-46.7095-45.7357
-44.7618 -43.788-42.8142-41.8404-40.8666-39.8928 -38.919-37.9452-36.9713-35.9975
-35.0237-34.0499-33.0761-32.1023-31.1285-30.1547-29.1809 -28.207-27.2332-26.2594
-25.2856-24.3118 -23.338-22.3642-21.4187-20.4733-19.5278-18.5824-17.6369-16.6915
 -15.746-14.8006-13.8551-12.9096-11.9642-11.0187-10.0548-9.09089-8.12694-7.16299
-6.19904-5.23509-4.27114-3.30719-2.34324-1.37929 -.41535.54859831.5125472.460461
3.408376 4.356295.3042046.2521187.2000328.147946 9.0958610.0437710.99169 11.9396
12.8875213.8354314.7833515.7312616.6791717.62709  18.57519.5229220.5124821.50204
 22.491623.4811624.4707125.4602826.4498327.4393928.4289629.4185130.4080731.39763
32.3871933.3767534.3663135.3558736.3454337.3349938.3245539.3141140.3036741.29323
42.2827943.2723544.2619145.2514746.2410347.2305948.2201549.2097150.1992751.18883
52.1783953.1679554.1575155.1470756.1366357.1261958.1157559.1053160.0948761.08443
62.0739963.0635564.0531165.0426666.0322367.0217868.0031268.9844569.9657870.94712
71.9284572.9097873.8911174.8724575.8537876.8351177.8164578.7977879.7791180.76045
81.7417882.7231183.7044484.6857885.6671186.6484587.6297888.6111189.5924590.57378
91.5551192.5364593.5177894.4991195.4804596.4617897.4439198.4260599.40818100.3903
101.3724102.3546103.3367104.3188 105.301106.2831107.2652108.2474109.2295110.2116
111.1938112.1759 113.158114.1402115.1223116.1044117.0866118.0687119.0508 120.033
121.0235122.0141123.0047123.9952124.9858125.9763126.9669127.9575 128.948129.9386
130.9291131.9197132.9102133.9008134.8914135.8819136.8725137.8631138.8536139.8442
140.8347141.8253142.8158143.8064 144.797145.7875146.7781147.7686148.7345149.7005
150.6664151.6323152.5982153.5641  154.53155.4959156.4618157.4277158.3937159.3596
160.3255161.2914162.2573163.2232164.1891 165.155 166.121167.0869168.0528169.0187
169.9846170.9719171.9592172.9465173.9337 174.921175.9083176.8956177.8829178.8701
179.8574180.8447 181.832182.8193183.8065184.7938185.7811186.7684187.7557 188.743
189.7302190.7175191.7048192.6921193.6794194.6667195.6539196.6412
  17.109  17.129  17.144  17.166  17.175  17.198   17.21   17.23  17.241  17.262
  17.269  17.277  17.281  17.292   17.32   17.34  17.354  17.366  17.365  17.387
  17.403  17.423  17.432  17.437  17.457  17.482    17.5  17.523  17.576  17.647
   17.65   17.67  17.686  17.704  17.708  17.714  17.729  17.758   17.78    17.8
  17.833  17.838   17.88   17.88  17.848  17.835  17.888  17.941  17.939  17.947
  17.939  17.909  17.928  17.918  17.986  17.996   18.02  18.047  18.042   18.05
  18.066  18.101  18.095  18.093  18.092  18.099  18.082  18.071  18.091  18.104
  18.134   18.14  18.125  18.121  18.094   18.07  18.045  18.016  18.069  18.067
  18.126  18.124  18.136  18.119  18.125  18.122  18.104  18.096  18.112  18.112
  18.098  18.111  18.083    18.1  18.103  18.105  18.107  18.104  18.101  18.092
  18.096  18.098  18.126  18.111  18.123  18.123  18.099  18.111    18.1  18.082
  18.075  18.091  18.066  18.066  18.049  18.059  18.046  18.035  18.032  18.033
  18.024  18.017  18.004  18.001  18.004  18.016  17.993  17.974   17.98   17.96
  17.948  17.947  17.944  17.933  17.936  17.943   17.93  17.929   17.92  17.896
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BR Coef=-1 , 0 , 0 ,, 0 ,,,0.8,-1,,0,
WSPro=,,,, 1 ,,,, 0 ,,,, 0 ,,,,-1 ,-1 ,-1 , 0 , 0 , 0 , 0 , 0
Multiple Barrel Culv=1,1.05,,34,0.024,0.5,1,2,1,16.54,16.3, 2,Culvert #1  , 0 ,3.9
     165      90   166.5    91.5
BC Culvert Barrel=1,One,0
BC Culvert Barrel=2,Two,0
Culvert Bottom n=0.024
Culvert=1,0.75,,34,0.011,0.5,1,2,1,16.54,168,16.3,88,Culvert #2  , 0 ,3.9
     168      88
BC Culvert Barrel=1,One,0
Culvert Bottom n=0.011
BC Design=,, 0 ,, 0 ,,,,,,
BC Use User HTab Curves=0
BC User HTab FreeFlow(D)= 0

Type RM Length L Ch R = 1 ,.5235   ,3.62,3.45,3.44
BEGIN DESCRIPTION:
DS of Kings Road Culvert - n/a
END DESCRIPTION:
XS GIS Cut Line= 6
  611833.9560036 5430847.4813831  611765.6934036 5430819.1708831
  611759.3368036 5430814.2756831  611737.6475036 5430813.8791831
  611696.3724036 5430792.7124831  611686.3183036 5430796.4166831
#Sta/Elev= 30
       0   17.52       3   17.68    8.99   17.55   11.98   17.95   13.98   18.38
   17.98   18.06   27.96   18.24   47.94   18.29   54.93   18.41   57.92   18.74
   66.91   19.07   75.68   19.09   81.03   18.91   82.92   18.67   83.91   18.43
    84.9   17.99   86.35   16.95   86.89    16.5   89.86   16.51   91.83   16.33
   92.73   16.58    93.8   17.22   94.78   17.61   95.76   17.76  104.61   17.95
  107.57   18.17  115.47   18.25  126.32   18.09  133.23   18.19  160.72   17.98
#Mann= 3 , 0 , 0
       0     .06       0   86.35     .04       0   92.73     .12       0
#XS Ineff= 2 , 0
           73.97   19.08
Permanent Ineff=
       F       F
Bank Sta=86.35,92.73
XS Rating Curve= 0 ,0
Exp/Cntr=0.3,0.1