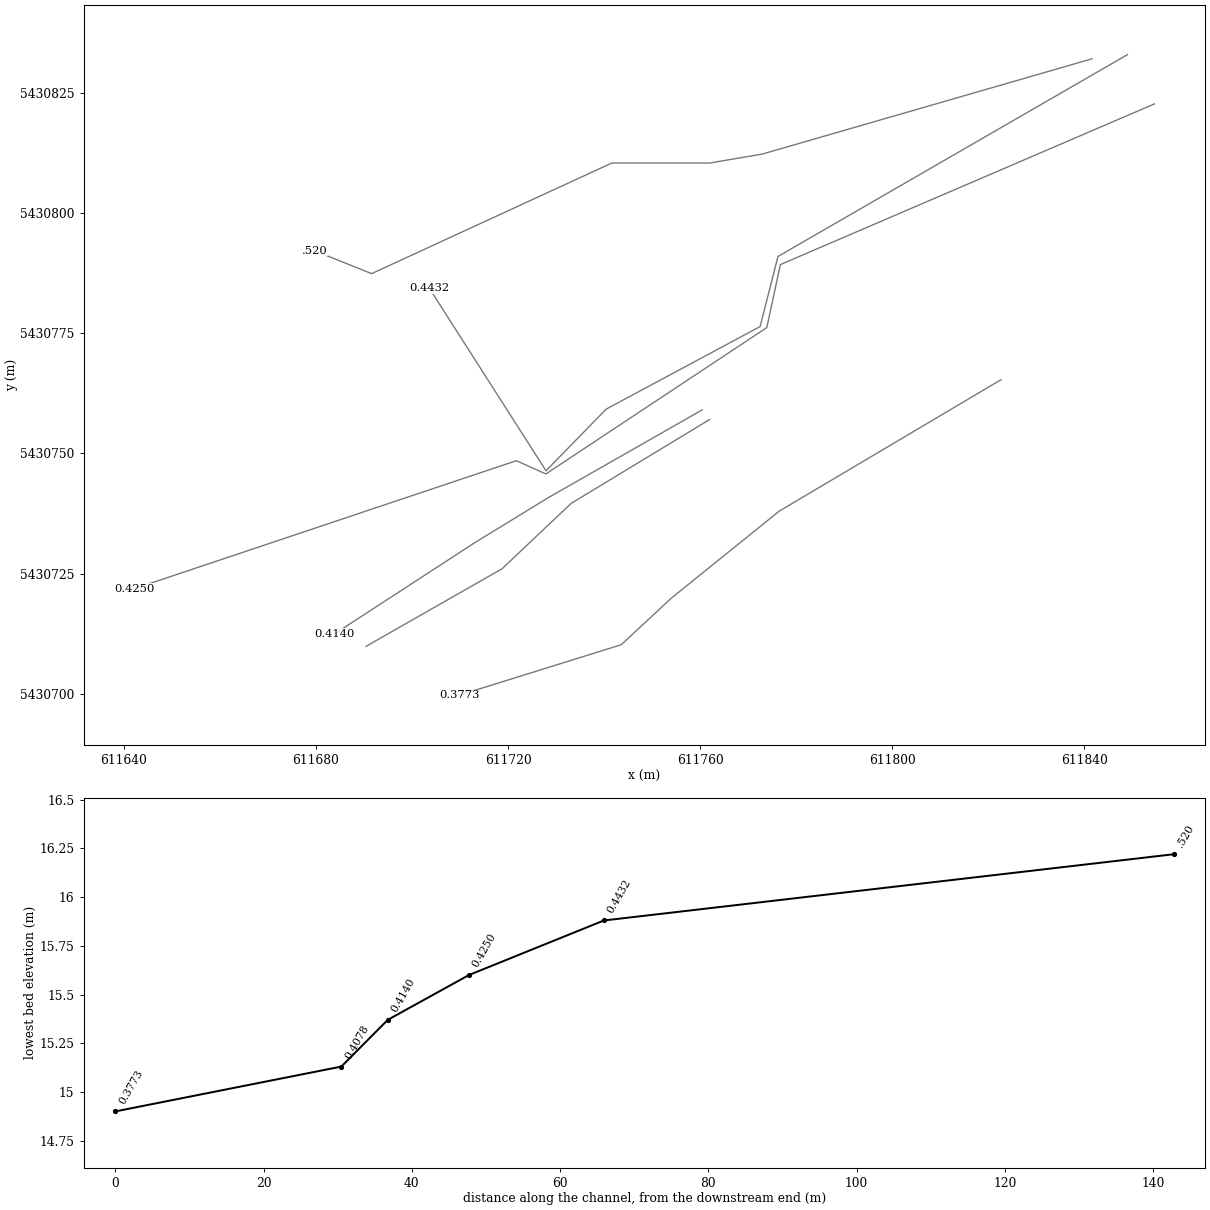
HEC-RAS study Exploits_FMM.prj: Exploits_FMM

--- Exploits_FMM.g01 (geometry) --- (continued)

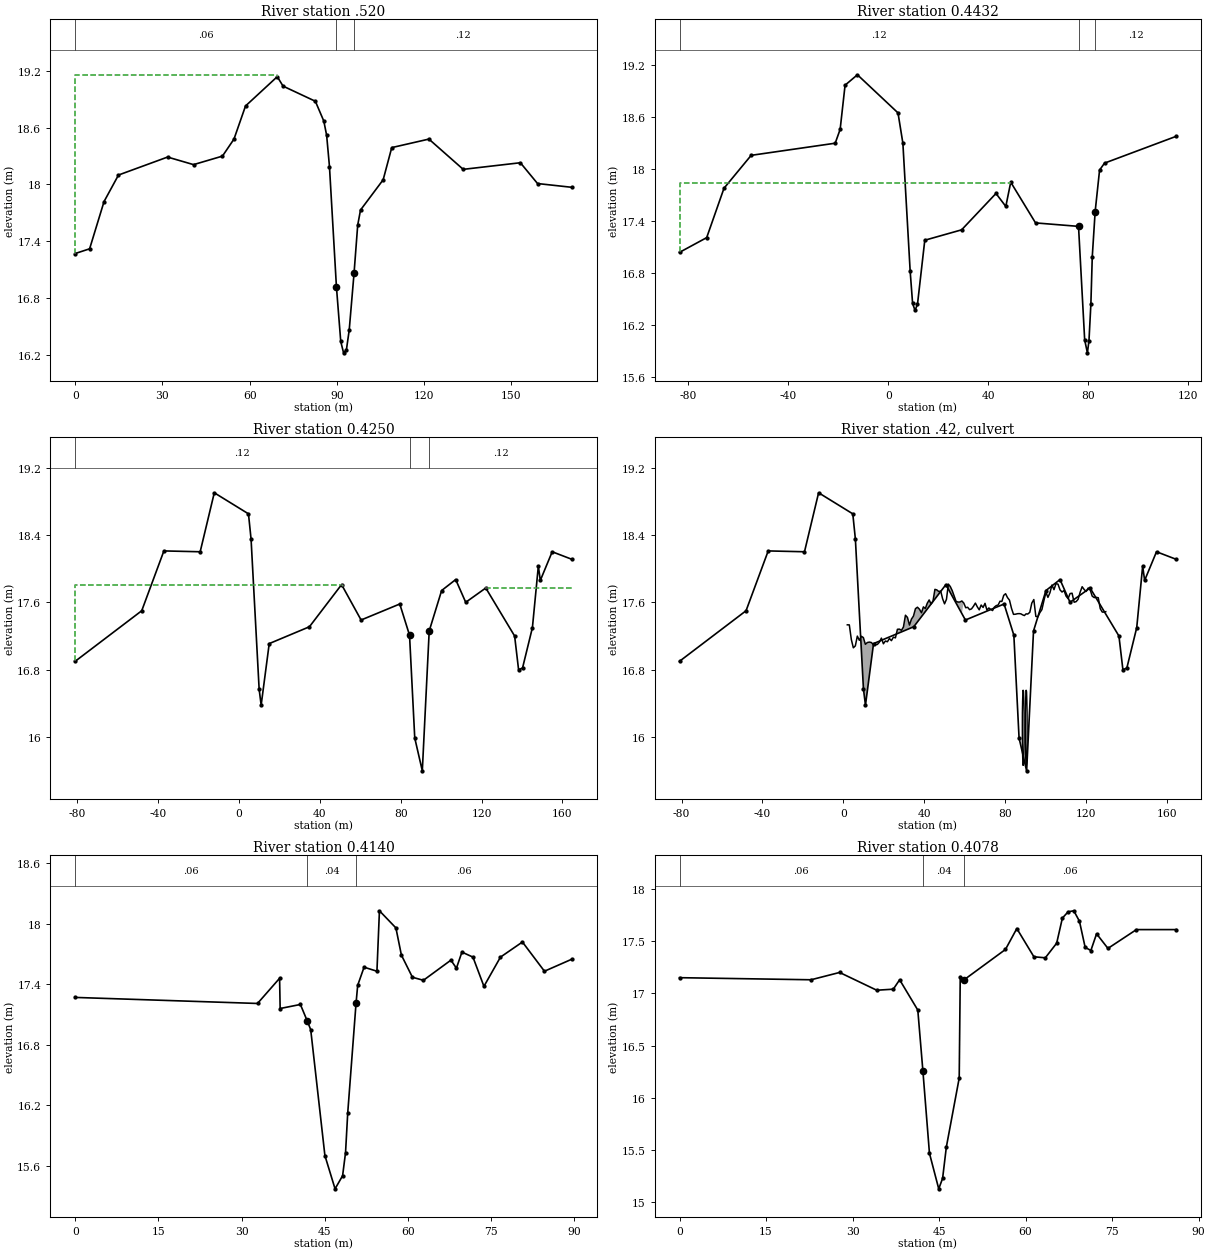
Type RM Length L Ch R = 1 ,.520    ,81.38,76.88,73.79
BEGIN DESCRIPTION:
n/a
END DESCRIPTION:
XS GIS Cut Line= 6
  611841.6290036 5430832.1354831  611772.9453036 5430812.3042831
  611761.9892036 5430810.4395831  611741.6163036 5430810.4395831
  611691.6099036 5430787.4207831  611679.7037036 5430792.1832831
#Sta/Elev= 30
       0   17.27    4.96   17.32    9.93   17.82   14.89    18.1   31.77   18.29
   40.71   18.21   50.64    18.3   54.61   18.48   58.58   18.83    69.5   19.14
   71.49   19.04    82.6   18.88   85.51   18.67   86.48   18.52   87.45   18.19
   89.84   16.92   91.33   16.34    92.3   16.22   93.27   16.25   94.24   16.46
    95.9   17.06   97.16   17.57   98.13   17.73  105.92   18.05  108.87   18.39
  121.65   18.48  133.45   18.16  153.11   18.23  159.01   18.01  170.85   17.97
#Mann= 3 , 0 , 0
       0     .06       0   89.84     .04       0    95.9     .12       0
#XS Ineff= 2 , 0
           69.52   19.16
Permanent Ineff=
       F       F
Bank Sta=89.84,95.9
XS Rating Curve= 0 ,0
Exp/Cntr=0.3,0.1

Type RM Length L Ch R = 1 ,0.4432  ,10.64,18.2,24.3
BEGIN DESCRIPTION:
BF2_13 (SEM 2019)
END DESCRIPTION:
XS GIS Cut Line= 6
  611848.9712036 5430832.9953831  611776.2106036 5430790.9926831
  611772.4888036 5430776.4020831  611740.4467036 5430759.2208831
  611727.9130036 5430746.3903831  611703.5833036 5430784.4315831
#Sta/Elev= 30
   -83.5   17.04  -72.63   17.21  -65.71   17.78  -54.84   18.16  -21.23    18.3
  -19.25   18.46  -17.28   18.97  -12.34   19.09    3.89   18.65    5.84    18.3
    8.76   16.82    9.73   16.45    10.7   16.37   11.68   16.44    14.6   17.18
   29.33    17.3   43.08   17.72   47.01   17.57   48.98   17.85    58.9   17.38
   76.09   17.34   78.55   16.03   79.64   15.88   80.27   16.02   81.03   16.44
   81.59   16.99   82.74   17.51   84.51   17.99   86.49   18.07  115.19   18.38
#Mann= 3 , 0 , 0
   -83.5     .12       0   76.09     .04       0   82.74     .12       0
#XS Ineff= 2 , 0
           48.96   17.84
Permanent Ineff=
       F       F
Bank Sta=76.09,82.74
XS Rating Curve= 0 ,0
Exp/Cntr=0.3,0.1

Type RM Length L Ch R = 1 ,0.4250  ,10.74,10.95,11.22
BEGIN DESCRIPTION:
US of BF2 Stream Exploits Valley and Beothuk Trail Culvert - BF2_12 (SEM 2019)
END DESCRIPTION:
XS GIS Cut Line= 6
  611854.5936036 5430822.7427831  611776.7131036 5430789.3020831
  611773.8903036 5430776.1917831  611727.8878036 5430745.7270831
  611721.7470036 5430748.4878831  611642.2650036 5430721.8701831
#Sta/Elev= 30
     -81    16.9  -48.09    17.5  -37.13   18.21  -19.18    18.2   -12.2    18.9
4.709999   18.65    5.99   18.35    9.98   16.57   10.98   16.38   14.97   17.11
   34.86   17.31   50.76   17.81   60.41   17.39   79.54   17.58   84.37   17.21
   86.95   15.99   90.69    15.6    94.1   17.26  100.25   17.74   107.2   17.87
  112.16    17.6  122.08   17.77  136.35    17.2  138.31    16.8  140.26   16.82
  145.15    17.3  148.08   18.03  149.06   17.86  154.93    18.2  164.71   18.11
#Mann= 3 , 0 , 0
     -81     .12       0   84.37     .04       0    94.1     .12       0
#XS Ineff= 2 , 0
           51.69    17.8  121.75           17.77
Permanent Ineff=
       F       F
Bank Sta=84.37,94.1
XS Rating Curve= 0 ,0
Exp/Cntr=0.3,0.1

Type RM Length L Ch R = 2 ,.42     ,,,
Node Photo=.\Photos\BF2-CR-3.JPG
BEGIN DESCRIPTION:
BF2 Stream Exploits Valley and Beothuk Trail Culvert
END DESCRIPTION:
Node Name=BF2-CR-3
Bridge Culvert--1,0,-1,-1, 0
Deck Dist Width WeirC Skew NumUp NumDn MinLoCord MaxHiCord MaxSubmerge Is_Ogee
1.7,4,1.4,0, 133, 133, , , 0.98, 0, 3,3,,
       22.9914083.9828164.9742245.965632 6.957047.9484488.9398579.93126510.92267
11.9140812.90549 13.8969 14.888315.8797116.8711217.8625318.8539419.8453420.83675
21.8281622.8195723.8109824.8023925.79379 26.785227.7766128.7680229.7594330.75083
31.7422432.7336533.7250634.7164635.7078736.6992837.69069 38.682139.6323840.58266
41.5329442.4832343.4335144.3837945.3340746.2843547.2346348.18491 49.135250.08548
51.0357651.9860452.93633 53.886654.8368955.7915256.74616 57.700858.6554359.61007
60.5647161.5193562.4739863.4286264.3832665.3378966.2925367.2471768.2018169.15644
70.1110871.0657271.9876972.9096673.8316374.7536175.6755876.5975677.5195378.44151
79.3634880.2854581.20743 82.204883.2021984.1995685.1969586.1943287.0382587.88216
88.72608   89.5790.4139291.2578492.2549793.2521194.2492595.2463996.2435397.24067
98.2378199.23495100.2307101.2264102.2222103.2179104.2136105.2094106.2051107.2008
108.1966109.1923 110.188111.1838112.1795113.1752 114.171115.1667116.1624117.1582
118.1539119.1497120.1454121.1411122.1369123.1326124.1283125.1241126.1198127.1155
128.1113128.9712129.8311
  17.333  17.332  17.159   17.06  17.083  17.199  17.149  17.197  17.182  17.102
  17.123  17.128  17.123  17.099  17.098    17.1  17.127  17.175  17.108  17.141
  17.132  17.171  17.145  17.187  17.178   17.28  17.282  17.268  17.307  17.447
  17.421   17.33  17.401  17.437  17.525  17.542  17.518  17.476  17.546  17.526
  17.589  17.628   17.58  17.616  17.754  17.747  17.728  17.734  17.642  17.582
  17.635  17.816  17.787  17.739  17.677  17.611  17.603  17.604  17.616  17.591
  17.536  17.541  17.513  17.522  17.553  17.591  17.546  17.511  17.568  17.539
  17.588  17.507  17.533  17.516  17.502  17.544  17.561  17.568  17.613   17.61
  17.683  17.702  17.657  17.626  17.529  17.457  17.459  17.465  17.466  17.463
  17.451  17.443  17.463  17.461  17.481  17.591  17.633  17.433  17.427  17.478
  17.513   17.62  17.718  17.659  17.714  17.805   17.75  17.821  17.816  17.748
  17.722  17.741  17.674  17.644  17.704  17.708  17.601  17.608  17.636   17.72
  17.785  17.752  17.729   17.77  17.748  17.673  17.656  17.659  17.654  17.524
  17.484  17.484  17.489
     -40-39.0085-38.0171-37.0257-36.0343-35.0429-34.0515-33.0601-32.0687-31.0773
-30.0859-29.0945-28.1031-27.1117-26.1202-25.1288-24.1374 -23.146-22.1546-21.1632
-20.1718-19.1804 -18.189-17.1976-16.2062-15.2148-14.2233-13.2319-12.2405-11.2491
-10.2577-9.26635-8.27494-7.28353-6.29212-5.30071-4.30931 -3.3179-2.36762-1.41733
-.467056.48322491.4335072.383788 3.334074.2843525.2346336.1849157.1351978.085479
9.0357619.98604210.9363211.8866112.8368913.7915214.74616 15.700816.6554417.61007
18.5647119.5193520.4739821.4286222.3832623.3378924.2925325.2471726.2018127.15644
28.1110829.0657229.9876930.9096631.8316432.7536133.6755834.5975635.5195336.44151
37.3634838.2854539.2074340.2048141.2021942.1995743.1969544.1943245.0382445.88216
46.72608   47.5748.4139249.2578450.2549851.2521252.2492553.2463954.2435355.24067
 56.237857.2349458.2306859.2264160.2221561.2178962.2136263.2093664.2050965.20083
66.19656 67.192368.1880369.18377 70.179571.1752472.1709773.1667174.1624575.15819
76.1539277.1496678.1453979.1411380.13686 81.132682.1283383.12407 84.119885.11554
86.1112786.9711887.83107
  17.333  17.332  17.159   17.06  17.083  17.199  17.149  17.197  17.182  17.102
  17.123  17.128  17.123  17.099  17.098    17.1  17.127  17.175  17.108  17.141
  17.132  17.171  17.145  17.187  17.178   17.28  17.282  17.268  17.307  17.447
  17.421   17.33  17.401  17.437  17.525  17.542  17.518  17.476  17.546  17.526
  17.589  17.628   17.58  17.616  17.754  17.747  17.728  17.734  17.642  17.582
  17.635  17.816  17.787  17.739  17.677  17.611  17.603  17.604  17.616  17.591
  17.536  17.541  17.513  17.522  17.553  17.591  17.546  17.511  17.568  17.539
  17.588  17.507  17.533  17.516  17.502  17.544  17.561  17.568  17.613   17.61
  17.683  17.702  17.657  17.626  17.529  17.457  17.459  17.465  17.466  17.463
  17.451  17.443  17.463  17.461  17.481  17.591  17.633  17.433  17.427  17.478
  17.513   17.62  17.718  17.659  17.714  17.805   17.75  17.821  17.816  17.748
  17.722  17.741  17.674  17.644  17.704  17.708  17.601  17.608  17.636   17.72
  17.785  17.752  17.729   17.77  17.748  17.673  17.656  17.659  17.654  17.524
  17.484  17.484  17.489
BR Coef=-1 , 0 , 0 ,, 0 ,,,0.8,-1,,0,
WSPro=,,,, 1 ,,,, 0 ,,,, 0 ,,,,-1 ,-1 ,-1 , 0 , 0 , 0 , 0 , 0
Multiple Barrel Culv=1,0.9,,8.9,0.011,0.9,1,2,3,15.661,15.5165, 2,Culvert #1  , 0 ,0.85
      89      46    90.5    47.5
BC Culvert Barrel=1,Barrel 1,0
BC Culvert Barrel=2,Barrel 2,0
Culvert Bottom n=0.011
BC Design=,, 0 ,, 0 ,,,,,,
BC Use User HTab Curves=0
BC User HTab FreeFlow(D)= 0

Type RM Length L Ch R = 1 ,0.4140  ,5.48,6.27,7.08
BEGIN DESCRIPTION:
DS of BF2 Stream Exploits Valley and Beothuk Trail Culvert - BF2_11 (SEM 2019)
END DESCRIPTION:
XS GIS Cut Line= 4
611760.4231035985430759.06018309611728.4084035985430740.80388309
611713.0626035985430731.41118309611683.9583035995430712.49338309
#Sta/Elev= 30
       0   17.27   32.87   17.21   36.85   17.46   36.95   17.16    40.6    17.2
   41.81   17.04   42.46   16.95   45.02    15.7   46.85   15.37   48.21    15.5
   48.74   15.73   49.13   16.12   50.63   17.21   50.93   17.39   52.08   17.57
    54.4   17.53   54.85   18.13   57.82   17.96   58.81   17.69    60.8   17.47
   62.78   17.44   67.74   17.64   68.73   17.56   69.72   17.72   71.71   17.67
   73.69   17.38   76.67   17.67   80.63   17.82    84.6   17.53   89.56   17.65
#Mann= 3 , 0 , 0
       0     .06       0   41.81     .04       0   50.63     .06       0
Bank Sta=41.81,50.63
XS Rating Curve= 0 ,0
Exp/Cntr=0.3,0.1

Type RM Length L Ch R = 1 ,0.4078  ,29.92,30.48,29.95
BEGIN DESCRIPTION:
BF2_10 (SEM 2019)
END DESCRIPTION:
XS GIS Cut Line= 4
611762.0106035985430757.07578309611733.1709035985430739.61328309
611718.7511035995430725.98718309611690.4406035985430709.84758309
#Sta/Elev= 30
       0   17.15   22.81   17.13   27.76    17.2    34.2   17.03   37.07   17.04
   38.17   17.13   41.32   16.84    42.2   16.26   43.34   15.47   44.95   15.13
   45.62   15.23   46.27   15.53    48.5   16.19   48.68   17.16   49.35   17.13
   56.52   17.42   58.49   17.62   61.45   17.35   63.43   17.34    65.4   17.48
   66.39   17.72   67.38   17.78   68.37   17.79   69.35   17.69   70.34   17.44
   71.33   17.41   72.32   17.57   74.29   17.43   79.23   17.61   86.14   17.61
#Mann= 3 , 0 , 0
       0     .06       0    42.2     .04       0   49.35     .06       0
Bank Sta=42.2,49.35
XS Rating Curve= 0 ,0
Exp/Cntr=0.3,0.1

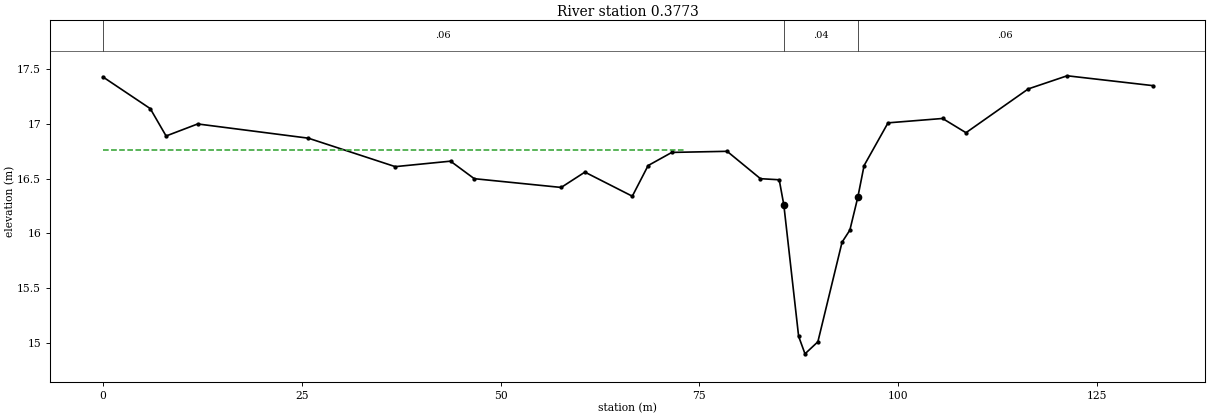
Type RM Length L Ch R = 1 ,0.3773  ,8.5,7.1,5.64
BEGIN DESCRIPTION:
BF2_09 (SEM 2019)
END DESCRIPTION:
XS GIS Cut Line= 5
611822.6396035985430765.33938309611776.4844035985430737.99798309
611754.0554035995430719.91938309611743.5779035995430710.18268309
611709.9228035985430699.70518309
#Sta/Elev= 30
       0   17.43    5.96   17.14    7.95   16.89   11.92      17   25.83   16.87
   36.76   16.61   43.71   16.66   46.69    16.5   57.62   16.42    60.6   16.56
   66.56   16.34   68.55   16.62   71.53   16.74   78.48   16.75   82.67    16.5
   85.03   16.49   85.61   16.26   87.47   15.06   88.27    14.9   89.89   15.01
   92.93   15.92   93.91   16.03   94.91   16.33    95.7   16.62   98.71   17.01
  105.57   17.05  108.51   16.92  116.34   17.32  121.23   17.44  132.01   17.35
#Mann= 3 , 0 , 0
       0     .06       0   85.61     .04       0   94.91     .06       0
#XS Ineff= 2 , 0
           73.12   16.76
Permanent Ineff=
       F       F
Bank Sta=85.61,94.91
XS Rating Curve= 0 ,0
Exp/Cntr=0.3,0.1