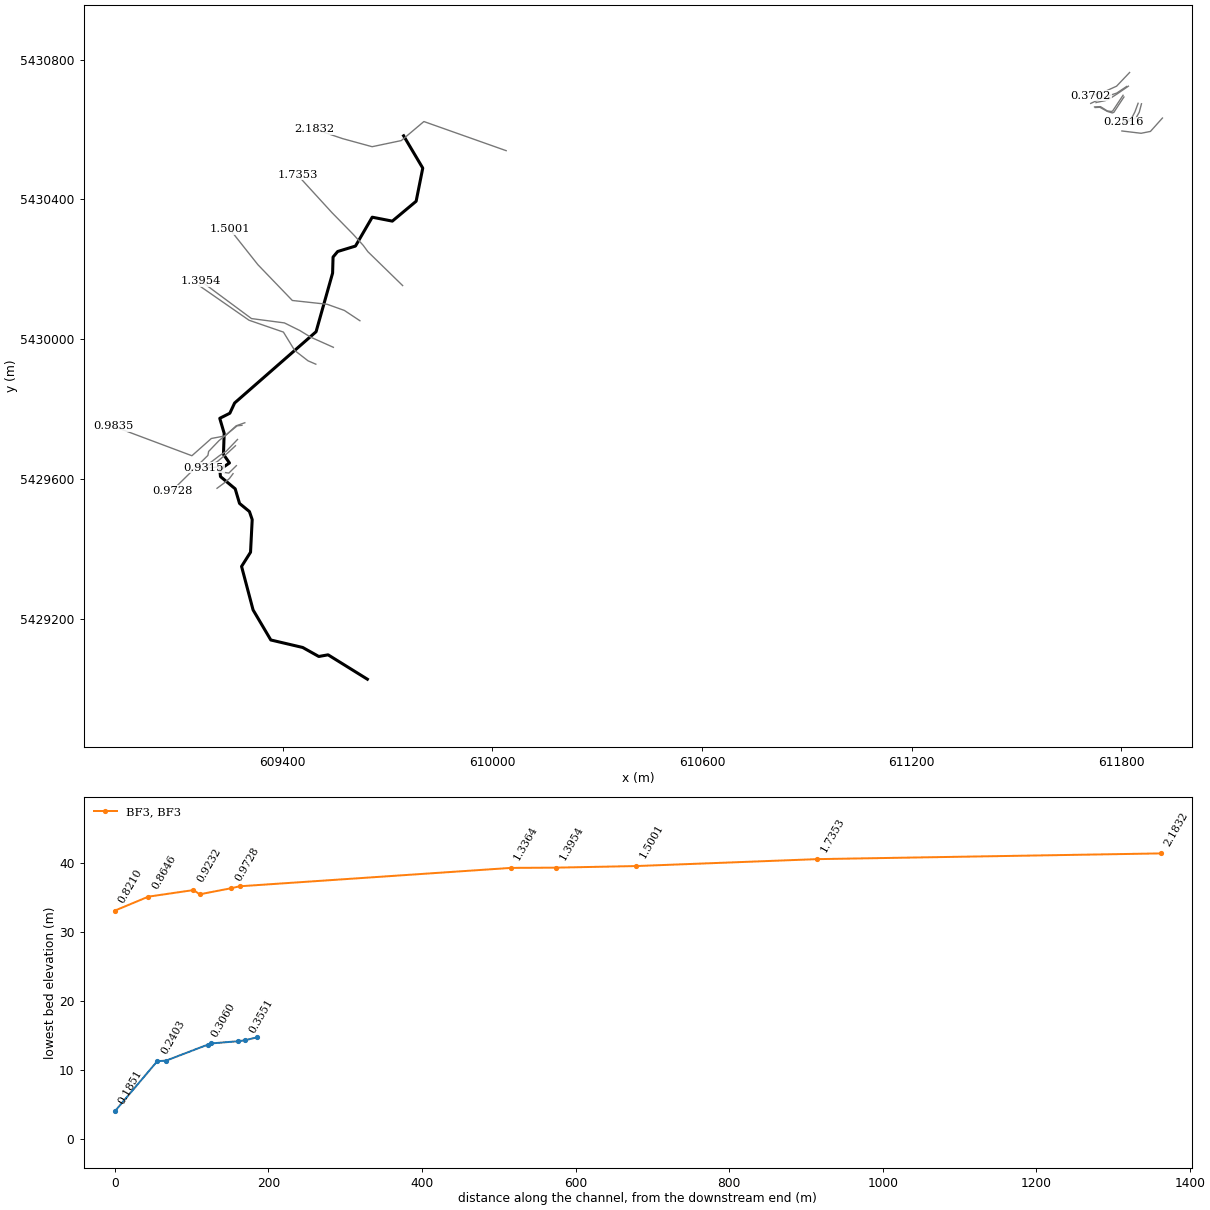
HEC-RAS study Exploits_FMM.prj: Exploits_FMM

--- Exploits_FMM.g01 (geometry) --- (continued)

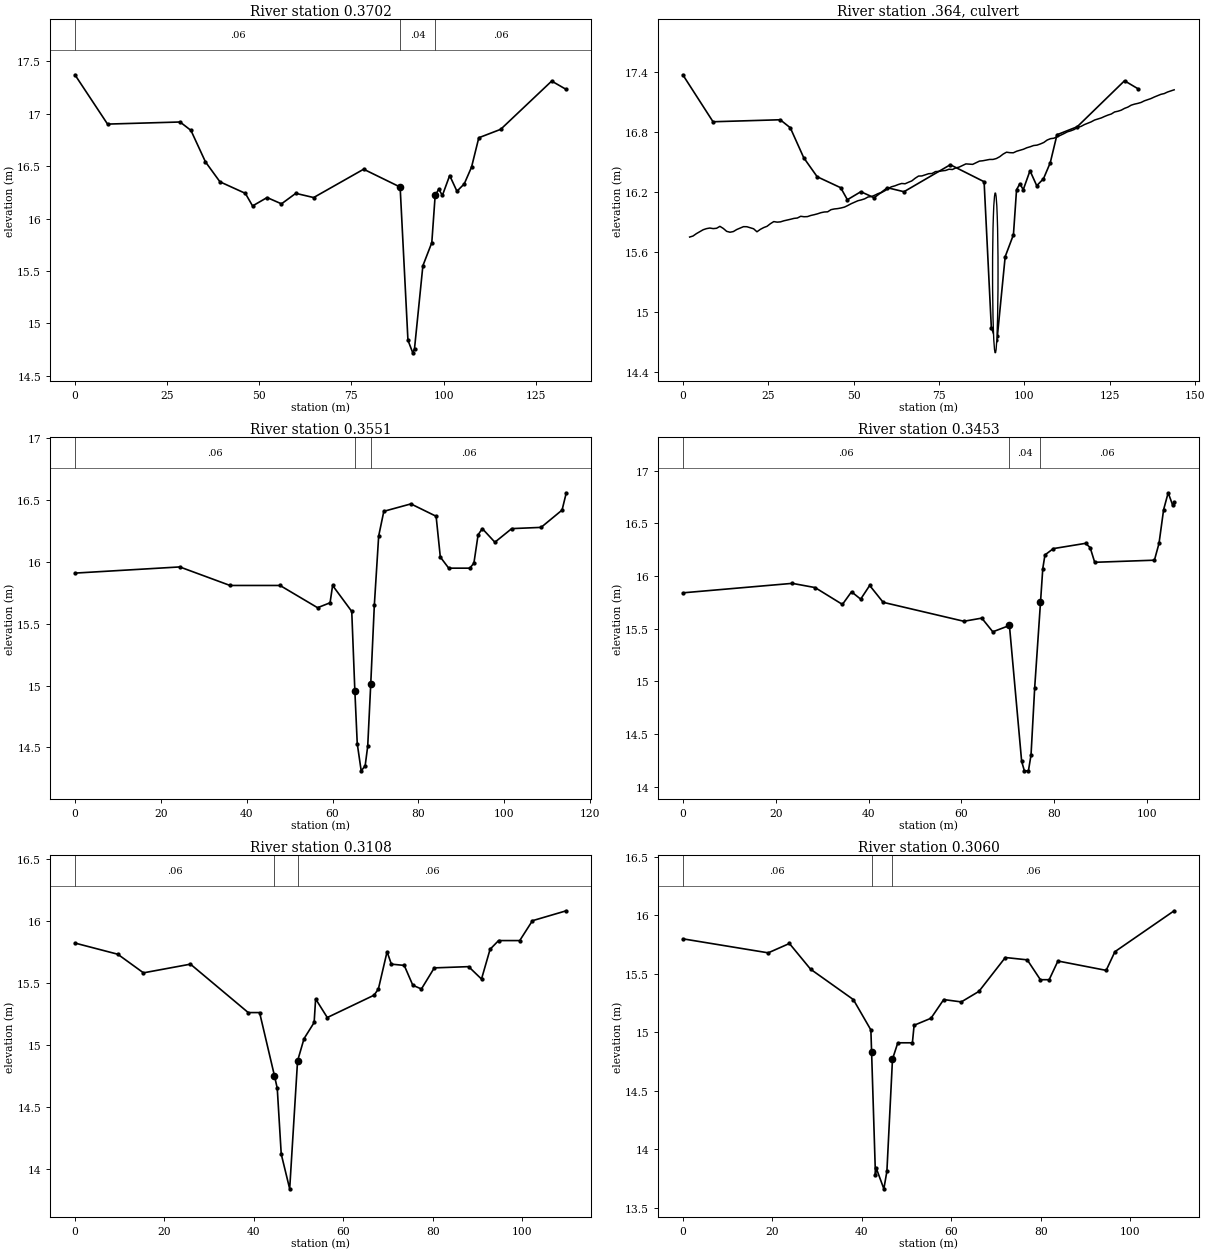
Type RM Length L Ch R = 1 ,0.3702  ,15.52,15.06,14.82
BEGIN DESCRIPTION:
US of BF2 Stream Main Street Culvert - BF2_08 (SEM 2019)
END DESCRIPTION:
XS GIS Cut Line= 5
611824.2227035985430763.46738309611786.9179035985430724.29498309
611759.5588035985430711.87608309611746.2237035995430706.05518309
611712.9920035985430696.42438309
#Sta/Elev= 30
       0   17.37    8.85    16.9   28.52   16.92   31.47   16.84   35.41   16.54
   39.34   16.35   46.23   16.24   48.19   16.12   52.13    16.2   56.03   16.14
   59.91   16.24   64.76    16.2   78.32   16.47   88.22    16.3   90.34   14.84
91.64999   14.72   92.12   14.76   94.39   15.55   96.81   15.77   97.72   16.22
   98.69   16.28   99.68   16.22  101.66   16.41  103.63   16.26  105.61   16.33
  107.59   16.49  109.56   16.77  115.49   16.85  129.33   17.31  133.29   17.23
#Mann= 3 , 0 , 0
       0     .06       0   88.22     .04       0   97.72     .06       0
#XS Ineff= 2 , 0
           78.77   16.46
Permanent Ineff=
       F       F
Bank Sta=88.22,97.72
XS Rating Curve= 0 ,0
Exp/Cntr=0.3,0.1

Type RM Length L Ch R = 2 ,.364    ,,,
Node Photo=.\Photos\BF2-CR-2.JPG
BEGIN DESCRIPTION:
BF2 Stream Main Street Culvert
END DESCRIPTION:
Node Name=BF2-CR-2
Bridge Culvert--1,0,-1,-1, 0
Deck Dist Width WeirC Skew NumUp NumDn MinLoCord MaxHiCord MaxSubmerge Is_Ogee
1.1,8,1.4,0, 145, 145, , , 0.98, 0, 3,3,,
       22.9856063.971213 4.956825.9424266.9280327.9136398.8992459.88485110.87046
11.8560612.8416713.8272814.8128815.79849 16.7841 17.769718.7553119.7409220.72652
21.7121322.6977323.6833424.6689525.6545526.6401627.6257728.6113729.5969830.58259
31.56819 32.553833.5394134.5250135.5106236.4962337.4818338.4674439.4530440.43865
41.4242642.4098743.3954744.3810845.3666846.35229 47.3379 48.323549.3091150.29472
51.2803252.2659353.2515454.2371455.2227556.2083557.1939658.1795759.1651760.15078
61.1363962.12199 63.107664.0932165.0788166.0644267.0500368.0356369.0212470.01219
71.0031471.9940972.98505  73.97674.96695 75.957976.94885 77.939878.9307679.92171
80.9126681.9036182.8945683.8855184.8764685.8674286.8583787.8493288.8402889.83123
90.8221891.8131392.8040893.7950494.7859995.7769496.7678997.7588498.7497999.74075
100.7317101.7226102.7136103.7046104.6955105.6865106.6774107.6684108.6593109.6503
110.6412111.6322112.6231113.6141 114.605 115.596116.5869117.5779118.5688119.5598
120.5507121.5417122.5326123.5236124.4924125.4613126.4301127.3989128.3677129.3366
130.3054131.2742132.2431133.2119134.1807135.1496136.1184137.0872 138.056139.0249
139.9937140.9625141.9314142.9002 143.869
 15.7465 15.7568 15.7804 15.7999 15.8193 15.8306 15.8367 15.8309 15.8342 15.8536
 15.8327 15.8035 15.7948 15.8016 15.8219 15.8358 15.8504 15.8498 15.8401 15.8293
 15.7991 15.8233 15.8412 15.8541 15.8802 15.9011 15.8957 15.8984 15.9091 15.9167
 15.9245 15.9332 15.9368 15.9542 15.9497  15.951 15.9624   15.97  15.979 15.9902
 15.9972 15.9989 16.0204 16.0276 16.0312 16.0376 16.0462 16.0623 16.0803 16.0954
 16.1099 16.1182 16.1288 16.1473 16.1515 16.1651 16.1816 16.1917 16.2094 16.2336
 16.2497  16.259 16.2723 16.2826 16.2795 16.2945 16.3082 16.3348 16.3566  16.358
 16.3693 16.3804 16.3822 16.4014 16.4034 16.4089 16.4128  16.425 16.4221 16.4379
 16.4464 16.4628 16.4784 16.4762 16.4737 16.4905 16.5063 16.5098 16.5168 16.5229
  16.523 16.5321 16.5504 16.5766 16.5954 16.5906 16.5894 16.6051 16.6154  16.625
 16.6399 16.6499 16.6622  16.666 16.6779 16.6924 16.7169 16.7308 16.7352 16.7517
 16.7656 16.7818 16.7996 16.8095 16.8227 16.8444 16.8534 16.8715 16.8848 16.8988
 16.9171 16.9272 16.9383 16.9536 16.9669 16.9775 16.9981 17.0052 17.0159 17.0339
 17.0464 17.0658 17.0762 17.0836 17.0932 17.1094 17.1204 17.1322 17.1476 17.1616
 17.1745  17.182 17.1976 17.2086 17.2196
     -24-23.0143-22.0287-21.0431-20.0575-19.0719-18.0863-17.1007-16.1151-15.1295
-14.1439-13.1583-12.1727-11.1871-10.2015 -9.2159-8.23029-7.24469-6.25908-5.27347
-4.28787-3.30226-2.31665-1.33105-.345445.64016131.6257682.6113743.5969814.582587
5.568193  6.55387.5394068.5250139.51061910.4962311.4818312.4674413.4530414.43865
15.4242616.4098617.3954718.3810819.3666820.35229 21.3379 22.323523.3091124.29472
25.2803226.2659327.2515428.2371429.2227530.2083531.1939632.1795733.1651734.15078
35.1363936.12199 37.107638.0932139.0788140.0644241.0500342.0356343.0212444.01219
45.0031445.9940946.98505  47.97648.96695 49.957950.94885 51.939852.9307653.92171
54.9126655.9036156.8945757.8855258.8764759.8674260.8583761.8493262.8402763.83123
64.8221865.8131366.8040867.7950468.7859969.7769470.7678971.7588472.7497973.74075
 74.731775.72265 76.713677.70455 78.695579.6864580.6774181.6683682.6593183.65026
84.6412185.6321686.6231287.6140788.6050289.5959790.5869291.5778892.5688393.55978
94.5507495.5416996.5326497.5235998.4924299.46125100.4301101.3989102.3677103.3366
104.3054105.2742106.2431107.2119108.1807109.1496110.1184111.0872112.0561113.0249
113.9937114.9625115.9314116.9002 117.869
 15.7465 15.7568 15.7804 15.7999 15.8193 15.8306 15.8367 15.8309 15.8342 15.8536
 15.8327 15.8035 15.7948 15.8016 15.8219 15.8358 15.8504 15.8498 15.8401 15.8293
 15.7991 15.8233 15.8412 15.8541 15.8802 15.9011 15.8957 15.8984 15.9091 15.9167
 15.9245 15.9332 15.9368 15.9542 15.9497  15.951 15.9624   15.97  15.979 15.9902
 15.9972 15.9989 16.0204 16.0276 16.0312 16.0376 16.0462 16.0623 16.0803 16.0954
 16.1099 16.1182 16.1288 16.1473 16.1515 16.1651 16.1816 16.1917 16.2094 16.2336
 16.2497  16.259 16.2723 16.2826 16.2795 16.2945 16.3082 16.3348 16.3566  16.358
 16.3693 16.3804 16.3822 16.4014 16.4034 16.4089 16.4128  16.425 16.4221 16.4379
 16.4464 16.4628 16.4784 16.4762 16.4737 16.4905 16.5063 16.5098 16.5168 16.5229
  16.523 16.5321 16.5504 16.5766 16.5954 16.5906 16.5894 16.6051 16.6154  16.625
 16.6399 16.6499 16.6622  16.666 16.6779 16.6924 16.7169 16.7308 16.7352 16.7517
 16.7656 16.7818 16.7996 16.8095 16.8227 16.8444 16.8534 16.8715 16.8848 16.8988
 16.9171 16.9272 16.9383 16.9536 16.9669 16.9775 16.9981 17.0052 17.0159 17.0339
 17.0464 17.0658 17.0762 17.0836 17.0932 17.1094 17.1204 17.1322 17.1476 17.1616
 17.1745  17.182 17.1976 17.2086 17.2196
BR Coef=-1 , 0 , 0 ,, 0 ,,,0.8,-1,,0,
WSPro=,,,, 1 ,,,, 0 ,,,, 0 ,,,,-1 ,-1 ,-1 , 0 , 0 , 0 , 0 , 0
Culvert=1,1.6,,13.4,0.024,0.9,1,2,3,14.588,91.5,14.41,67,Culvert #1  , 0 ,0.8
    91.5      67
BC Culvert Barrel=1,Barrel 1,0
Culvert Bottom n=0.024
BC Design=,, 0 ,, 0 ,,,,,,
BC Use User HTab Curves=0
BC User HTab FreeFlow(D)= 0

Type RM Length L Ch R = 1 ,0.3551  ,9.7,9.82,9.97
BEGIN DESCRIPTION:
DS of BF2 Stream Main Street Culvert - BF2_07 (SEM 2019)
END DESCRIPTION:
XS GIS Cut Line= 5
611815.8663035995430723.53508309611787.4156035995430704.58708309
611763.4856035985430696.53018309611748.4043035985430691.50308309
611712.9501035995430674.96658309
#Sta/Elev= 30
       0   15.91   24.42   15.96   36.13   15.81   47.78   15.81   56.52   15.63
   59.43   15.67   60.02   15.81   64.48    15.6    65.2   14.96   65.76   14.53
   66.68   14.31    67.6   14.35    68.2   14.51    68.9   15.01   69.74   15.65
   70.75   16.21   71.95   16.41   78.26   16.47   84.13   16.37   85.11   16.04
   87.07   15.95   91.96   15.95   92.93   15.99   93.91   16.22   94.89   16.27
   97.82   16.16  101.74   16.27  108.58   16.28  113.47   16.42  114.45   16.56
#Mann= 3 , 0 , 0
       0     .06       0    65.2     .04       0    68.9     .06       0
Bank Sta=65.2,68.9
XS Rating Curve= 0 ,0
Exp/Cntr=0.3,0.1

Type RM Length L Ch R = 1 ,0.3453  ,32.24,34.5,36.04
BEGIN DESCRIPTION:
BF2_06 (SEM 2019)
END DESCRIPTION:
XS GIS Cut Line= 6
611820.7876035985430724.32888309611788.4175035985430702.08058309
611766.5283035985430687.93118309611754.0929035985430682.77188309
611727.8991035995430677.61248309611728.0314035985430677.34788309
#Sta/Elev= 30
       0   15.84   23.57   15.93   28.48   15.89   34.37   15.73   36.33   15.85
    38.3   15.78   40.24   15.91   43.14   15.75   60.52   15.57   64.38    15.6
   66.75   15.47   70.33   15.53   72.96   14.24   73.55   14.15   74.42   14.15
   74.98    14.3   75.77   14.94   77.02   15.7577.50999   16.07   77.98    16.2
   79.79   16.26   86.72   16.31   87.71   16.27   88.69   16.13  101.55   16.15
  102.54   16.31  103.53   16.63  104.51   16.79   105.5   16.67   105.8    16.7
#Mann= 3 , 0 , 0
       0     .06       0   70.33     .04       0   77.02     .06       0
Bank Sta=70.33,77.02
XS Rating Curve= 0 ,0
Exp/Cntr=0.3,0.1

Type RM Length L Ch R = 1 ,0.3108  ,4.68,4.8,4.89
BEGIN DESCRIPTION:
BF2_05 (SEM 2019)
END DESCRIPTION:
XS GIS Cut Line= 6
611805.4902035995430698.27398309611775.7888035985430653.40308309
611771.7899035985430651.68928309611760.2993035985430653.45348309
611740.8186035995430665.76398309611723.8046035985430664.91308309
#Sta/Elev= 30
       0   15.82    9.58   15.73   15.33   15.58   25.84   15.65   38.76   15.26
    41.3   15.26   44.63   14.75   45.25   14.65   46.14   14.12   48.03   13.84
   49.79   14.87   51.24   15.05    53.5   15.18   53.83   15.37   56.44   15.22
    66.9    15.4   67.87   15.45   69.81   15.75   70.77   15.65   73.65   15.64
   75.57   15.48   77.49   15.45   80.37   15.62   88.05   15.63   90.93   15.53
   92.85   15.77   94.75   15.84   99.48   15.84  102.32      16  109.89   16.08
#Mann= 3 , 0 , 0
       0     .06       0   44.63     .04       0   49.79     .06       0
Bank Sta=44.63,49.79
XS Rating Curve= 0 ,0
Exp/Cntr=0.3,0.1

Type RM Length L Ch R = 1 ,0.3060  ,54.25,54.38,54.07
BEGIN DESCRIPTION:
US of Culvert Under Private Home- BF2_04 (SEM 2019)
END DESCRIPTION:
XS GIS Cut Line= 6
611808.0302035995430693.40558309611779.0961035985430649.43428309
611774.7411035985430647.74998309611760.6168035995430652.02468309
611739.1496035985430663.83388309611725.9213035985430663.21978309
#Sta/Elev= 27
       0    15.8   19.09   15.68   23.83   15.76   28.56   15.54   38.12   15.28
   42.04   15.02    42.2   14.83   43.06   13.78   43.21   13.84   44.94   13.66
   45.62   13.81   46.87   14.77   48.06   14.91   51.32   14.91    51.7   15.06
   55.47   15.12   58.32   15.28   62.25   15.26   66.19   15.35   72.09   15.64
   76.99   15.62   79.93   15.45   81.89   15.45   83.85   15.61   94.63   15.53
   96.59   15.69  109.83   16.04
#Mann= 3 , 0 , 0
       0     .06       0    42.2     .04       0   46.87     .06       0
Bank Sta=42.2,46.87
XS Rating Curve= 0 ,0
Exp/Cntr=0.3,0.1

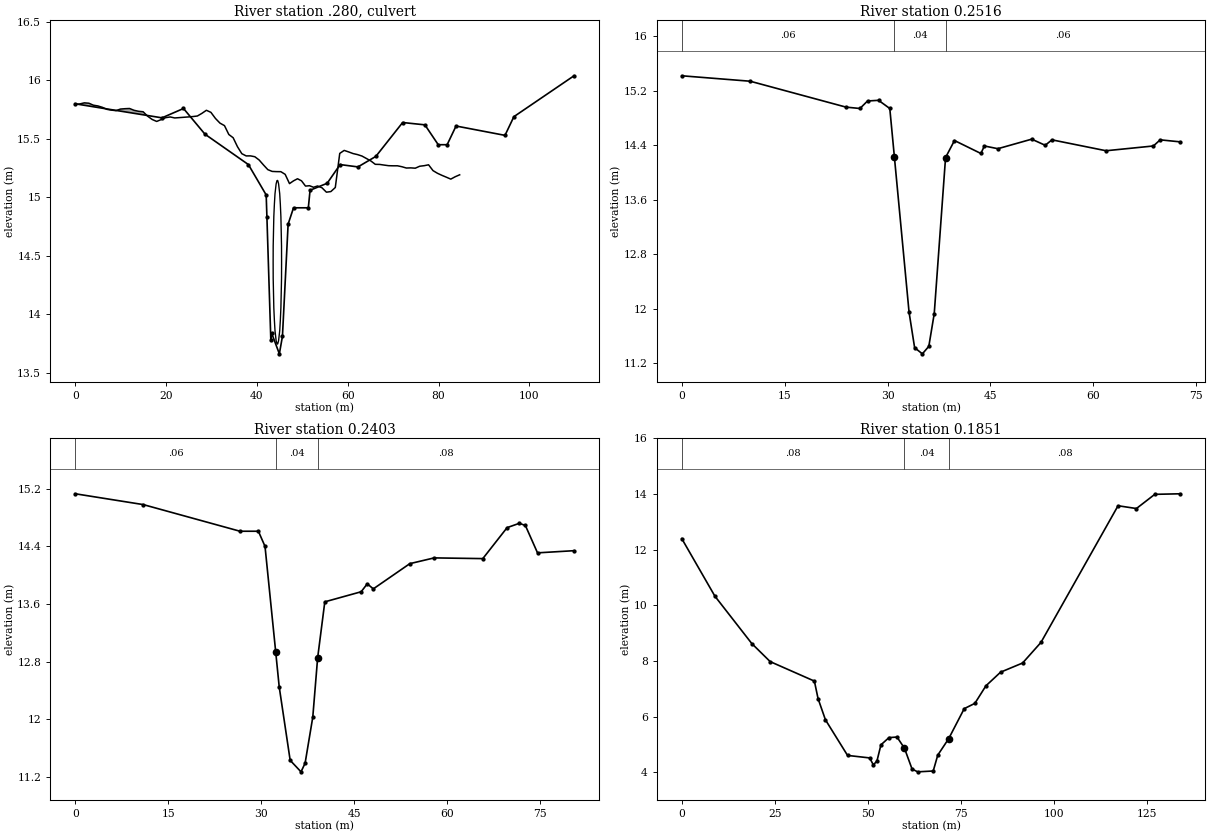
Type RM Length L Ch R = 2 ,.280    ,,,
Node Photo=.\Photos\BF2-CR-1.JPG
BEGIN DESCRIPTION:
Culvert Under Private Home
END DESCRIPTION:
Node Name=BF2-CR-1
Bridge Culvert--1,0,-1,-1, 0
Deck Dist Width WeirC Skew NumUp NumDn MinLoCord MaxHiCord MaxSubmerge Is_Ogee
9.5,43,1.4,0, 88, 88, , , 0.98, 0, 3,3,,
       0.99563151.9912632.9868953.9825264.9781585.9737896.9694217.9650528.960684
9.95631510.9519511.9475812.9432113.9388414.93447 15.930116.9257417.92137  18.917
19.9126320.9082621.9038922.8995223.8951624.8907925.8864226.8820527.8776828.87331
29.8689530.8645831.8602132.8558433.8103434.7648435.7193436.6738437.6283438.58284
39.5373540.4918441.4463542.4008443.3553544.3098445.2643546.2188547.1733548.05534
48.9373349.8193250.7013151.5833152.4652953.3472954.3254155.3035356.2816557.25977
58.2378859.2160160.1941361.1722562.1503663.1284964.1066165.0847266.0628467.04096
68.0190868.9972169.9753370.9534571.9315672.90968 73.887874.8659275.8440476.82217
77.80029 78.778479.7565280.7346481.7127682.69088  83.66984.64712
 15.7941 15.7991 15.8083 15.8052 15.7883 15.7818 15.7698 15.7526 15.7458 15.7417
 15.7552 15.7583   15.76 15.7445  15.736 15.7322 15.6943 15.6661 15.6492 15.6651
 15.6815 15.6875  15.679 15.6819 15.6848 15.6877 15.6909 15.6956 15.7182 15.7447
 15.7269 15.6748 15.6348 15.6133 15.5374 15.5096 15.4326 15.3732 15.3541 15.3544
 15.3471  15.319 15.2766 15.2365 15.2214 15.2196 15.2192 15.1964  15.117 15.1406
 15.1586 15.1408 15.0958  15.099 15.0856 15.0968 15.0814 15.0436 15.0489 15.0837
 15.3756 15.4012 15.3883 15.3742 15.3654  15.353 15.3322 15.3111 15.2822 15.2812
 15.2756 15.2704 15.2694 15.2695 15.2615 15.2504 15.2517  15.249 15.2657 15.2704
  15.278 15.2282 15.2055 15.1879  15.172 15.1555 15.1759 15.1924
     -10-9.00436-8.00873 -7.0131-6.01747-5.02184-4.02621-3.03057-2.03494-1.03931
   -.043.95194681.947578 2.943213.9388414.9344735.9301046.9257367.9213688.916999
 9.9126310.9082611.9038912.8995213.8951614.8907915.8864216.8820517.8776818.87331
19.8689520.8645821.8602122.8558423.8103424.7648425.7193426.6738427.6283428.58284
29.5373430.4918431.4463432.4008433.3553534.3098435.2643536.2188537.1733538.05534
38.9373339.8193240.7013141.5833142.4652943.3472944.3254145.3035346.2816547.25977
48.2378849.2160150.1941351.1722552.1503653.1284954.1066155.0847256.0628457.04097
58.01908 58.997259.9753260.9534561.9315662.90968 63.887864.8659265.8440466.82217
67.80029 68.778469.7565270.7346471.7127672.69088  73.66974.64712
 15.7941 15.7991 15.8083 15.8052 15.7883 15.7818 15.7698 15.7526 15.7458 15.7417
 15.7552 15.7583   15.76 15.7445  15.736 15.7322 15.6943 15.6661 15.6492 15.6651
 15.6815 15.6875  15.679 15.6819 15.6848 15.6877 15.6909 15.6956 15.7182 15.7447
 15.7269 15.6748 15.6348 15.6133 15.5374 15.5096 15.4326 15.3732 15.3541 15.3544
 15.3471  15.319 15.2766 15.2365 15.2214 15.2196 15.2192 15.1964  15.117 15.1406
 15.1586 15.1408 15.0958  15.099 15.0856 15.0968 15.0814 15.0436 15.0489 15.0837
 15.3756 15.4012 15.3883 15.3742 15.3654  15.353 15.3322 15.3111 15.2822 15.2812
 15.2756 15.2704 15.2694 15.2695 15.2615 15.2504 15.2517  15.249 15.2657 15.2704
  15.278 15.2282 15.2055 15.1879  15.172 15.1555 15.1759 15.1924
BR Coef=-1 , 0 , 0 ,, 0 ,,,0.8,-1,,0,
WSPro=,,,, 1 ,,,, 0 ,,,, 0 ,,,,-1 ,-1 ,-1 , 0 , 0 , 0 , 0 , 0
Culvert=3,1.4,1.86,46,0.024,0.9,1,34,3,13.744,44.5,12.106,35,Culvert #1  , 0 ,3.5
    44.5      35
BC Culvert Barrel=1,Barrel 1,0
Culvert Bottom n=0.024
BC Design=,, 0 ,, 0 ,,,,,,
BC Use User HTab Curves=0
BC User HTab FreeFlow(D)= 0

Type RM Length L Ch R = 1 ,0.2516  ,11.47,11.34,11.43
BEGIN DESCRIPTION:
DS of Culvert Under Private Home- BF2_03 (SEM 2019)
END DESCRIPTION:
XS GIS Cut Line= 4
611848.5493035985430675.36348309611839.5535035985430651.02178309
611831.2191035985430634.88218309611806.0836035985430621.25608309
#Sta/Elev= 25
       0   15.42    9.98   15.34   23.95   14.96   25.98   14.94   27.08   15.05
   28.69   15.06   30.33   14.94      31   14.23   33.14   11.95   33.95   11.43
   35.08   11.34   36.02   11.45   36.81   11.93   38.46   14.22   39.76   14.47
   43.61   14.28   44.12   14.39   46.09   14.35   51.02   14.49   52.99    14.4
   53.97   14.48   61.86   14.32   68.76   14.39   69.75   14.48   72.71   14.45
#Mann= 3 , 0 , 0
       0     .06       0      31     .04       0   38.46     .06       0
Bank Sta=31,38.46
XS Rating Curve= 0 ,0
Exp/Cntr=0.3,0.1

Type RM Length L Ch R = 1 ,0.2403  ,61.28,55.21,50.36
BEGIN DESCRIPTION:
BF2_02 (SEM 2019)
END DESCRIPTION:
XS GIS Cut Line= 4
611858.2066035985430673.90828309611851.8566035985430649.83118309
611842.9931035985430633.82378309611809.1263035985430618.21338309
#Sta/Elev= 24
       0   15.13   10.96   14.98   26.58   14.61   29.55   14.61   30.62    14.4
   32.35   12.93   32.91   12.45   34.68   11.43   36.43   11.27   37.09   11.39
   38.33   12.03   39.11   12.85   40.27   13.63   46.14   13.77   47.12   13.88
    48.1   13.81   53.99   14.16   57.92   14.24   65.77   14.23   69.69   14.66
   71.66   14.72   72.64   14.69    74.6   14.31   80.49   14.34
#Mann= 3 , 0 , 0
       0     .06       0   32.35     .04       0   39.11     .08       0
Bank Sta=32.35,39.11
XS Rating Curve= 0 ,0
Exp/Cntr=0.3,0.1

Type RM Length L Ch R = 1 ,0.1851  ,7.11,185.07,7.29
BEGIN DESCRIPTION:
BF2_01 (SEM 2019)
END DESCRIPTION:
XS GIS Cut Line= 4
611918.2275035995430633.08298309611883.8316035985430594.71838309
611857.0425035985430589.42668309611802.1413035985430596.04128309
#Sta/Elev= 30
       0    12.4    8.92   10.33   18.83    8.63   23.78    7.98   35.67    7.28
   36.66    6.65   38.64    5.89   44.59    4.61   50.53    4.52   51.53    4.27
    52.5    4.41   53.57    4.99   55.73    5.25   57.89    5.27   59.89    4.87
   61.94    4.12   63.45    4.02   67.63    4.05   68.85    4.62   71.78    5.21
   75.97    6.29   78.83    6.48    81.8    7.11   85.74     7.6   91.67    7.93
   96.61    8.67  117.34   13.58  122.28   13.48  127.22   13.99  134.13   14.01
#Mann= 3 , 0 , 0
       0     .08       0   59.89     .04       0   71.78     .08       0
Bank Sta=59.89,71.78
XS Rating Curve= 0 ,0
Exp/Cntr=0.3,0.1

River Reach=BF3             ,BF3
Reach XY= 30
609746.1130035995430582.19368309609800.9083035985430489.72158309
609781.9245035985430394.78888309609713.7941035985430337.90338309
609656.2471035985430349.14818309609608.2913035985430266.46578309
609557.3589035985430250.92148309609544.1297035985430235.04638309
609542.8068035985430189.07498309609495.4904035985430021.16338309
609262.3920035995429817.16928309609248.6336035985429787.80048309
609219.7940035985429773.24838309609232.4940035995429730.12118309
609230.3773035985429670.06068309609247.5753035985429645.45438309
609219.7940035985429626.40428309609221.9107035995429606.29598309
609263.9795035985429571.37088309609276.4149035985429529.56658309
609304.7254035995429506.28328309609312.6629035995429483.26448309
609307.9004035985429389.86638309609282.2358035995429349.12038309
609315.1765035995429224.63368309609365.9766035985429138.51168309
609457.2580035985429117.08038309609503.2956035985429091.28348309
609529.8863035985429096.04598309609642.395047543 5429026.2014789

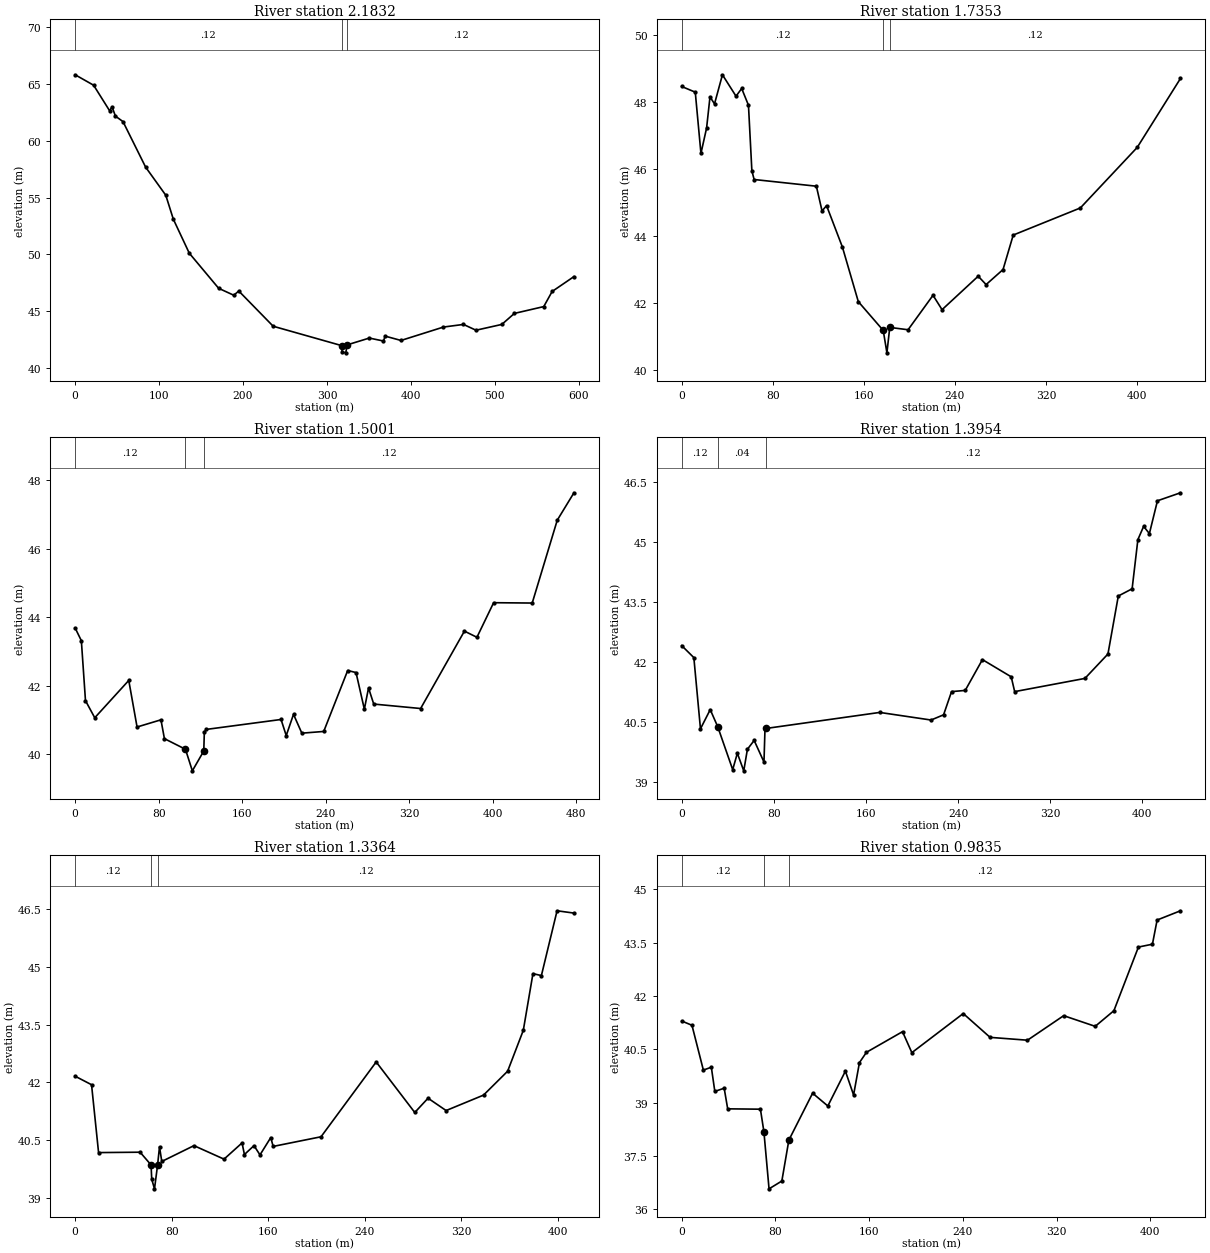
Type RM Length L Ch R = 1 ,2.1832  ,450.03,447.87,436.49
BEGIN DESCRIPTION:
BF3_40 (SEM 2019)
END DESCRIPTION:
XS GIS Cut Line= 6
610039.6509035985430539.61628309609804.0994035985430623.05248309
609739.5131035985430568.55588309609655.9359035995430550.99248309
609571.7120035985430574.05698309609489.3165035985430601.79348309
#Sta/Elev= 30
       0   65.81   21.99   64.89   40.98   62.65   43.98   62.98   47.98   62.17
   56.98   61.69   83.96   57.68  107.95   55.21  116.95    53.1  135.94   50.11
  170.93   47.02  188.92   46.41  194.92   46.78   235.9   43.68  317.29   41.98
  318.02   41.42  322.38   41.34  323.97   42.04  350.43   42.64  367.31   42.38
   369.3   42.81  388.17   42.43   438.8   43.61  462.61   43.84   477.5   43.33
  508.27   43.84  523.26   44.81  558.23   45.41  568.23   46.74  594.21   48.05
#Mann= 3 , 0 , 0
       0     .12       0  317.29     .04       0  323.97     .12       0
Bank Sta=317.29,323.97
XS Rating Curve= 0 ,0
Exp/Cntr=0.3,0.1

Type RM Length L Ch R = 1 ,1.7353  ,228.3,235.25,237.22
BEGIN DESCRIPTION:
BF3_39 (SEM 2019)
END DESCRIPTION:
XS GIS Cut Line= 6
609743.3170035985430153.32378309609643.6384035985430250.52688309
609630.7030035985430268.25318309609601.2680035985430300.66468309
609541.5079035985430361.60808309609441.6914035995430470.82438309
#Sta/Elev= 30
       0   48.47   11.93    48.3   16.91   46.47   21.88   47.23   24.86   48.16
   28.84   47.95    35.8   48.82   47.74   48.18   52.71   48.41   58.67   47.91
   61.66   45.95   63.65   45.69  118.34   45.49  123.32   44.75  127.29   44.91
  141.22   43.67  155.19   42.04  177.09   41.18  180.32   40.51  182.83   41.27
  198.91    41.2  220.83   42.23  228.77    41.8  260.53    42.8  267.48   42.55
  282.37      43  291.31   44.03  350.29   44.84  400.28   46.65  438.27   48.71
#Mann= 3 , 0 , 0
       0     .12       0  177.09     .04       0  182.83     .12       0
Bank Sta=177.09,182.83
XS Rating Curve= 0 ,0
Exp/Cntr=0.3,0.1

Type RM Length L Ch R = 1 ,1.5001  ,115.14,104.69,111.57
BEGIN DESCRIPTION:
BF3_38 (SEM 2019)
END DESCRIPTION:
XS GIS Cut Line= 6
609620.9701035985430052.66288309609576.5241035995430082.14778309
609527.2507035985430099.77938309609427.5505035995430110.68878309
609329.2440035995430212.85588309609248.5451035985430314.71998309
#Sta/Elev= 30
       0   43.68    5.93   43.31    9.88   41.56   18.77   41.06   51.36   42.15
   59.31   40.79    82.2      41   85.52   40.45  105.69   40.14  112.29   39.51
  123.24   40.09  123.78   40.64  125.73   40.72  197.29   41.01  202.26   40.54
  209.23   41.16  217.22   40.61  238.18   40.66  261.15   42.44  269.14   42.38
  277.12   41.31  281.12   41.93  286.11   41.46  331.04   41.33  373.01   43.59
     385   43.41     401   44.42  437.98   44.41  461.98   46.83  477.97   47.63
#Mann= 3 , 0 , 0
       0     .12       0  105.69     .04       0  123.24     .12       0
Bank Sta=105.69,123.24
XS Rating Curve= 0 ,0
Exp/Cntr=0.3,0.1

Type RM Length L Ch R = 1 ,1.3954  ,68.16,58.94,59.4
BEGIN DESCRIPTION:
BF3_37 (SEM 2019)
END DESCRIPTION:
XS GIS Cut Line= 6
609545.0359035985429976.55408309609480.1548035985430005.58748309
609448.9339035985430024.63758309609404.8431035985430046.45098309
609310.6491035995430058.83928309609165.2012035995430166.55298309
#Sta/Elev= 30
       0   42.41   10.55   42.11    16.3   40.33   24.78   40.81   31.33   40.38
   44.29   39.31   48.33   39.72   53.89   39.28   57.07   39.82   62.93   40.04
   71.45    39.5   72.37   40.36   73.36   40.34  171.99   40.74  216.53   40.55
  227.41   40.68  234.34   41.26  246.21   41.29  261.15   42.06  286.15   41.63
  289.15   41.26  350.15   41.59  370.15    42.2  379.15   43.65  391.15   43.83
  396.15   45.06  401.14   45.39  406.14   45.21  413.14   46.03  433.14   46.23
#Mann= 3 , 0 , 0
       0     .12       0   31.33     .04       0   73.36     .12       0
Bank Sta=31.33,73.36
XS Rating Curve= 0 ,0
Exp/Cntr=0.3,0.1

Type RM Length L Ch R = 1 ,1.3364  ,346.71,352.9,355.61
BEGIN DESCRIPTION:
BF3_36 (SEM 2019)
END DESCRIPTION:
XS GIS Cut Line= 6
609494.7650035985429928.26758309609472.5044035995429937.84988309
609434.3818035985429967.48748309609402.0687035985430020.11858309
609303.6429035985430054.06008309609160.0664035995430153.82528309
#Sta/Elev= 30
       0   42.16   13.57   41.94   19.39   40.18    53.8   40.19   62.87   39.86
   63.43   39.49   65.72   39.24   68.25   39.85   69.87   40.3371.75999   39.95
   98.42   40.36  123.33   40.01  138.25   40.43  140.23   40.13  148.16   40.36
  153.12   40.12  162.05   40.57  164.03   40.34  203.69   40.59  249.39   42.53
  281.36   41.22  292.35   41.59  307.33   41.27   338.3   41.67  358.28   42.29
  371.27   43.35  379.26   44.82  386.26   44.77  399.24   46.45  413.23   46.39
#Mann= 3 , 0 , 0
       0     .12       0   62.87     .04       0   68.25     .12       0
Bank Sta=62.87,68.25
XS Rating Curve= 0 ,0
Exp/Cntr=0.3,0.1

Type RM Length L Ch R = 1 ,0.9835  ,6.82,10.7,13.92
BEGIN DESCRIPTION:
BF3_35 (SEM 2019)
END DESCRIPTION:
XS GIS Cut Line= 6
609291.5510035995429760.58208309609266.7786035985429751.81628309
609235.0708035995429722.90608309609195.7548035985429715.53168309
609140.0830035985429666.10828309608915.1695035985429750.49488309
#Sta/Elev= 30
       0    41.3    8.76   41.18   18.49   39.92    25.3      40   28.27   39.32
   36.26   39.41   39.25   38.83   67.19   38.82   70.15   38.19   74.55   36.58
   85.47    36.8   91.46   37.95  111.73   39.27  124.72   38.91  139.71   39.89
   146.7   39.22   151.7   40.13  157.69   40.42  188.46      41  196.43   40.41
  240.29   41.51  263.21   40.84  295.11   40.76  326.01   41.45  352.92   41.15
  368.87   41.59   389.8   43.38  401.76   43.46  405.75   44.14  425.69    44.4
#Mann= 3 , 0 , 0
       0     .12       0   70.15     .04       0   91.46     .12       0
Bank Sta=70.15,91.46
XS Rating Curve= 0 ,0
Exp/Cntr=0.3,0.1

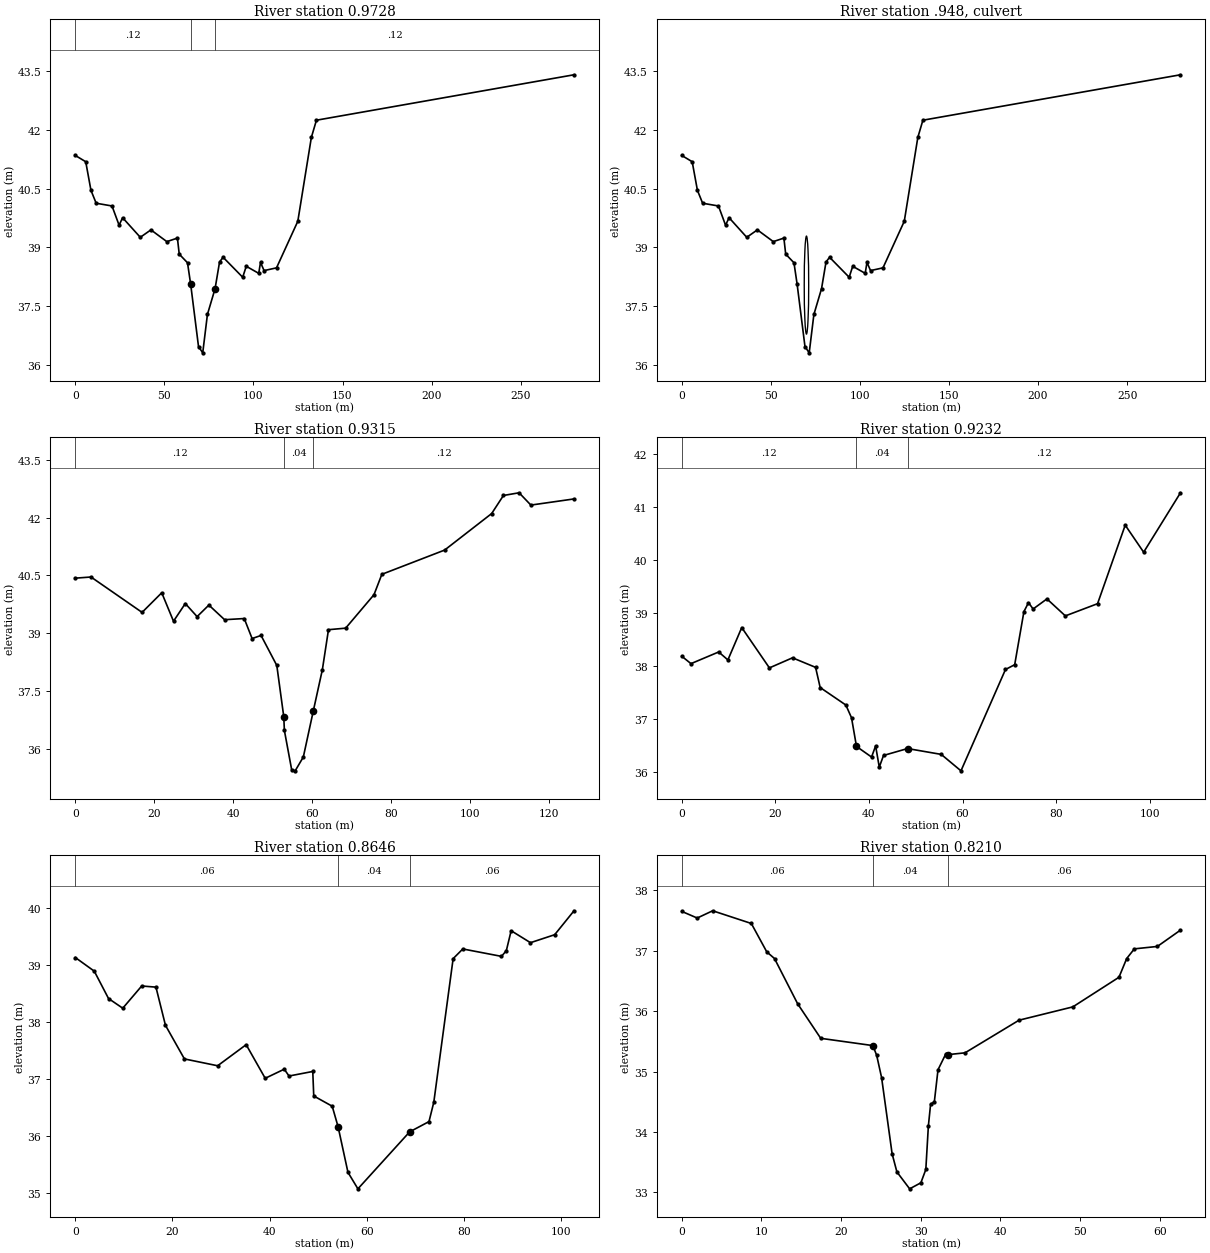
Type RM Length L Ch R = 1 ,0.9728  ,42.17,41.38,41.08
BEGIN DESCRIPTION:
US of BF3 Stream TCH Culvert - BF3_34 (SEM 2019)
END DESCRIPTION:
XS GIS Cut Line= 6
609283.2960035985429753.17378309609269.6922035985429751.84988309
609217.6909035985429709.35948309609187.9115035985429678.37688309
609185.9276035995429667.15068309609082.9402035985429565.65538309
#Sta/Elev= 30
       0   41.35    5.86   41.19    8.79   40.46   11.72   40.13   20.61   40.06
   24.58   39.57   26.57   39.76   36.49   39.26   42.45   39.45   51.38   39.15
   57.33   39.24   58.35   38.83   62.99   38.61   64.77   38.06   69.17   36.47
   71.54   36.31   74.17   37.29   78.47   37.95   80.98   38.63   82.98   38.75
   93.97   38.24   95.97   38.52  102.97   38.34  103.97   38.62  105.97   38.41
  112.96   38.48  124.91   39.67  132.51   41.81  135.36   42.25  279.95   43.41
#Mann= 3 , 0 , 0
       0     .12       0   64.77     .04       0   78.47     .12       0
Bank Sta=64.77,78.47
XS Rating Curve= 0 ,0
Exp/Cntr=0.3,0.1

Type RM Length L Ch R = 2 ,.948    ,,,
Node Photo=.\Photos\BF3-CR-7.JPG
BEGIN DESCRIPTION:
BF3 Stream TCH Culvert
END DESCRIPTION:
Node Name=BF3-CR-7
Bridge Culvert--1,0,-1,-1, 0
Deck Dist Width WeirC Skew NumUp NumDn MinLoCord MaxHiCord MaxSubmerge Is_Ogee
5,15.7,1.4,0, 297, 297, , , 0.98, 0, 3,3,,
     -15 -14.001-13.0021-12.0031-11.0042-10.0052-9.00629-8.00734-7.00839-6.00944
-5.01048-4.01153-3.01258-2.01363-1.01468   -.015.98321691.9821682.981119 3.98007
4.9790215.9779726.9769237.9758748.9748259.97377710.9727311.9716812.9706313.96958
14.9685315.9674816.9664317.9653918.9643419.9632920.9622421.9611922.9601423.95909
24.9580425.9569926.95594 27.954928.95385 29.952830.95175 31.950732.94965 33.9486
34.94755 35.946536.94545 37.944438.9433639.9423140.9412641.9402142.9391643.93811
44.9370745.9360246.9349747.9339248.9328749.9318250.9307751.9297252.9286753.92762
54.9265755.9255356.9244857.9234358.9223859.9213360.9202861.9192362.9181863.91713
64.9160865.9150466.9139967.9129468.9118969.9108470.9097971.9087472.9076973.90665
74.9055975.90455 76.903577.90245 78.901479.90035 80.899381.89825 82.897283.89616
 84.895185.8940686.8930187.8919688.8909189.8898690.8888191.8877692.8867193.88567
94.8846195.8835796.8825197.8814798.8804299.87937100.8783101.8773102.8762103.8752
104.8741105.8731 106.872 107.871108.8699109.8689110.8678111.8668112.8657113.8647
114.8636115.8626116.8615117.8605118.8594119.8584120.8573121.8563122.8552123.8542
124.8531125.8521126.8511  127.85 128.849129.8479130.8468131.8458132.8448133.8437
134.8427135.8416136.8406137.8395138.8385139.8374140.8364141.8353142.8343143.8332
144.8322145.8311146.8301 147.829 148.828149.8269150.8259151.8248152.8238153.8227
154.8217155.8206156.8196157.8185158.8175159.8164160.8154161.8143162.8133163.8122
164.8112165.8101166.8091 167.808 168.807169.8059170.8049171.8038172.8028173.8017
174.8007175.7997176.7986177.7975178.7965179.7955180.7944181.7934182.7923183.7913
184.7902185.7892186.7881187.7871 188.786 189.785190.7839191.7829192.7818193.7808
194.7797195.7787196.7776197.7766198.7755199.7745200.7734201.7724202.7713203.7703
204.7692205.7682206.7671207.7661 208.765 209.764210.7629211.7619212.7608213.7598
214.7587215.7577216.7566217.7556218.7545219.7535220.7525221.7514222.7504223.7493
224.7483225.7472226.7462227.7451228.7441 229.743 230.742231.7409232.7399233.7388
234.7378235.7367236.7357237.7346238.7336239.7325240.7315241.7304242.7294243.7283
244.7273245.7262246.7252247.7241248.7231 249.722 250.721251.7199252.7189253.7178
254.7168255.7157256.7147257.7137258.7126259.7115260.7105261.7094262.7084263.7073
264.7063265.7053266.7042267.7032268.7021 269.701   270.7271.6989272.6979273.6969
274.6958275.6948276.6937277.6927278.6916279.6906280.6895
 41.4416 41.4354 41.4312 41.4236 41.4408 41.4429 41.4408 41.4601 41.4523 41.4556
 41.4682 41.4596 41.4675 41.4732 41.4773 41.4804 41.4881 41.4943 41.5086 41.5074
 41.5104  41.519 41.5258 41.5343 41.5368  41.544 41.5386 41.5419 41.5431 41.5468
 41.5475 41.5578 41.5663 41.5616 41.5658 41.5691 41.5767 41.5816 41.5818 41.5867
 41.5908 41.6075  41.613 41.6244 41.6287 41.6388 41.6478 41.6644 41.6799 41.6774
 41.6931  41.704 41.7145 41.7264 41.7353 41.7505 41.7533 41.7523 41.7664 41.7776
 41.7825 41.7902 41.7999 41.8042 41.8162 41.8201 41.8284 41.8309 41.8444 41.8517
 41.8555 41.8573 41.8657 41.8683 41.8764 41.8791 41.8982 41.9137 41.9078  41.904
 41.9171  41.927 41.9304 41.9273 41.9336 41.9366 41.9533  41.964 41.9838  41.986
 41.9904 41.9982 42.0001 42.0203 42.0335 42.0408 42.0569 42.0604 42.0661 42.0796
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     -60 -59.001-58.0021-57.0031-56.0042-55.0052-54.0062-53.0073-52.0083-51.0094
-50.0104-49.0115-48.0125-47.0136-46.0146-45.0157-44.0167-43.0178-42.0188-41.0199
-40.0209 -39.022 -38.023-37.0241-36.0251-35.0262-34.0272-33.0283-32.0293-31.0304
-30.0314-29.0325-28.0335-27.0346-26.0356-25.0367-24.0377-23.0388-22.0398-21.0409
-20.0419 -19.043 -18.044-17.0451-16.0461-15.0472-14.0482-13.0493-12.0503-11.0514
-10.0524-9.05349-8.05454-7.05559-6.05664-5.05769-4.05874-3.05979-2.06083-1.06188
   -.062.93601451.9349652.9339173.9328684.931818 5.930776.9297217.9286728.927623
9.92657410.9255211.9244812.9234313.9223814.9213315.9202816.9192317.9181818.91713
19.9160820.9150421.9139922.9129423.9118924.9108425.9097926.9087427.9076928.90664
 29.905630.90455 31.903532.90245 33.901434.90035 35.899336.8982537.8972138.89616
39.8951140.8940641.8930142.8919643.8909144.8898645.8888146.8877647.8867148.88567
49.8846250.8835751.8825252.8814753.8804254.8793755.8783256.8772757.8762258.87518
59.8741360.8730861.8720362.8709863.8699364.8688865.8678466.8667867.8657468.86469
69.8636470.8625971.8615472.8604973.8594474.8583975.8573576.8562977.8552578.85419
79.85315 80.852181.85105   82.8583.84895 84.847985.84686 86.845887.84476 88.8437
89.8426690.8416191.8405692.8395193.8384694.8374295.8363696.8353297.8342798.83322
99.83217100.8311101.8301 102.829 103.828104.8269105.8259106.8248107.8238108.8227
109.8217110.8206111.8196112.8185113.8175114.8164115.8154116.8143117.8133118.8122
119.8112120.8101121.8091 122.808 123.807124.8059125.8049126.8038127.8028128.8017
129.8007130.7997131.7986132.7975133.7965134.7955135.7944136.7934137.7923138.7913
139.7902140.7892141.7881142.7871 143.786 144.785145.7839146.7829147.7818148.7808
149.7797150.7787151.7776152.7766153.7755154.7745155.7734156.7724157.7713158.7703
159.7692160.7682161.7671162.7661 163.765 164.764165.7629166.7619167.7608168.7598
169.7587170.7577171.7566172.7556173.7545174.7535175.7525176.7514177.7504178.7493
179.7483180.7472181.7462182.7451183.7441 184.743 185.742186.7409187.7399188.7388
189.7378190.7367191.7357192.7346193.7336194.7325195.7315196.7304197.7294198.7283
199.7273200.7262201.7252202.7241203.7231 204.722 205.721206.7199207.7189208.7178
209.7168210.7157211.7147212.7136213.7126214.7115215.7105216.7094217.7084218.7074
219.7063220.7052221.7042222.7032223.7021 224.701   225.7 226.699227.6979228.6969
229.6958230.6948231.6937232.6927233.6916234.6906235.6895
 41.4416 41.4354 41.4312 41.4236 41.4408 41.4429 41.4408 41.4601 41.4523 41.4556
 41.4682 41.4596 41.4675 41.4732 41.4773 41.4804 41.4881 41.4943 41.5086 41.5074
 41.5104  41.519 41.5258 41.5343 41.5368  41.544 41.5386 41.5419 41.5431 41.5468
 41.5475 41.5578 41.5663 41.5616 41.5658 41.5691 41.5767 41.5816 41.5818 41.5867
 41.5908 41.6075  41.613 41.6244 41.6287 41.6388 41.6478 41.6644 41.6799 41.6774
 41.6931  41.704 41.7145 41.7264 41.7353 41.7505 41.7533 41.7523 41.7664 41.7776
 41.7825 41.7902 41.7999 41.8042 41.8162 41.8201 41.8284 41.8309 41.8444 41.8517
 41.8555 41.8573 41.8657 41.8683 41.8764 41.8791 41.8982 41.9137 41.9078  41.904
 41.9171  41.927 41.9304 41.9273 41.9336 41.9366 41.9533  41.964 41.9838  41.986
 41.9904 41.9982 42.0001 42.0203 42.0335 42.0408 42.0569 42.0604 42.0661 42.0796
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BR Coef=-1 , 0 , 0 ,, 0 ,,,0.8,-1,,0,
WSPro=,,,, 1 ,,,, 0 ,,,, 0 ,,,,-1 ,-1 ,-1 , 0 , 0 , 0 , 0 , 0
Culvert=1,2.5,,39,0.024,0.9,1,2,3,36.79,70,36.318,56,Culvert #1  , 0 ,0.3
      70      56
BC Culvert Barrel=1,Barrel 1,0
Culvert Bottom n=0.024
BC Design=,, 0 ,, 0 ,,,,,,
BC Use User HTab Curves=0
BC User HTab FreeFlow(D)= 0

Type RM Length L Ch R = 1 ,0.9315  ,7.33,8.23,9.13
BEGIN DESCRIPTION:
DS of BF3 Stream TCH Culvert - BF3_33 (SEM 2019)
END DESCRIPTION:
XS GIS Cut Line= 4
609270.6077035985429712.66678309609238.1961035985429678.93228309
609219.0138035985429666.36458309609174.0346035995429631.96868309
#Sta/Elev= 30
       0   40.43    3.98   40.46   16.92   39.54    21.9   40.05   24.88   39.31
   27.87   39.77   30.86   39.43   33.84   39.73   37.82   39.35    42.8   39.38
   44.79   38.86   47.06   38.94   51.05   38.16   52.81   36.83   52.97   36.47
   54.83   35.44    55.7   35.42   57.77   35.78    60.3   36.98   62.59   38.05
   64.14   39.09   68.49   39.13   75.67      40   77.66   40.53   93.56   41.16
  105.48   42.11  108.46   42.58  112.43   42.65  115.41   42.33  126.34   42.49
#Mann= 3 , 0 , 0
       0     .12       0   52.81     .04       0    60.3     .12       0
Bank Sta=52.81,60.3
XS Rating Curve= 0 ,0
Exp/Cntr=0.3,0.1

Type RM Length L Ch R = 1 ,0.9232  ,69.01,58.62,40.07
BEGIN DESCRIPTION:
BF3_32 (SEM 2019)
END DESCRIPTION:
XS GIS Cut Line= 4
609264.7868035995429694.67498309609243.0909035985429674.56668309
609211.8701035995429648.63748309609179.3262035995429632.29938309
#Sta/Elev= 30
       0   38.19    1.97   38.05    7.89   38.27    9.86   38.12   12.82   38.73
   18.73   37.97   23.67   38.16    28.6   37.98   29.58    37.6   35.07   37.27
   36.28   37.03   37.34   36.49   40.56   36.29   41.43    36.5   42.21    36.1
   43.12   36.32   48.25   36.45   55.45   36.34   59.67   36.03   69.18   37.94
   71.15   38.03   73.12   39.03    74.1    39.2   75.09   39.08   78.04   39.27
   81.98   38.95   88.86   39.18   94.77   40.66   98.71   40.15  106.58   41.27
#Mann= 3 , 0 , 0
       0     .12       0   37.34     .04       0   48.25     .12       0
Bank Sta=37.34,48.25
XS Rating Curve= 0 ,0
Exp/Cntr=0.3,0.1

Type RM Length L Ch R = 1 ,0.8646  ,30.24,43.58,49.8
BEGIN DESCRIPTION:
BF3_31 (SEM 2019)
END DESCRIPTION:
XS GIS Cut Line= 5
609267.3816035995429637.70158309609245.7971035985429616.46868309
609227.3747035985429619.05698309609217.3602035995429633.95308309
609181.6413035985429631.30718309
#Sta/Elev= 30
       0   39.14    3.91    38.9    6.84   38.42    9.77   38.25   13.67   38.64
    16.6   38.62   18.56   37.95   22.46   37.36    29.3   37.24   35.17   37.61
   39.09   37.02   43.01   37.18   43.99   37.06   48.88   37.14   49.08   36.71
   52.88   36.53   54.09   36.17   56.12   35.37   58.17   35.08   68.82   36.08
    72.8   36.26   73.79    36.6   77.77   39.12   79.76   39.29   87.72   39.16
   88.72   39.26   89.71   39.61   93.69    39.4   98.67   39.54  102.65   39.96
#Mann= 3 , 0 , 0
       0     .06       0   54.09     .04       0   68.82     .06       0
Bank Sta=54.09,68.82
XS Rating Curve= 0 ,0
Exp/Cntr=0.3,0.1

Type RM Length L Ch R = 1 ,0.8210  ,8.41,8.22,7.78
BEGIN DESCRIPTION:
US of Dominic Street 3 Bridge - BF3_30B (SEM 2019)
END DESCRIPTION:
XS GIS Cut Line= 4
609257.8547035995429614.77068309609247.3772035995429600.80068309
609232.1372035985429587.78318309609211.9759035995429572.86058309
#Sta/Elev= 30
       0   37.65    1.94   37.54    3.88   37.66    8.73   37.45   10.67   36.98
   11.64   36.87   14.55   36.12   17.44   35.55   23.98   35.43   24.46   35.27
   25.08    34.9    26.4   33.64      27   33.34    28.6   33.06   30.01   33.16
   30.63   33.38   30.95    34.1   31.23   34.46    31.7    34.5   32.16   35.03
   33.13   35.29    33.4   35.28   35.55   35.31   42.33   35.85   49.08   36.07
   54.87   36.56   55.84   36.87    56.8   37.03   59.69   37.07   62.59   37.34
#Mann= 3 , 0 , 0
       0     .06       0   23.98     .04       0    33.4     .06       0
Bank Sta=23.98,33.4
XS Rating Curve= 0 ,0
Exp/Cntr=0.3,0.1