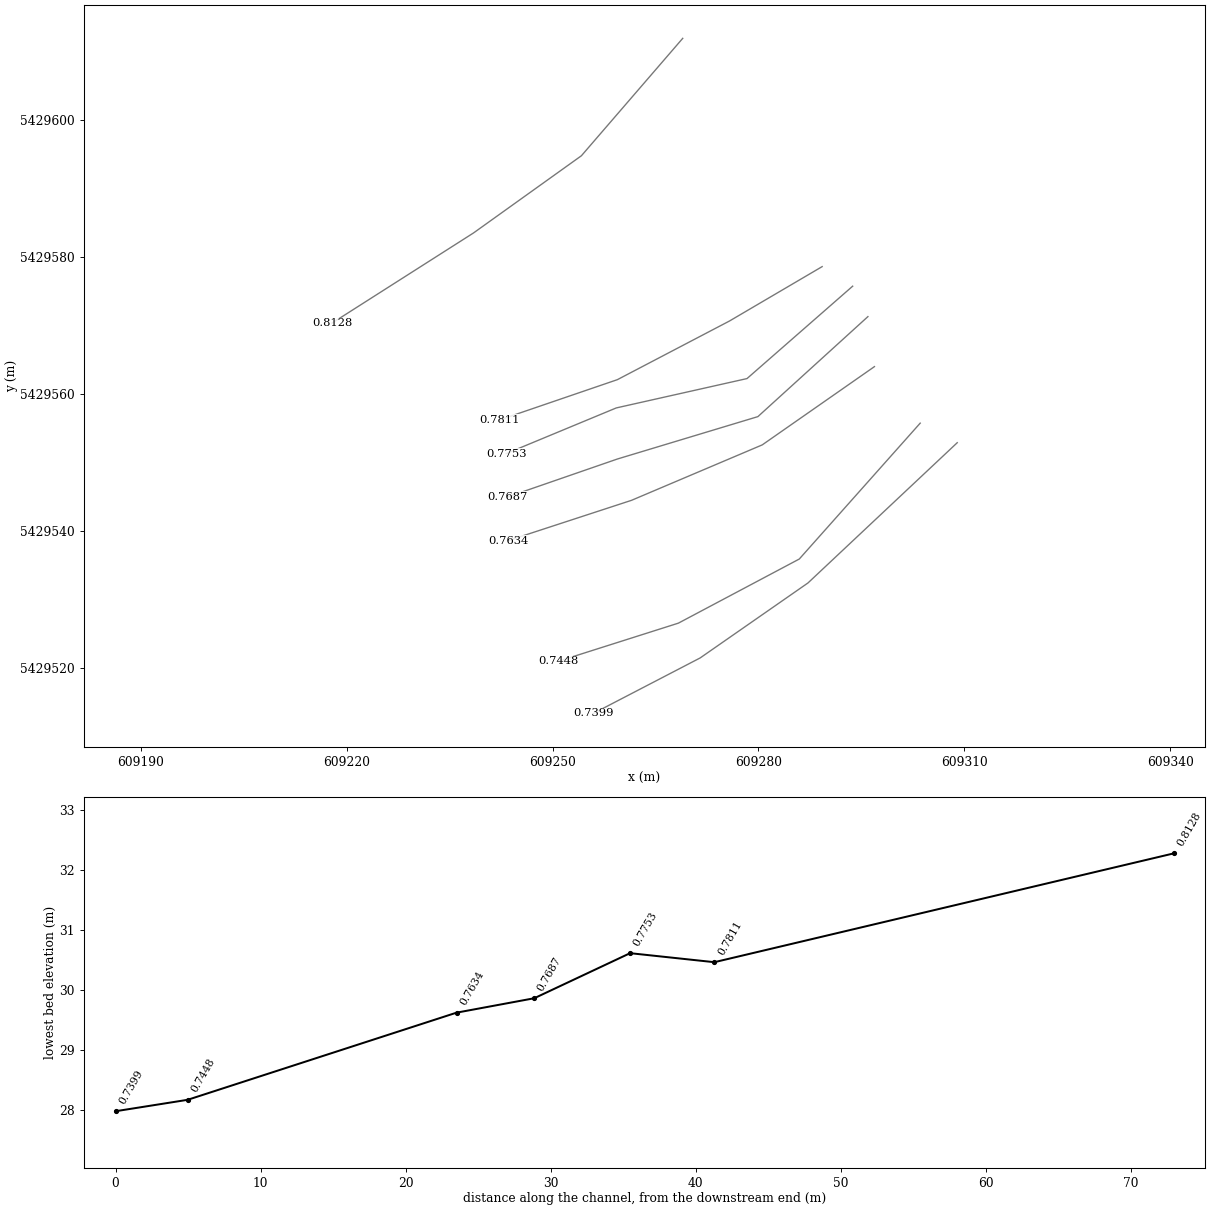
HEC-RAS study Exploits_FMM.prj: Exploits_FMM

--- Exploits_FMM.g01 (geometry) --- (continued)

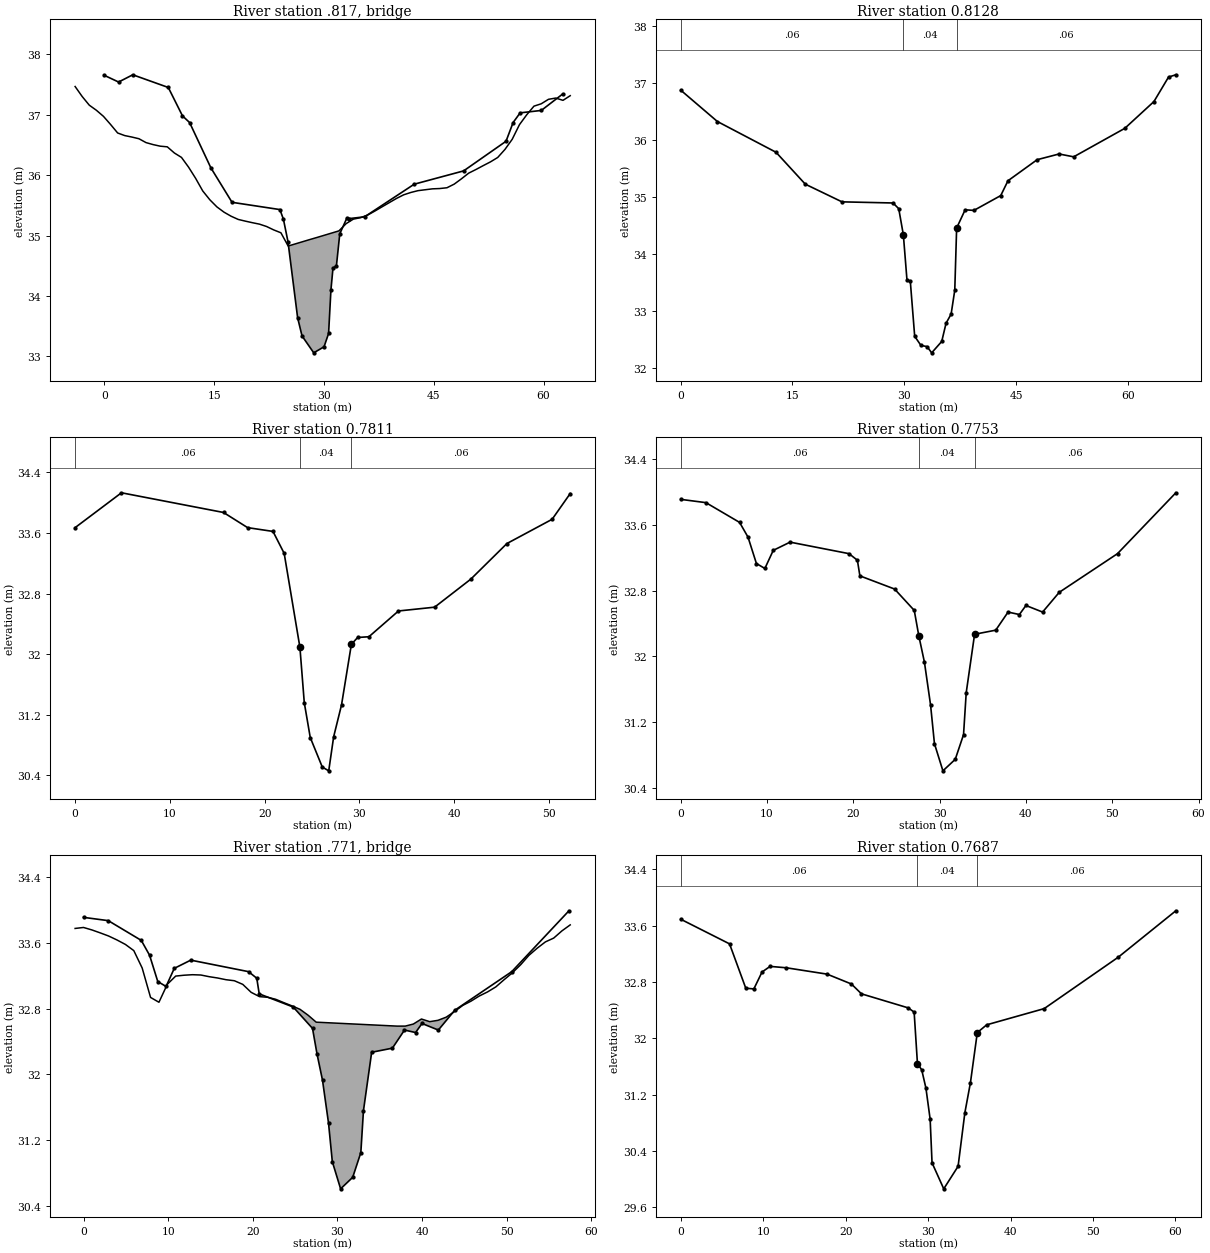
Type RM Length L Ch R = 3 ,.817    ,,,
Node Photo=.\Photos\BF3-CR-6.JPG
BEGIN DESCRIPTION:
Dominic Street 3 Bridge
END DESCRIPTION:
Node Name=BF3-CR-6
Bridge Culvert--1,0,-1,-1, 0
Deck Dist Width WeirC Skew NumUp NumDn MinLoCord MaxHiCord MaxSubmerge Is_Ogee
1.6,3.3,1.4,0, 70, 70, , , 0.98, 0, 3,3,,
      -4  -3.031  -2.062  -1.094   -.125    .844   1.813   2.781    3.75   4.719
   5.688   6.656   7.625   8.594   9.563  10.532    11.5  12.469  13.438  14.407
  15.375  16.344  17.313  18.282   19.25  20.219  21.188  22.157  23.126  24.117
  25.108    26.1  27.091  28.083  29.074  30.066  31.057  32.048   33.03  34.012
  34.993  35.975  36.957  37.938   38.92  39.902  40.883  41.865  42.846  43.828
  44.819  45.809    46.8  47.791  48.781  49.772  50.763  51.753  52.744  53.735
  54.725  55.716  56.707  57.697  58.688  59.679  60.669   61.66  62.651  63.641
  37.466    37.3  37.157  37.073  36.972  36.838  36.697  36.654   36.63  36.602
  36.538  36.505  36.479  36.468  36.366  36.293  36.132  35.946  35.738  35.592
  35.474  35.387   35.32  35.267  35.239  35.213  35.189   35.15  35.094  35.046
  34.827  34.863  34.899  34.935   34.97  35.006  35.042  35.078  35.198  35.272
  35.296   35.34  35.406  35.476  35.545  35.614  35.674  35.713  35.743  35.758
  35.773  35.778  35.791  35.851  35.939  36.033  36.093  36.157  36.219  36.292
  36.425  36.593  36.835  36.998  37.141   37.18  37.254  37.275  37.237  37.314
  34.427  34.463  34.499  34.535   34.57  34.606  34.642  34.678
       1   1.969   2.938   3.906   4.875   5.844   6.813   7.781    8.75   9.719
  10.688  11.656  12.625  13.594  14.563  15.532    16.5  17.469  18.438  19.407
  20.375  21.344  22.313  23.282   24.25  25.219  26.188  27.157  28.126  29.117
  30.108    31.1  32.091  33.083  34.074  35.066  36.057  37.048   38.03  39.012
  39.993  40.975  41.957  42.938   43.92  44.902  45.883  46.865  47.846  48.828
  49.819  50.809    51.8  52.791  53.781  54.772  55.763  56.753  57.744  58.735
  59.725  60.716  61.707  62.697  63.688  64.679  65.669   66.66  67.651  68.641
 37.4658 37.2995 37.1568 37.0726 36.9715 36.8381  36.697 36.6539 36.6299 36.6018
 36.5375 36.5048 36.4793 36.4675 36.3661 36.2926 36.1319 35.9462 35.7384 35.5917
 35.4739 35.3872 35.3203  35.267 35.2385 35.2134  35.189 35.1503 35.0937 35.0461
  34.82734.8628634.8987234.9345734.9704335.0062935.04214  35.078 35.1978 35.2717
 35.2959 35.3397 35.4063 35.4763 35.5453 35.6143 35.6739 35.7127 35.7433 35.7579
 35.7726 35.7783 35.7913 35.8507 35.9393  36.033 36.0928 36.1567 36.2188  36.292
 36.4246 36.5931 36.8353 36.9975 37.1408 37.1797 37.2538 37.2752 37.2367 37.3136
  34.42734.4628634.4987134.5345734.5704334.6062934.64214  34.678
BR Coef=-1 , 0 , 0 ,, 0 ,,,0.8,-1,,0,
WSPro=,,,, 1 ,,,, 0 ,,,, 0 ,,,,-1 ,-1 ,-1 , 0 , 0 , 0 , 0 , 0
BC Design=,, 0 ,, 0 ,,,,,,
BC Use User HTab Curves=0
BC User HTab FreeFlow(D)= 0

Type RM Length L Ch R = 1 ,0.8128  ,31.72,31.67,31.27
BEGIN DESCRIPTION:
DS of Dominic Street 3 Bridge - BF3_30A (SEM 2019)
END DESCRIPTION:
XS GIS Cut Line= 4
609268.9673035985429611.91318309609254.2035035985429594.76818309
609238.4872035985429583.49688309609217.8496035985429570.32058309
#Sta/Elev= 30
       0   36.88    4.92   36.33   12.79   35.79   16.72   35.23   21.64   34.92
   28.49    34.9   29.26    34.8   29.88   34.34   30.37   33.54   30.81   33.53
    31.4   32.56   32.24    32.4   33.06   32.38   33.68   32.27   35.03   32.47
   35.61   32.79   36.29   32.95   36.78   33.37   37.03   34.46   38.17   34.78
   39.35   34.77   42.95   35.03   43.92   35.29   47.84   35.66   50.78   35.76
   52.74   35.71    59.6   36.21   63.51   36.68   65.47   37.11   66.45   37.15
#Mann= 3 , 0 , 0
       0     .06       0   29.88     .04       0   37.03     .06       0
Bank Sta=29.88,37.03
XS Rating Curve= 0 ,0
Exp/Cntr=0.3,0.1

Type RM Length L Ch R = 1 ,0.7811  ,6.68,5.81,4.83
BEGIN DESCRIPTION:
BF3_30 (SEM 2019)
END DESCRIPTION:
XS GIS Cut Line= 4
609289.2873035995429578.57558309609275.7935035985429570.63808309
609259.4422035985429562.06558309609242.2972035995429556.19188309
#Sta/Elev= 22
       0   33.67    4.89   34.13   15.66   33.87    18.2   33.67   20.88   33.62
   22.06   33.33   23.72   32.09   24.18   31.36   24.81    30.9   26.08   30.51
   26.76   30.46   27.28   30.91   28.11   31.33   29.15   32.13   29.81   32.22
      31   32.23   34.12   32.57   37.93   32.62   41.75   32.99   45.56   33.46
   50.33   33.78   52.24   34.12
#Mann= 3 , 0 , 0
       0     .06       0   23.72     .04       0   29.15     .06       0
Bank Sta=23.72,29.15
XS Rating Curve= 0 ,0
Exp/Cntr=0.3,0.1

Type RM Length L Ch R = 1 ,0.7753  ,6.36,6.61,6.88
BEGIN DESCRIPTION:
US of Dominic Street 2 Bridge - BF3_29 (SEM 2019)
END DESCRIPTION:
XS GIS Cut Line= 4
609293.7323035985429575.71808309609278.3335035985429562.22438309
609259.2835035995429557.93808309609243.2497035985429551.27058309
#Sta/Elev= 30
       0   33.91    2.92   33.87    6.82   33.63     7.8   33.45    8.77   33.13
    9.75   33.07   10.72   33.29   12.67   33.39    19.5   33.25   20.47   33.17
   20.76   32.98   24.78   32.82   27.06   32.56   27.59   32.25   28.24   31.93
   28.95   31.41    29.4   30.94   30.38   30.61   31.81   30.75   32.77   31.05
   33.08   31.56   34.05   32.27    36.5   32.32   37.93   32.54   39.24   32.51
      40   32.62   41.93   32.54   43.86   32.78   50.61   33.25   57.37   33.99
#Mann= 3 , 0 , 0
       0     .06       0   27.59     .04       0   34.05     .06       0
Bank Sta=27.59,34.05
XS Rating Curve= 0 ,0
Exp/Cntr=0.3,0.1

Type RM Length L Ch R = 3 ,.771    ,,,
Node Photo=.\Photos\BF3-CR-5.JPG
BEGIN DESCRIPTION:
Dominic Street 2 Bridge
END DESCRIPTION:
Node Name=BF3-CR-5
Bridge Culvert--1,0,-1,-1, 0
Deck Dist Width WeirC Skew NumUp NumDn MinLoCord MaxHiCord MaxSubmerge Is_Ogee
1.3,3.3,1.4,0, 61, 61, , , 0.98, 0, 3,3,,
      -1  -.0092.9815799 1.97237 2.96316 3.95395 4.94474 5.93553 6.926327.917109
  8.90799.89868910.8894811.8802712.8710613.8618514.8526415.8434316.8342217.82501
 18.815819.8065920.7973821.7541522.7109123.6676824.6244425.5812126.5379827.49475
28.4515129.4082830.3650531.3218132.2785833.2353434.1921135.1488836.1056437.06241
38.0191838.9759439.9327140.9096341.8865442.8634543.8403744.81728 45.794246.77111
47.7480348.7249449.7018650.6787751.65569 52.632653.6095254.5864355.5633556.54026
57.51717
 33.7752 33.7871 33.7573 33.7212 33.6831 33.6349 33.5808 33.5059 33.2944 32.9367
 32.8781 33.0967 33.1963 33.2067 33.2129 33.2092 33.1887 33.1729 33.1521 33.1396
 33.0954 32.9986 32.9463 32.9387 32.9139 32.8731 32.8342 32.7922 32.7205  32.636
 32.6312 32.6264 32.6216 32.6168  32.612 32.6072 32.6024 32.5976 32.5928  32.588
 32.5882 32.6132 32.6744 32.6423 32.6584  32.697 32.7649 32.8398 32.8918 32.9542
 33.0038 33.0647 33.1522 33.2359 33.3338  33.448  33.535 33.6119  33.658 33.7459
 33.8186
                                                                          32.236
 32.2312 32.2264 32.2216 32.2168  32.212 32.2072 32.2024 32.1976 32.1928  32.188
      -1  -.0092.9815799 1.97237 2.96316 3.95395 4.94474 5.93553 6.926327.917109
  8.90799.89868910.8894811.8802712.8710613.8618514.8526415.8434316.8342217.82501
 18.815819.8065920.7973821.7541522.7109123.6676824.6244425.5812126.5379827.49475
28.4515129.4082830.3650531.3218132.2785833.2353434.1921135.1488836.1056437.06241
38.0191838.9759439.9327140.9096341.8865442.8634543.8403744.81728 45.794246.77111
47.7480348.7249449.7018650.6787751.65569 52.632653.6095254.5864355.5633556.54026
57.51717
 33.7752 33.7871 33.7573 33.7212 33.6831 33.6349 33.5808 33.5059 33.2944 32.9367
 32.8781 33.0967 33.1963 33.2067 33.2129 33.2092 33.1887 33.1729 33.1521 33.1396
 33.0954 32.9986 32.9463 32.9387 32.9139 32.8731 32.8342 32.7922 32.7205  32.562
 32.5611 32.5602 32.5593 32.5584 32.5575 32.5566 32.5557 32.5548 32.5539  32.553
 32.5882 32.6132 32.6744 32.6423 32.6584  32.697 32.7649 32.8398 32.8918 32.9542
 33.0038 33.0647 33.1522 33.2359 33.3338  33.448  33.535 33.6119  33.658 33.7459
 33.8186
                                                                          32.162
 32.1611 32.1602 32.1593 32.1584 32.1575 32.1566 32.1557 32.1548 32.1539  32.153
BR Coef=-1 , 0 , 0 ,, 0 ,,,0.8,-1,,0,
WSPro=,,,, 1 ,,,, 0 ,,,, 0 ,,,,-1 ,-1 ,-1 , 0 , 0 , 0 , 0 , 0
BC Design=,, 0 ,, 0 ,,,,,,
BC Use User HTab Curves=0
BC User HTab FreeFlow(D)= 0

Type RM Length L Ch R = 1 ,0.7687  ,4.88,5.36,5.77
BEGIN DESCRIPTION:
DS of Dominic Street 2 Bridge - BF3_28 (SEM 2019)
END DESCRIPTION:
XS GIS Cut Line= 4
609295.9548035985429571.27308309609279.9210035985429556.66808309
609259.4422035985429550.47678309609243.4084035985429544.92058309
#Sta/Elev= 26
       0   33.69    5.92   33.34    7.89   32.71    8.87    32.7    9.86   32.94
   10.84   33.02   12.82      33   17.75   32.91    20.7   32.77   21.92   32.63
   27.61   32.43   28.31   32.37   28.71   31.64   29.23   31.55   29.74   31.29
   30.25   30.85   30.48   30.23    31.9   29.86   33.64   30.18   34.46   30.94
   35.14   31.37   35.97   32.08   37.11   32.19   44.08   32.42   53.06   33.15
   60.05   33.81
#Mann= 3 , 0 , 0
       0     .06       0   28.71     .04       0   35.97     .06       0
Bank Sta=28.71,35.97
XS Rating Curve= 0 ,0
Exp/Cntr=0.3,0.1

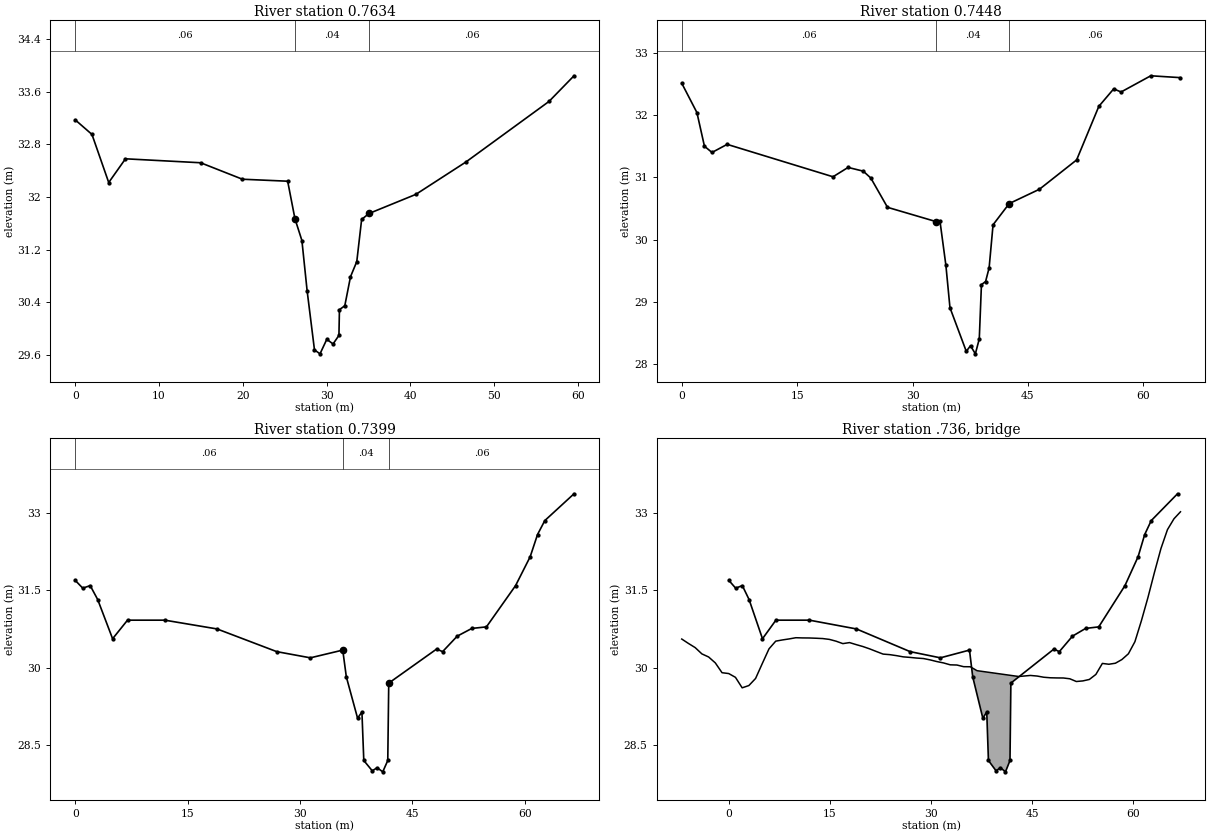
Type RM Length L Ch R = 1 ,0.7634  ,18.61,18.54,19.11
BEGIN DESCRIPTION:
BF3_27 (SEM 2019)
END DESCRIPTION:
XS GIS Cut Line= 4
609296.9073035985429563.97058309609280.5560035995429552.54058309
609261.5060035995429544.44428309609243.5672035985429538.57058309
#Sta/Elev= 25
       0   33.17    1.99   32.95    3.99   32.22    5.99   32.58   14.96   32.52
   19.95   32.27   25.35   32.24   26.22   31.67   27.05   31.34   27.67   30.58
   28.55   29.68   29.21   29.62   30.02   29.84   30.77   29.77   31.47    29.9
   31.53   30.29   32.17   30.35   32.85   30.79    33.6   31.02   34.18   31.66
   35.06   31.75   40.65   32.04   46.61   32.53   56.54   33.45   59.53   33.84
#Mann= 3 , 0 , 0
       0     .06       0   26.22     .04       0   35.06     .06       0
Bank Sta=26.22,35.06
XS Rating Curve= 0 ,0
Exp/Cntr=0.3,0.1

Type RM Length L Ch R = 1 ,0.7448  ,4.59,4.97,5.6
BEGIN DESCRIPTION:
BF3_26 (SEM 2019)
END DESCRIPTION:
XS GIS Cut Line= 4
609303.5748035985429555.71558309609285.9535035985429535.87178309
609268.3322035995429526.50548309609250.8697035985429520.94928309
#Sta/Elev= 30
       0   32.51    1.97   32.04    2.95    31.5    3.93    31.4     5.9   31.53
   19.66   31.01   21.62   31.16   23.59    31.1   24.57   30.99   26.74   30.52
   33.08   30.29   33.56    30.3   34.33   29.59   34.86   28.91   36.98   28.21
   37.53    28.3   38.16   28.17   38.67   28.41   38.95   29.28   39.49   29.33
   39.95   29.55   40.46   30.24   42.56   30.58   46.49   30.81   51.32   31.28
   54.21   32.14   56.14   32.42    57.1   32.37   60.96   32.63   64.82    32.6
#Mann= 3 , 0 , 0
       0     .06       0   33.08     .04       0   42.56     .06       0
Bank Sta=33.08,42.56
XS Rating Curve= 0 ,0
Exp/Cntr=0.3,0.1

Type RM Length L Ch R = 1 ,0.7399  ,7.71,9.91,11.69
BEGIN DESCRIPTION:
US of Dominic Street 1 Bridge - BF3_25 (SEM 2019)
END DESCRIPTION:
XS GIS Cut Line= 4
609308.9723035985429552.85808309609287.2235035985429532.37928309
609271.5073035985429521.42548309609255.9497035985429513.32928309
#Sta/Elev= 30
       0   31.69       1   31.54    1.99   31.59    2.99   31.32    4.98   30.56
    6.97   30.92   11.95   30.92   18.92   30.75   26.89   30.31   31.38   30.19
    35.7   30.34   36.18   29.82   37.68   29.02   38.26   29.14   38.51    28.2
   39.64      28   40.29   28.06   41.04   27.98   41.71    28.2   41.84    29.7
   48.23   30.36   49.03   30.31   50.98   30.61   52.93   30.76   54.88   30.79
   58.77   31.59   60.72   32.15    61.7   32.58   62.67   32.85   66.57   33.37
#Mann= 3 , 0 , 0
       0     .06       0    35.7     .04       0   41.84     .06       0
Bank Sta=35.7,41.84
XS Rating Curve= 0 ,0
Exp/Cntr=0.3,0.1

Type RM Length L Ch R = 3 ,.736    ,,,
Node Photo=.\Photos\BF3-CR-4.JPG
BEGIN DESCRIPTION:
Dominic Street 1 Bridge
END DESCRIPTION:
Node Name=BF3-CR-4
Bridge Culvert--1,0,-1,-1, 0
Deck Dist Width WeirC Skew NumUp NumDn MinLoCord MaxHiCord MaxSubmerge Is_Ogee
1.6,3.6,1.4,0, 76, 76, , , 0.98, 0, 3,3,,
      -7-6.00396-5.00793-4.01189-3.01586-2.01983-1.02379   -.027.96827041.964304
2.9603383.9563724.952405 5.948446.9444737.9405078.9365419.93257410.9286111.92464
12.9206813.9167114.9127415.9087816.9048117.9008418.8968819.8929120.8889521.88498
22.8810123.8770524.8730825.8691226.8651527.8611828.8572229.8532530.8492931.84532
32.8413533.8373934.8334235.8243336.8152437.8061538.7970639.7879740.7788841.76979
 42.760743.0152444.7425245.7334346.7243447.69032 48.656349.6222850.5882651.55424
52.52022 53.486254.4521855.4181656.3841457.35012 58.316159.2820960.2480761.21405
62.1800363.1460164.1119965.0779766.0439567.00993
 30.5542 30.4685 30.3881 30.2662 30.2067 30.0917 29.9017 29.8851  29.812 29.6086
 29.6527 29.7903 30.0798 30.3642 30.5133 30.5368 30.5566 30.5798 30.5758 30.5747
 30.5698 30.5636 30.5472 30.5123 30.4655 30.4853 30.4457 30.4085 30.3634 30.3124
 30.2623 30.2516 30.2322 30.2089 30.1984 30.1855 30.1764 30.1502 30.1177 30.0912
 30.0545 30.0505 30.0183 30.0168  29.94129.9229429.9048829.8868229.86876 29.8507
29.83264  29.828 29.8484 29.8369 29.8137 29.8034 29.8002 29.7993 29.7839  29.731
 29.7426 29.7707 29.8679 30.0815 30.0656 30.0853 30.1567 30.2686 30.5028 30.9109
 31.3585 31.8455 32.3089 32.6749 32.8854 33.0208
                                  29.54129.5229429.5048829.4868229.46876 29.4507
29.43264  29.428
      -2-1.00396  -.0079.98810141.9841352.9801693.9762034.972237 5.968276.964304
7.9603388.9563729.95240610.9484411.9444712.9405113.9365414.9325715.9286116.92464
17.9206818.9167119.9127420.9087821.9048122.9008423.8968824.8929125.8889526.88498
27.8810128.8770529.8730830.8691231.8651532.8611833.8572234.8532535.8492936.84532
37.8413538.8373939.8334240.8243341.8152442.8061543.7970644.7879745.7788846.76979
 47.760748.0152449.7425250.7334351.7243452.69032 53.656354.6222855.5882656.55424
57.52022 58.486259.4521860.4181661.3841462.35012 63.316164.2820965.2480766.21405
67.1800368.1460169.1119970.0779771.0439572.00993
 30.5542 30.4685 30.3881 30.2662 30.2067 30.0917 29.9017 29.8851  29.812 29.6086
 29.6527 29.7903 30.0798 30.3642 30.5133 30.5368 30.5566 30.5798 30.5758 30.5747
 30.5698 30.5636 30.5472 30.5123 30.4655 30.4853 30.4457 30.4085 30.3634 30.3124
 30.2623 30.2516 30.2322 30.2089 30.1984 30.1855 30.1764 30.1502 30.1177 30.0912
 30.0545 30.0505 30.0183 30.0168  29.85329.8616329.8702629.8788929.8875229.89615
29.90478  29.907 29.8484 29.8369 29.8137 29.8034 29.8002 29.7993 29.7839  29.731
 29.7426 29.7707 29.8679 30.0815 30.0656 30.0853 30.1567 30.2686 30.5028 30.9109
 31.3585 31.8455 32.3089 32.6749 32.8854 33.0208
                                  29.45329.4616329.4702629.4788929.4875229.49615
29.50478  29.507
BR Coef=-1 , 0 , 0 ,, 0 ,,,0.8,-1,,0,
WSPro=,,,, 1 ,,,, 0 ,,,, 0 ,,,,-1 ,-1 ,-1 , 0 , 0 , 0 , 0 , 0
BC Design=,, 0 ,, 0 ,,,,,,
BC Use User HTab Curves=0
BC User HTab FreeFlow(D)= 0