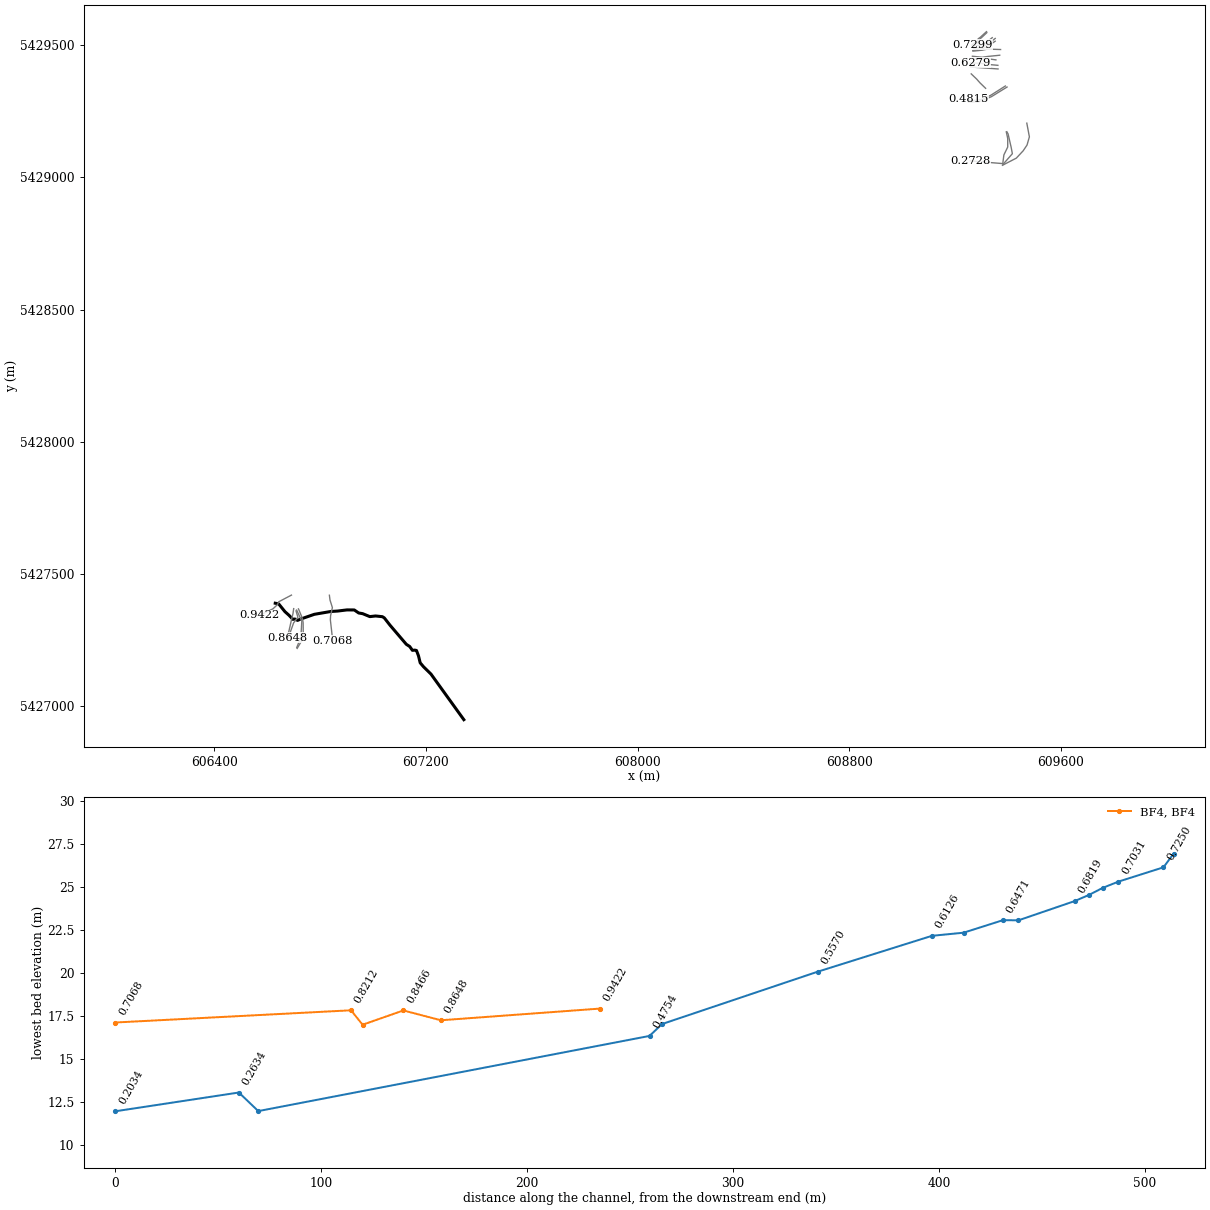
HEC-RAS study Exploits_FMM.prj: Exploits_FMM

--- Exploits_FMM.g01 (geometry) --- (continued)

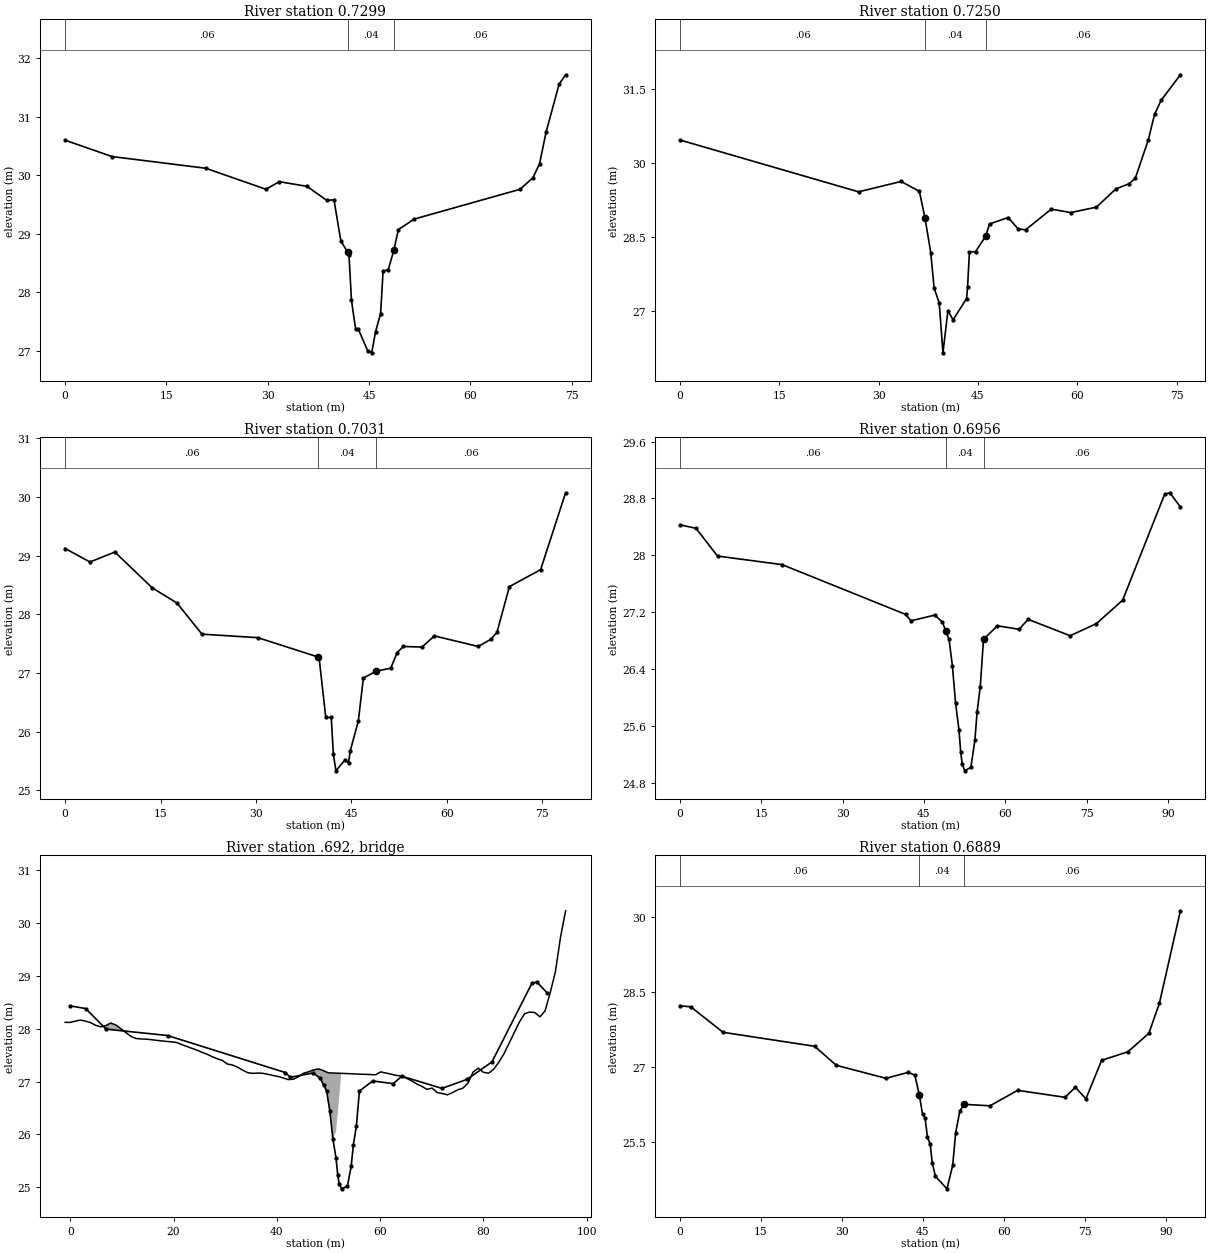
Type RM Length L Ch R = 1 ,0.7299  ,4.14,4.98,4.88
BEGIN DESCRIPTION:
DS of Dominic Street 1 Bridge - BF3_24 (SEM 2019)
END DESCRIPTION:
XS GIS Cut Line= 6
609319.6086035995429551.27058309609295.4786035995429529.20428309
609288.0173035985429523.96548309609284.5248035985429516.50428309
609279.1273035985429512.53548309609265.3160035985429502.05798309
#Sta/Elev= 29
       0    30.6    6.94   30.32   20.81   30.12   29.73   29.76   31.71   29.89
    35.8   29.81   38.73   29.57    39.8   29.58   40.81   28.88   41.82   28.68
   42.02   28.64   42.39   27.86   43.01   27.36   43.42   27.36   44.77      27
   45.39   26.96   45.95   27.32    46.7   27.63   47.07   28.36   47.83   28.38
   48.67   28.72   49.33   29.07   51.68   29.25   67.35   29.76   69.27   29.96
   70.24    30.2    71.2   30.74   73.13   31.56   74.09   31.72
#Mann= 3 , 0 , 0
       0     .06       0   41.82     .04       0   48.67     .06       0
Bank Sta=41.82,48.67
XS Rating Curve= 0 ,0
Exp/Cntr=0.3,0.1

Type RM Length L Ch R = 1 ,0.7250  ,24.82,21.84,18.36
BEGIN DESCRIPTION:
BF3_23 (SEM 2019)
END DESCRIPTION:
XS GIS Cut Line= 5
609320.8786035985429547.30178309609300.3998035985429528.25178309
609293.0973035985429522.69548309609286.7473035995429510.15428309
609265.1572035985429498.88298309
#Sta/Elev= 30
       0   30.47   26.97   29.42   33.39   29.63   36.15   29.43   36.99    28.9
   37.87   28.19   38.38   27.47   39.15   27.17   39.71   26.16   40.46   27.01
   41.25   26.83   43.28   27.26   43.43   27.49   43.71    28.2   44.64   28.21
   46.15   28.52   46.75   28.77   49.56    28.9   51.05   28.67   52.18   28.65
   56.07   29.07      59      29   62.89   29.11   65.82   29.48   67.76   29.58
   68.74   29.69   70.69   30.46   71.66   30.99   72.64   31.27   75.56   31.79
#Mann= 3 , 0 , 0
       0     .06       0   36.99     .04       0   46.15     .06       0
Bank Sta=36.99,46.15
XS Rating Curve= 0 ,0
Exp/Cntr=0.3,0.1

Type RM Length L Ch R = 1 ,0.7031  ,7.67,7.57,7.42
BEGIN DESCRIPTION:
BF3_22 (SEM 2019)
END DESCRIPTION:
XS GIS Cut Line= 4
609341.3574035985429528.41048309609315.7986035985429507.13798309
609299.1298035985429500.47048309609271.8248035985429497.13668309
#Sta/Elev= 30
       0   29.12    3.91   28.89    7.82   29.06   13.69   28.45    17.6   28.19
   21.52   27.66   30.32    27.6   39.79   27.27   39.95   27.25   40.99   26.24
   41.85   26.24   42.19   25.61   42.59   25.33   43.96   25.51   44.58   25.47
   44.84   25.67   46.11   26.18    46.9   26.91   48.92   27.03   51.22   27.08
   52.19   27.34   53.17   27.45   56.12   27.44   58.08   27.63   64.96   27.45
   66.92   27.57   67.91   27.69   69.87   28.47   74.78   28.76   78.71   30.07
#Mann= 3 , 0 , 0
       0     .06       0   39.79     .04       0   48.92     .06       0
Bank Sta=39.79,48.92
XS Rating Curve= 0 ,0
Exp/Cntr=0.3,0.1

Type RM Length L Ch R = 1 ,0.6956  ,6.59,6.68,6.75
BEGIN DESCRIPTION:
US of Beaumont Heights 2 Bridge - BF3_21 (SEM 2019)
END DESCRIPTION:
XS GIS Cut Line= 4
609352.6287035985429525.55298309609318.6561035985429499.83548309
609299.2886035985429492.69168309609270.7135035985429487.45298309
#Sta/Elev= 30
       0   28.43    2.97   28.38    6.94   27.99   18.83   27.87   41.62   27.17
   42.61   27.08   47.01   27.16   48.42   27.06   49.06   26.93   49.63   26.82
   50.25   26.45   50.84   25.92   51.46   25.55   51.79   25.23   52.06   25.07
   52.52   24.97   53.66   25.02    54.4    25.4   54.81    25.8   55.39   26.15
   55.99   26.82   58.56   27.01   62.53   26.96   64.22    27.1   71.97   26.87
   76.81   27.04   81.65   27.37    89.4   28.86   90.37   28.88    92.3   28.68
#Mann= 3 , 0 , 0
       0     .06       0   49.06     .04       0   55.99     .06       0
Bank Sta=49.06,55.99
XS Rating Curve= 0 ,0
Exp/Cntr=0.3,0.1

Type RM Length L Ch R = 3 ,.692    ,,,
Node Photo=.\Photos\BF3-CR-3.JPG
BEGIN DESCRIPTION:
Beaumont Heights 2 Bridge
END DESCRIPTION:
Node Name=BF3-CR-3
Bridge Culvert--1,0,-1,-1, 0
Deck Dist Width WeirC Skew NumUp NumDn MinLoCord MaxHiCord MaxSubmerge Is_Ogee
1.3,3.6,1.4,0, 100, 100, , , 0.98, 0, 3,3,,
      -1   -.018    .964   1.946   2.928    3.91   4.892   5.873   6.855   7.837
   8.819   9.801  10.783  11.765  12.747  13.729  14.711  15.693  16.675  17.657
  18.638   19.62  20.602  21.584  22.566  23.548   24.53  25.512  26.494  27.476
  28.458   29.44  30.422  31.404  32.386  33.368   34.35  35.332  36.314  37.296
  38.278   39.26  40.242  41.224  42.206  43.188   44.17  45.152  46.134  47.116
  48.098  49.016  49.933  50.851  51.769  52.687  53.605  54.522   55.44  56.358
  57.276  58.193  59.111  60.106  61.101  62.095   63.09  64.085  65.079  66.074
  67.069  68.063  69.058  70.053  71.047  72.042  73.037  74.031  75.026  76.021
  77.016   78.01  79.005      80  80.994  81.989  82.984  83.978  84.973  85.968
  86.962  87.957  88.952  89.946  90.941  91.936  92.931  93.925   94.92  95.915
  28.119  28.118  28.142  28.162  28.142  28.114  28.064  28.034  28.056  28.106
   28.07  27.997  27.924  27.852  27.813  27.805  27.801  27.791  27.779  27.768
  27.758   27.75  27.738  27.698  27.663  27.627  27.593  27.551  27.516  27.469
   27.43  27.397  27.331  27.312  27.272  27.215  27.168  27.154   27.16  27.155
  27.136  27.114  27.095  27.069  27.036  27.044  27.089  27.155  27.185   27.22
  27.238  27.206  27.165  27.161  27.157  27.154   27.15  27.146  27.142  27.138
  27.135  27.131  27.127  27.182  27.161  27.139  27.117  27.102  27.062  27.014
  26.955   26.91  26.851  26.876  26.791  26.773  26.748  26.791  26.843  26.874
  26.971   27.18  27.253  27.174  27.157  27.232  27.365  27.525  27.725  27.924
  28.124  28.281  28.314  28.304  28.223  28.335   28.68  29.068  29.725  30.229
                  26.935 26.9312 26.9274 26.9236 26.9198  26.916 26.9122 26.9084
 26.9046 26.9008  26.897
      -7  -6.018  -5.036  -4.054  -3.072   -2.09  -1.108   -.127    .855   1.837
   2.819   3.801   4.783   5.765   6.747   7.729   8.711   9.693  10.675  11.657
  12.638   13.62  14.602  15.584  16.566  17.548   18.53  19.512  20.494  21.476
  22.458   23.44  24.422  25.404  26.386  27.368   28.35  29.332  30.314  31.296
  32.278   33.26  34.242  35.224  36.206  37.188   38.17  39.152  40.134  41.116
  42.098  43.016  43.933  44.851  45.769  46.687  47.605  48.522   49.44  50.358
  51.276  52.193  53.111  54.106  55.101  56.095   57.09  58.085  59.079  60.074
  61.069  62.063  63.058  64.053  65.047  66.042  67.037  68.031  69.026  70.021
  71.016   72.01  73.005      74  74.994  75.989  76.984  77.978  78.973  79.968
  80.962  81.957  82.952  83.946  84.941  85.936  86.931  87.925   88.92  89.915
  28.119  28.118  28.142  28.162  28.142  28.114  28.064  28.034  28.056  28.106
   28.07  27.997  27.924  27.852  27.813  27.805  27.801  27.791  27.779  27.768
  27.758   27.75  27.738  27.698  27.663  27.627  27.593  27.551  27.516  27.469
   27.43  27.397  27.331  27.312  27.272  27.215  27.168  27.154   27.16  27.155
  27.136  27.114  27.095  27.069  27.036  27.044  27.089  27.155  27.185   27.22
  27.238  27.206  27.179  27.178  27.176  27.175  27.173  27.172   27.17  27.169
  27.167  27.166  27.164  27.182  27.161  27.139  27.117  27.102  27.062  27.014
  26.955   26.91  26.851  26.876  26.791  26.773  26.748  26.791  26.843  26.874
  26.971   27.18  27.253  27.174  27.157  27.232  27.365  27.525  27.725  27.924
  28.124  28.281  28.314  28.304  28.223  28.335   28.68  29.068  29.725  30.229
                  26.949  26.948  26.946  26.945  26.943  26.942   26.94  26.939
  26.937  26.936  26.934
BR Coef=-1 , 0 , 0 ,, 0 ,,,0.8,-1,,0,
WSPro=,,,, 1 ,,,, 0 ,,,, 0 ,,,,-1 ,-1 ,-1 , 0 , 0 , 0 , 0 , 0
BC Design=,, 0 ,, 0 ,,,,,,
BC Use User HTab Curves=0
BC User HTab FreeFlow(D)= 0

Type RM Length L Ch R = 1 ,0.6889  ,7.8,6.97,6.29
BEGIN DESCRIPTION:
DS of Beaumont Heights 2 Bridge - BF3_20 (SEM 2019)
END DESCRIPTION:
XS GIS Cut Line= 4
609352.4699035995429515.07548309609321.0374035985429493.80298309
609302.6223035995429486.65918309609268.1735035985429480.46798309
#Sta/Elev= 30
       0   28.22       2    28.2    7.99   27.69   24.97   27.41   28.97   27.03
   38.17   26.77   42.34   26.89   43.53   26.83   44.35   26.44   44.95   26.05
   45.42   25.97   45.86   25.59   46.37   25.45   46.75   25.07   47.34   24.81
   49.47   24.56   50.53   25.03   51.08   25.68   51.86   26.12   52.67   26.25
   57.43   26.22   62.57   26.53   71.32   26.39   73.26   26.59   75.21   26.36
   78.12   27.13   82.98    27.3   86.87   27.67   88.82   28.27   92.71   30.12
#Mann= 3 , 0 , 0
       0     .06       0   44.35     .04       0   52.67     .06       0
Bank Sta=44.35,52.67
XS Rating Curve= 0 ,0
Exp/Cntr=0.3,0.1

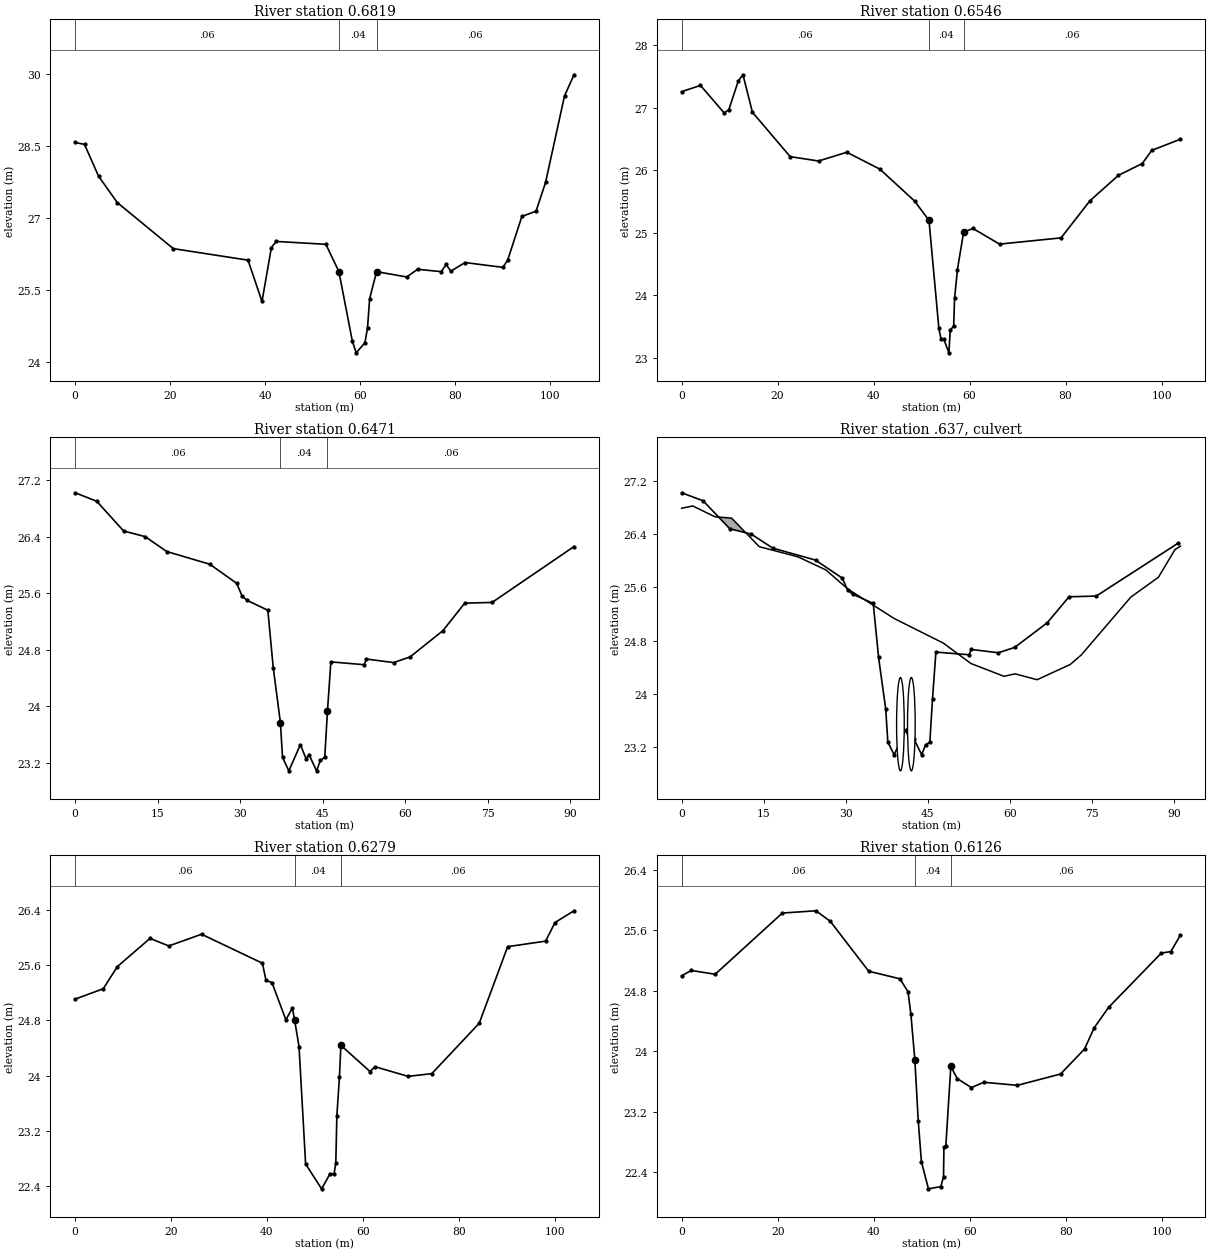
Type RM Length L Ch R = 1 ,0.6819  ,27.42,27.33,26.89
BEGIN DESCRIPTION:
BF3_19 (SEM 2019)
END DESCRIPTION:
XS GIS Cut Line= 4
609372.9487035985429483.64298309609322.7836035985429485.23048309
609303.2573035985429481.10298309609268.4910035985429477.61038309
#Sta/Elev= 30
       0   28.58    1.97   28.54    4.92   27.88    8.86   27.33   20.67   26.37
   36.41   26.13   39.36   25.27   41.33   26.39   42.32   26.52   52.82   26.46
   55.56   25.89    58.4   24.44    59.2    24.2   61.04   24.41   61.59   24.72
   62.04   25.33    63.5   25.89   69.86   25.78   72.14   25.94   77.14   25.89
   78.13   26.04   79.13    25.9   82.13   26.08   90.11   25.98   91.11   26.13
   94.11   27.04    97.1   27.15    99.1   27.75  103.09   29.55  105.09   29.99
#Mann= 3 , 0 , 0
       0     .06       0   55.56     .04       0    63.5     .06       0
Bank Sta=55.56,63.5
XS Rating Curve= 0 ,0
Exp/Cntr=0.3,0.1

Type RM Length L Ch R = 1 ,0.6546  ,7.95,7.49,7.08
BEGIN DESCRIPTION:
BF3_18 (SEM 2019)
END DESCRIPTION:
XS GIS Cut Line= 4
609369.6679035985429462.05288309609325.6411035985429457.60788309
609302.9927035985429454.43288309609266.3743035985429458.24288309
#Sta/Elev= 30
       0   27.26    3.93   27.36    8.85   26.92    9.83   26.97    11.8   27.43
   12.78   27.53   14.75   26.93   22.62   26.22   28.52   26.15   34.42   26.29
    41.3   26.02   48.53   25.51   51.54    25.2    53.6   23.47   54.06    23.3
   54.62    23.3   55.69   23.08   55.96   23.44   56.68   23.51   56.87   23.95
   57.46   24.41   58.75   25.01   60.71   25.07   66.24   24.82   79.06   24.92
   85.03   25.51      91   25.92   95.98   26.11   97.97   26.32  103.94    26.5
#Mann= 3 , 0 , 0
       0     .06       0   51.54     .04       0   58.75     .06       0
Bank Sta=51.54,58.75
XS Rating Curve= 0 ,0
Exp/Cntr=0.3,0.1

Type RM Length L Ch R = 1 ,0.6471  ,20.03,19.2,18.7
BEGIN DESCRIPTION:
US of Beaumont Heights 1 Culvert - BF3_17 (SEM 2019)
END DESCRIPTION:
XS GIS Cut Line= 4
609355.2745035985429444.48448309609325.2178035985429448.71788309
609303.6277035985429448.08288309609264.8927035985429448.92958309
#Sta/Elev= 30
       0   27.02    3.92    26.9    8.81   26.48   12.73    26.4   16.65   26.19
   24.48   26.01   29.37   25.74   30.35   25.56   31.24    25.5   35.03   25.36
   36.01   24.55   37.32   23.77    37.7   23.28   38.85   23.09   40.95   23.46
   41.99   23.26   42.51   23.32   43.89   23.09    44.6   23.24   45.38   23.28
   45.87   23.93   46.49   24.63   52.56   24.59   52.95   24.67   57.91   24.62
   60.89    24.7   66.85   25.07   70.83   25.46    75.8   25.47    90.7   26.26
#Mann= 3 , 0 , 0
       0     .06       0   37.32     .04       0   45.87     .06       0
Bank Sta=37.32,45.87
XS Rating Curve= 0 ,0
Exp/Cntr=0.3,0.1

Type RM Length L Ch R = 2 ,.637    ,,,
Node Photo=.\Photos\BF3-CR-2.JPG
BEGIN DESCRIPTION:
Beaumont Heights 1 Culvert
END DESCRIPTION:
Node Name=BF3-CR-2
Bridge Culvert--1,0,-1,-1, 0
Deck Dist Width WeirC Skew NumUp NumDn MinLoCord MaxHiCord MaxSubmerge Is_Ogee
3.4,6,1.4,0, 20, 20, , , 0.98, 0, 3,3,,
       02.0279486.0838459.12576814.1956421.2934626.3633330.4192338.8704747.86369
52.9034258.9510960.9669864.9987671.0464373.0623282.1338387.17355 90.197491.20534
 26.7874 26.8226 26.6601 26.6402 26.2116  26.058 25.8632 25.5739 25.1335 24.7637
 24.4583 24.2665 24.3037 24.2157 24.4444 24.5865 25.4555 25.7523 26.1677 26.2191
       06.95670713.91341 19.876323.8515727.82683 32.795937.7649845.6742455.19978
61.9401865.8954571.8283777.7612883.6941988.6382893.5823796.54883102.4817103.4706
 25.9956 26.4988 26.5477 26.3144 26.0435 26.0649 25.9275  25.585 25.1522 24.7281
 24.3459  24.233 24.1687 24.4128 24.9294 25.4607 25.7631 26.2621 26.5739 26.9365
BR Coef=-1 , 0 , 0 ,, 0 ,,,0.8,-1,,0,
WSPro=,,,, 1 ,,,, 0 ,,,, 0 ,,,,-1 ,-1 ,-1 , 0 , 0 , 0 , 0 , 0
Multiple Barrel Culv=1,1.4,,12.2,0.024,0.5,1,2,1,22.8485,22.7815, 2,Culvert #1  , 0 ,3.4
      40      50      42      52
BC Culvert Barrel=1,Barrel 1,0
BC Culvert Barrel=2,Barrel 2,0
Culvert Bottom n=0.024
BC Design=,, 0 ,, 0 ,,,,,,
BC Use User HTab Curves=0
BC User HTab FreeFlow(D)= 0

Type RM Length L Ch R = 1 ,0.6279  ,14.96,15.3,15.51
BEGIN DESCRIPTION:
DS of Beaumont Heights 1 Culvert - BF3_16 (SEM 2019)
END DESCRIPTION:
XS GIS Cut Line= 4
609362.7702035985429423.89738309609323.8764035985429427.46918309
609299.6670035985429431.04108309609259.1856035985429433.02548309
#Sta/Elev= 30
       0   25.11    5.86   25.26    8.79   25.58   15.62   25.99   19.53   25.88
   26.36   26.05   39.06   25.63   39.81   25.38   41.05   25.35   43.95   24.81
   45.31   24.98   45.77   24.81    46.7   24.42   48.07   22.72   51.41   22.36
   53.18   22.58      54   22.57   54.37   22.74   54.59   23.42   55.13   23.98
   55.43   24.44   61.51   24.06   62.55   24.13   69.46   23.99    74.4   24.03
   84.29   24.76   90.22   25.87   98.13   25.95   100.1   26.22  104.06   26.39
#Mann= 3 , 0 , 0
       0     .06       0   45.77     .04       0   55.43     .06       0
Bank Sta=45.77,55.43
XS Rating Curve= 0 ,0
Exp/Cntr=0.3,0.1

Type RM Length L Ch R = 1 ,0.6126  ,59.58,55.6,51.65
BEGIN DESCRIPTION:
BF3_15 (SEM 2019)
END DESCRIPTION:
XS GIS Cut Line= 2
609363.3179035985429410.19448309609259.8126035985429417.60278309
#Sta/Elev= 30
       0      25       2   25.07    6.98   25.02   20.95   25.83   27.94   25.86
   30.93   25.72   38.91   25.06   45.39   24.96   47.09   24.79   47.69   24.49
   48.51   23.89   49.22   23.08   49.88   22.54   51.34   22.18   53.92   22.21
   54.48   22.34   54.56   22.73   54.96   22.75      56    23.8   57.32   23.64
   60.27   23.52   62.86   23.59   69.85   23.55   78.83    23.7   83.81   24.03
   85.81   24.31    88.8   24.58   99.78    25.3  101.77   25.32  103.77   25.54
#Mann= 3 , 0 , 0
       0     .06       0   48.51     .04       0      56     .06       0
Bank Sta=48.51,56
XS Rating Curve= 0 ,0
Exp/Cntr=0.3,0.1

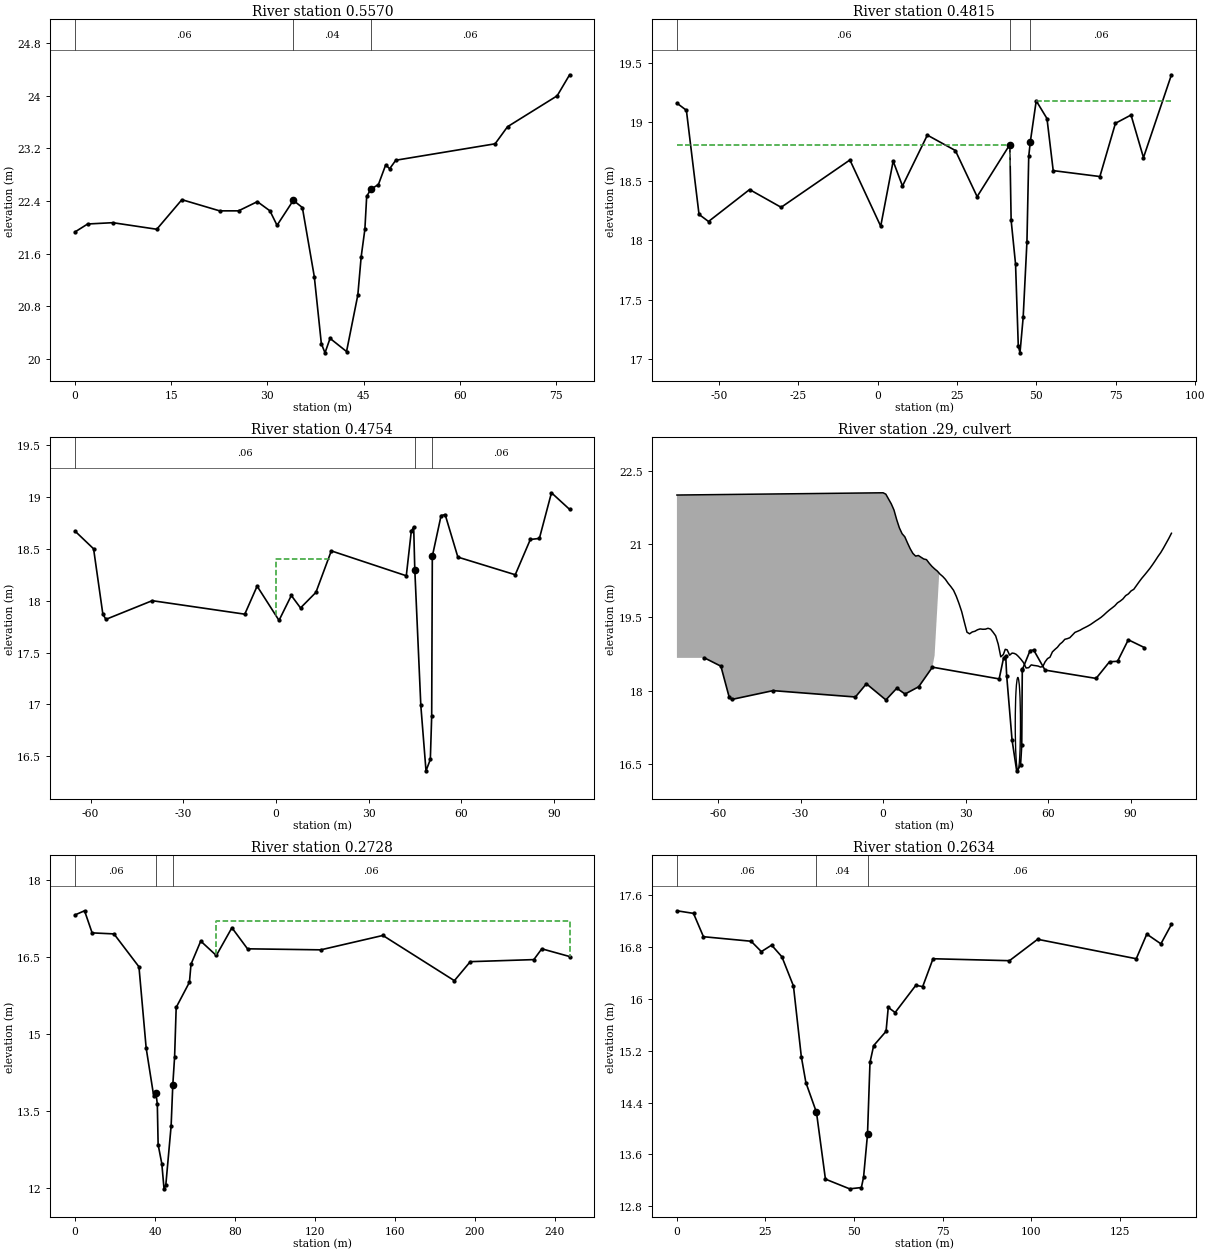
Type RM Length L Ch R = 1 ,0.5570  ,68.29,75.5,80.33
BEGIN DESCRIPTION:
BF3_14 (SEM 2019)
END DESCRIPTION:
XS GIS Cut Line= 4
609316.3278035985429336.95768309609294.5261035985429358.12438309
609282.8844035985429371.45938309609261.9293035995429391.56778309
#Sta/Elev= 30
       0   21.93    1.96   22.05    5.88   22.07   12.74   21.97   16.66   22.42
   22.54   22.25   25.49   22.25   28.43   22.39   30.39   22.25    31.5   22.03
   34.04   22.41   35.45    22.3   37.31   21.25   38.41   20.23   38.98   20.09
   39.77   20.31   42.34   20.11    44.1   20.97   44.62   21.55    45.2   21.97
   45.48   22.47   46.14   22.58   47.31   22.65   48.45   22.95   49.06   22.89
   50.02   23.02   65.51   23.27   67.45   23.53   75.19      24   77.13   24.32
#Mann= 3 , 0 , 0
       0     .06       0   34.04     .04       0   46.14     .06       0
Bank Sta=34.04,46.14
XS Rating Curve= 0 ,0
Exp/Cntr=0.3,0.1

Type RM Length L Ch R = 1 ,0.4815  ,5.74,6.07,6.34
BEGIN DESCRIPTION:
BF3_13 (SEM 2019)
END DESCRIPTION:
XS GIS Cut Line= 6
  609391.0522036 5429345.7792831  609335.1938036 5429310.3147831
  609304.0511036 5429296.1058831  609288.3877036 5429292.2958831
  609257.0610036 5429290.6025831  609252.1926036 5429296.7408831
#Sta/Elev= 30
   -63.2   19.16  -60.22    19.1  -56.24   18.22  -53.25   18.16  -40.32   18.43
  -30.38   18.28   -8.72   18.68     .98   18.12     4.9   18.67    7.84   18.46
   15.67   18.89   24.49   18.76   31.35   18.37   41.65   18.81   42.06   18.17
   43.45    17.8   44.31   17.11   44.85   17.05   45.85   17.35   47.04   17.99
    47.6   18.71   48.08   18.83   49.96   19.18   53.35   19.03   55.31   18.59
   70.01   18.54   74.91   18.99   79.82   19.06   83.74    18.7   92.55    19.4
#Mann= 3 , 0 , 0
   -63.2     .06       0   41.65     .04       0   48.08     .06       0
#XS Ineff= 2 , 0
           41.77   18.81   49.95           19.18
Permanent Ineff=
       F       F
Bank Sta=41.65,48.08
XS Rating Curve= 0 ,0
Exp/Cntr=0.3,0.1

Type RM Length L Ch R = 1 ,0.4754  ,190,190,190
BEGIN DESCRIPTION:
US of BF3 Stream Main St Culvert - BF3_12 (SEM 2019)
END DESCRIPTION:
XS GIS Cut Line= 5
  609397.3361036 5429341.8105831  609338.7169036 5429305.6136831
  609303.8394036 5429290.3908831  609289.4460036 5429285.7341831
  609251.3460036 5429285.0991831
#Sta/Elev= 30
     -65   18.67  -59.01    18.5  -56.01   17.87  -55.02   17.82  -40.04      18
  -10.08   17.87   -6.09   18.14       1   17.81    4.98   18.05    7.96   17.93
   12.94   18.08   17.92   18.48   42.19   18.24   43.81   18.67   44.58   18.71
   44.94    18.3   46.89   16.99   48.57   16.36   49.97   16.47   50.41   16.89
   50.61   18.44   50.63   18.43   53.45   18.82   54.76   18.83   58.88   18.42
   77.45   18.25   82.33   18.59   85.26    18.6   89.17   19.04   95.04   18.88
#Mann= 3 , 0 , 0
     -65     .06       0   44.94     .04       0   50.63     .06       0
#XS Ineff= 2 , 0
       0    17.8    18.4               0
Permanent Ineff=
       F       F
Bank Sta=44.94,50.63
XS Rating Curve= 0 ,0
Exp/Cntr=0.3,0.1

Type RM Length L Ch R = 2 ,.29     ,,,
Node Photo=.\Photos\BF3-CR-1.JPG
BEGIN DESCRIPTION:
BF3 Stream Main St Culvert
END DESCRIPTION:
Node Name=BF3-CR-1
Bridge Culvert--1,0,-1,-1, 0
Deck Dist Width WeirC Skew NumUp NumDn MinLoCord MaxHiCord MaxSubmerge Is_Ogee
2.25,186,1.4,0, 113, 114, , , 0.98, 0, 3,3,,
     -75       0    .985    1.97   2.955   3.941   4.926   5.911   6.896   7.881
   8.866   9.851  10.836  11.822  12.807  13.792  14.777  15.762  16.747  17.732
  18.717  19.703  20.688  21.673  22.658  23.643  24.628  25.613  26.599  27.584
  28.569  29.529  30.489  31.449  32.409  33.369   34.33   35.29   36.25   37.21
  38.139  39.068  39.997  40.926  41.856  42.785  43.714  44.411  45.109      46
   46.89   47.64  48.389  49.139    50.1  51.062  51.998  52.934   53.87  54.709
  55.548  56.387  57.226  58.065  58.904  59.793  60.681   61.57  62.473  63.376
  64.279  65.182  66.086  66.989  67.892  68.826   69.76  70.694  71.629  72.563
  73.497  74.432  75.366    76.3  77.292  78.285  79.277  80.269  81.261  82.253
  83.245  84.238   85.23  86.222  87.214  88.206  89.199  90.177  91.156  92.135
  93.114  94.092  95.071   96.05  97.029  98.008  98.986  99.965 100.944 101.923
 102.902  103.88 104.859
      22  22.046  22.017  21.918   21.82  21.694  21.497  21.328  21.209  21.146
   21.02  20.901  20.805  20.751  20.764  20.727  20.692  20.679  20.606  20.542
   20.49  20.445  20.382  20.335  20.275  20.195  20.127  20.051   19.93  19.782
  19.616  19.402  19.195  19.162    19.2  19.214  19.245  19.262  19.255  19.257
  19.275  19.258  19.194  19.121   18.95  18.691  18.738  18.845  18.834  18.725
  18.768  18.762  18.742  18.702  18.642  18.572  18.463  18.469  18.527  18.516
   18.51  18.502  18.482  18.492  18.589  18.655  18.684  18.793  18.842  18.886
   18.95  18.992   19.05  19.063  19.082  19.136  19.191  19.213  19.236  19.267
  19.293   19.32   19.35  19.386  19.425  19.461    19.5  19.547  19.599  19.647
   19.69  19.734  19.795  19.831  19.875  19.943  19.978  20.039  20.072  20.149
  20.226  20.299  20.364  20.432  20.501  20.578  20.659  20.744  20.821  20.913
  21.012  21.111  21.218
      -1       0    .985    1.97   2.955   3.941   4.926   5.911   6.896   7.881
   8.866   9.851  10.836  11.822  12.807  13.792  14.777  15.762  16.747  17.732
  18.717  19.703  20.688  21.673  22.658  23.643  24.628  25.613  26.599  27.584
  28.569  29.529  30.489  31.449  32.409  33.369   34.33   35.29   36.25   37.21
  38.139  39.068  39.997  40.926  41.856  42.785  43.714  44.411  45.109      46
   46.89   47.64  48.389  49.139    50.1  51.062  51.998  52.934   53.87  54.709
  55.548  56.387  57.226  58.065  58.904  59.793  60.681   61.57  62.473  63.376
  64.279  65.182  66.086  66.989  67.892  68.826   69.76  70.694  71.629  72.563
  73.497  74.432  75.366    76.3  77.292  78.285  79.277  80.269  81.261  82.253
  83.245  84.238   85.23  86.222  87.214  88.206  89.199  90.177  91.156  92.135
  93.114  94.092  95.071   96.05  97.029  98.008  98.986  99.965 100.944 101.923
 102.902  103.88 104.859     250
      22  22.046  22.017  21.918   21.82  21.694  21.497  21.328  21.209  21.146
   21.02  20.901  20.805  20.751  20.764  20.727  20.692  20.679  20.606  20.542
   20.49  20.445  20.382  20.335  20.275  20.195  20.127  20.051   19.93  19.782
  19.616  19.402  19.195  19.162    19.2  19.214  19.245  19.262  19.255  19.257
  19.275  19.258  19.194  19.121   18.95  18.691  18.738  18.845  18.834  18.725
  18.768  18.762  18.742  18.702  18.642  18.572  18.463  18.469  18.527  18.516
   18.51  18.502  18.482  18.492  18.589  18.655  18.684  18.793  18.842  18.886
   18.95  18.992   19.05  19.063  19.082  19.136  19.191  19.213  19.236  19.267
  19.293   19.32   19.35  19.386  19.425  19.461    19.5  19.547  19.599  19.647
   19.69  19.734  19.795  19.831  19.875  19.943  19.978  20.039  20.072  20.149
  20.226  20.299  20.364  20.432  20.501  20.578  20.659  20.744  20.821  20.913
  21.012  21.111  21.218      21
BR Coef=-1 , 0 , 0 ,, 0 ,,,0.8,-1,,0,
WSPro=,,,, 1 ,,,, 0 ,,,, 0 ,,,,-1 ,-1 ,-1 , 0 , 0 , 0 , 0 , 0
Culvert=1,1.9,,186.4,0.024,0.5,1,2,1,16.369,49,12.359,44.5,Culvert #1  , 0 ,1.35
      49    44.5
BC Culvert Barrel=1,Barrel 1,0
Culvert Bottom n=0.024
BC Design=,, 0 ,, 0 ,,,,,,
BC Use User HTab Curves=0
BC User HTab FreeFlow(D)= 0

Type RM Length L Ch R = 1 ,0.2728  ,8.36,9.45,10.66
BEGIN DESCRIPTION:
DS of BF3 Stream Main St Culvert - BF3_01B (SEM 2019)
END DESCRIPTION:
XS GIS Cut Line= 6
  609394.5006036 5429172.2269831  609399.8648036 5429147.3850831
  609399.8648036 5429114.8412831  609385.3465036 5429085.0599831
  609381.2180036 5429052.3200831  609258.4420036 5429062.4999831
#Sta/Elev= 30
       0   17.32    4.73    17.4    8.52   16.97   19.45   16.95   31.95   16.31
   35.55   14.73   39.35   13.79   40.42   13.86   41.13   13.64   41.54   12.85
   43.38   12.48   44.49   11.99   45.37   12.06   48.03   13.21   48.87   14.01
   49.78   14.56   50.57   15.52    57.2   16.01   57.98   16.36   62.85   16.81
   70.64   16.53   78.44   17.07   86.24   16.66  122.89   16.64  153.95   16.92
  189.71   16.04  197.66   16.41  229.45   16.45  233.43   16.66  247.34   16.51
#Mann= 3 , 0 , 0
       0     .06       0   40.42     .04       0   48.87     .06       0
#XS Ineff= 2 , 0
       0                    70.6       0    17.2
Permanent Ineff=
       F       F
Bank Sta=40.42,48.87
XS Rating Curve= 0 ,0
Exp/Cntr=0.3,0.1

Type RM Length L Ch R = 1 ,0.2634  ,65.29,59.94,55.45
BEGIN DESCRIPTION:
BF3_01A (SEM 2019)
END DESCRIPTION:
XS GIS Cut Line= 6
609396.6437035995429172.70328309609401.2948035985429164.58178309
609406.6117035985429141.03508309609412.9617035995429113.65068309
609417.4998035985429089.75048309609382.0784035995429049.39388309
#Sta/Elev= 30
       0   17.36    4.68   17.32    7.49   16.96   20.95   16.89   23.84   16.73
   26.74   16.83   29.64   16.65    32.9    16.2   35.12   15.11   36.41   14.71
    39.4   14.25   41.93   13.22   48.76   13.07   52.08   13.09    52.7   13.25
   53.81   13.91   54.51   15.02   55.55   15.28   59.05    15.5   59.67   15.87
   61.61   15.79   67.45   16.21   69.39   16.19   72.31   16.62   93.89   16.59
  101.85   16.92  129.69   16.62  132.67      17  136.65   16.85  139.63   17.15
#Mann= 3 , 0 , 0
       0     .06       0    39.4     .04       0   53.81     .06       0
Bank Sta=39.4,53.81
XS Rating Curve= 0 ,0
Exp/Cntr=0.3,0.1

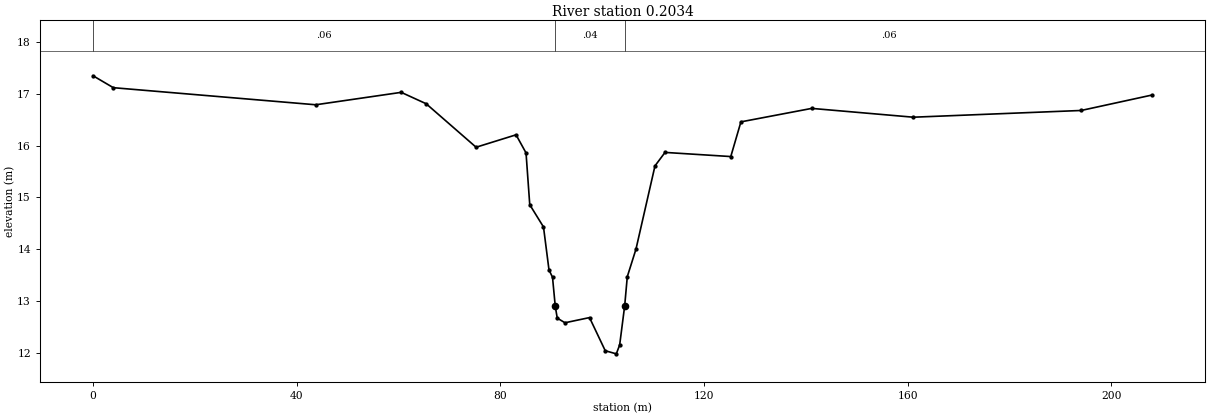
Type RM Length L Ch R = 1 ,0.2034  ,56.15,203.43,53.26
BEGIN DESCRIPTION:
BF3_01 (SEM 2019)
END DESCRIPTION:
XS GIS Cut Line= 6
609472.0766035985429205.26028309609481.8287035985429153.48868309
609472.8900035985429122.38188309609458.2056035995429100.55368309
609432.4096035995429072.96628309609380.0014035985429045.92788309
#Sta/Elev= 30
       0   17.35    3.98   17.12   43.74   16.79   60.53   17.03   65.43   16.81
   75.24   15.97   83.09   16.21   85.05   15.86   85.78   14.86   88.48   14.43
   89.56    13.6   90.25   13.4690.78999    12.9   91.18   12.67    92.7   12.58
   97.52   12.68  100.61   12.04  102.78   11.98  103.44   12.15  104.43   12.91
  104.94   13.47  106.64      14  110.38   15.61  112.35   15.87  125.27   15.79
  127.26   16.46  141.17   16.72  161.12   16.55   194.1   16.68   208.1   16.98
#Mann= 3 , 0 , 0
       0     .06       090.78999     .04       0  104.43     .06       0
Bank Sta=90.78999,104.43
XS Rating Curve= 0 ,0
Exp/Cntr=0.3,0.1

River Reach=BF4             ,BF4
Reach XY= 30
606630.2213035985427389.92988309606642.9214035985427387.70728309
606666.7339035985427358.17978309606681.9739035985427344.52728309
606696.8965035985427328.96968309606704.5165035995427330.23968309
606714.6765035995427325.00098309606724.8365035985427329.60468309
606777.9848035985427347.99988309606840.2943035985427358.71558309
606865.6943035985427360.30308309606901.4132035985427364.66868309
606928.9960035985427364.47028309606945.6648035985427353.09318309
606960.7461035985427350.44728309606987.7337035985427339.33478309
607009.6941035995427341.71608309607035.0942035985427339.07018309
607042.5025035985427334.57228309607064.1984035985427306.79098309
607125.8464035985427234.55958309607138.5465035985427226.35748309
607148.8652035995427211.80538309607157.8611035985427212.59908309
607164.2111035995427211.27618309607171.8840035985427190.90328309
607178.2340035985427164.70948309607190.6695035985427149.89278309
607218.9800035985427122.11148309607343.2426745345426949.64970111

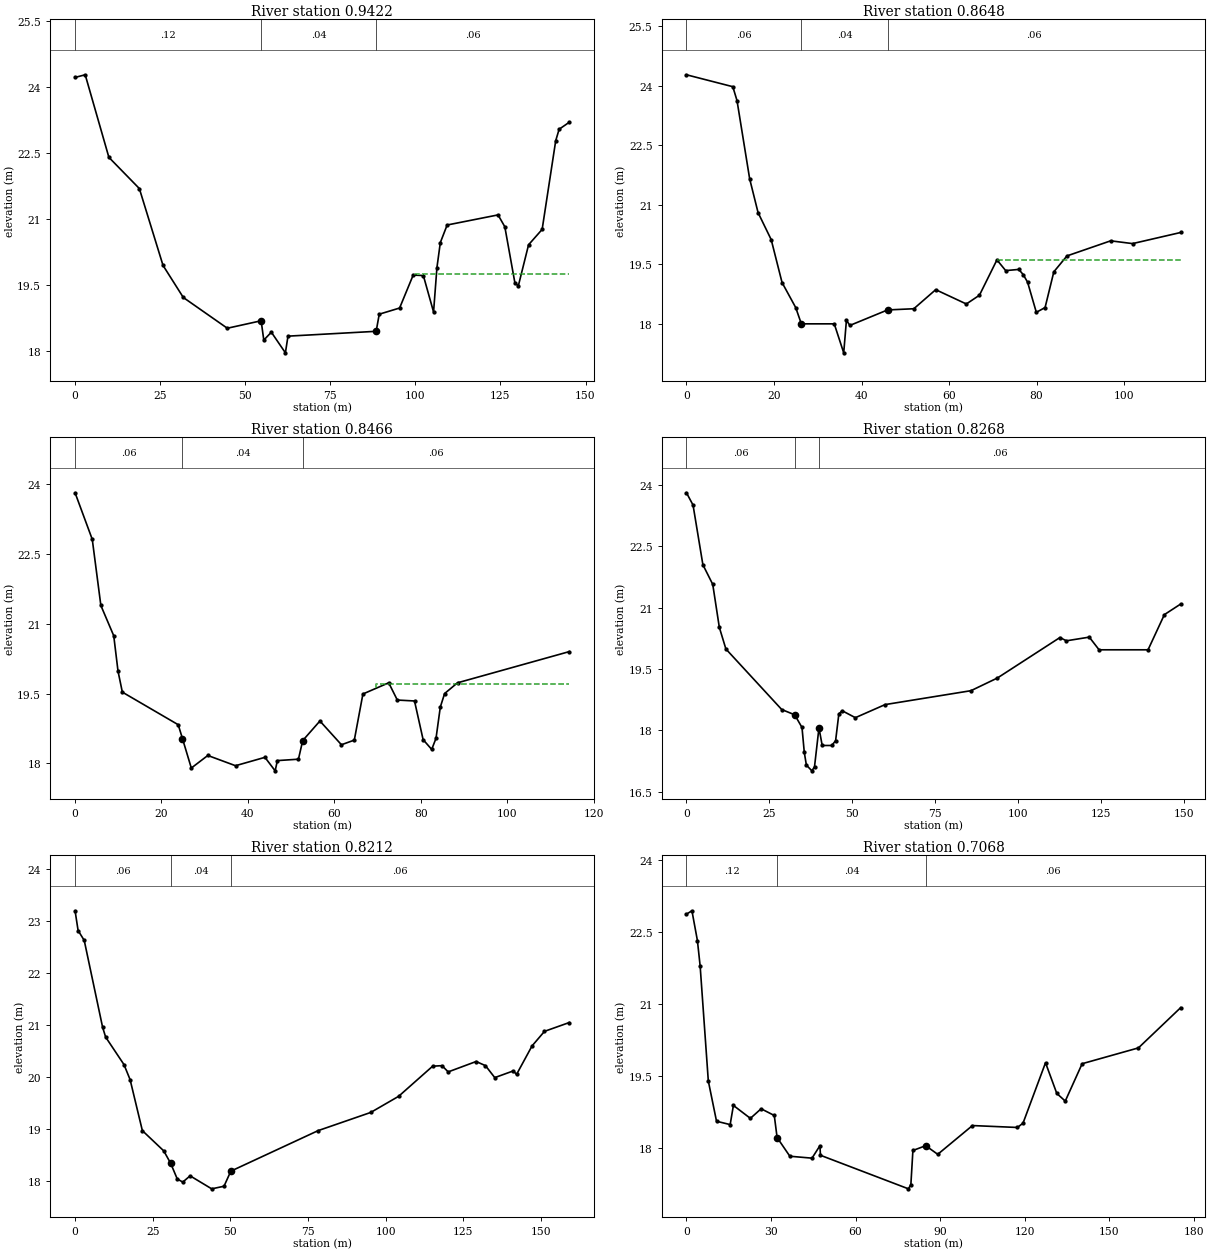
Type RM Length L Ch R = 1 ,0.9422  ,74.98,77.31,78.39
BEGIN DESCRIPTION:
BF4_19 (SEM 2019)
END DESCRIPTION:
XS GIS Cut Line= 5
606691.5097035985427420.70018309606643.0908035985427395.30018309
606638.5929035985427384.71678309606621.6595035985427368.84178309
606571.3886035985427344.50008309
#Sta/Elev= 30
       0   24.22    2.98   24.28    9.94    22.4   18.89   21.69   25.85   19.94
   31.81   19.21   44.74   18.51   54.68   18.68   55.46   18.24   57.68   18.42
   61.81   17.95   62.57   18.33   88.48   18.44   89.39   18.83   95.37   18.97
   99.36   19.72  102.35   19.71  105.35   18.88  106.34   19.89  107.34   20.46
  109.34   20.86   124.3   21.09  126.29   20.82  129.28   19.53  130.28   19.48
  133.27   20.41  137.26   20.76  141.25   22.78  142.25   23.04  145.24    23.2
#Mann= 3 , 0 , 0
       0     .12       0   54.68     .04       0   88.48     .06       0
#XS Ineff= 2 , 0
                           99.82           19.74
Permanent Ineff=
       F       F
Bank Sta=54.68,88.48
XS Rating Curve= 0 ,0
Exp/Cntr=0.3,0.1

Type RM Length L Ch R = 1 ,0.8648  ,19.17,18.24,16.76
BEGIN DESCRIPTION:
BF4_18 (SEM 2019)
END DESCRIPTION:
XS GIS Cut Line= 4
606699.9321035985427369.46978309606697.1539035985427350.41978309
606691.2008035985427325.41658309606676.1195035995427259.13828309
#Sta/Elev= 30
       0   24.27   10.59   23.97   11.55   23.62   14.44   21.65   16.36    20.8
   19.36   20.12   21.84   19.04   24.96   18.41   26.25      18   33.77      18
   35.93   17.27   36.55   18.09   37.34   17.96   45.95   18.35   51.95   18.38
   56.95   18.86   63.95    18.5   66.94   18.72   70.94   19.61   72.94   19.34
   75.94   19.37   76.94   19.24   77.94   19.05   79.94   18.29   81.94   18.41
   83.94   19.31   86.94   19.71   96.93   20.09  101.93   20.02  112.93    20.3
#Mann= 3 , 0 , 0
       0     .06       0   26.25     .04       0   45.95     .06       0
#XS Ineff= 2 , 0
                           71.07           19.61
Permanent Ineff=
       F       F
Bank Sta=26.25,45.95
XS Rating Curve= 0 ,0
Exp/Cntr=0.3,0.1

Type RM Length L Ch R = 1 ,0.8466  ,15.24,19.8,23.02
BEGIN DESCRIPTION:
BF4_17 (SEM 2019)
END DESCRIPTION:
XS GIS Cut Line= 4
606708.7076035985427360.90428309606715.8514035995427337.09168309
606699.7118035985427315.66038309606678.5451035985427256.65818309
#Sta/Elev= 30
       0   23.81    3.98   22.81    5.97   21.39    8.95   20.74    9.94   19.98
   10.94   19.53   23.87   18.83   24.86   18.53    26.9    17.9   30.72   18.17
   37.13   17.95   43.94   18.13    46.3   17.84   46.82   18.06   51.69   18.09
   52.68   18.49   56.66   18.91   61.64    18.4   64.62    18.5   66.61   19.49
   72.58   19.73   74.57   19.36   78.55   19.34   80.54   18.51   82.53    18.3
   83.53   18.54   84.52   19.21   85.52    19.5    88.5   19.73  114.37    20.4
#Mann= 3 , 0 , 0
       0     .06       0   24.86     .04       0   52.68     .06       0
#XS Ineff= 2 , 0
                           69.55           19.71
Permanent Ineff=
       F       F
Bank Sta=24.86,52.68
XS Rating Curve= 0 ,0
Exp/Cntr=0.3,0.1

Type RM Length L Ch R = 1 ,0.8268  ,6.37,5.62,5.09
BEGIN DESCRIPTION:
BF4_16 (SEM 2019)
END DESCRIPTION:
XS GIS Cut Line= 5
606711.0889035985427364.07928309606726.1701035985427331.79998309
606730.6681035985427322.53958309606727.1756035985427261.92018309
606711.6644035985427222.56138309
#Sta/Elev= 30
       0   23.81    1.98   23.51    4.95   22.05    7.92   21.57     9.9   20.52
   11.88   19.99    28.7   18.51   32.62   18.38   34.82   18.07   35.51   17.46
   36.14   17.15    37.8   17.01   38.59   17.11   39.93   18.06   40.91   17.63
   43.81   17.63   44.95   17.75   45.92    18.4   46.92   18.48    50.9   18.31
   59.86   18.63   85.74   18.97    93.7   19.28  112.55   20.27  114.51   20.19
   121.4   20.28  124.35   19.97  139.11   19.97  144.03   20.83  148.95   21.09
#Mann= 3 , 0 , 0
       0     .06       0   32.62     .04       0   39.93     .06       0
Bank Sta=32.62,39.93
XS Rating Curve= 0 ,0
Exp/Cntr=0.3,0.1

Type RM Length L Ch R = 1 ,0.8212  ,125.12,114.42,106.72
BEGIN DESCRIPTION:
BF4_15 (SEM 2019)
END DESCRIPTION:
XS GIS Cut Line= 6
606717.9680035985427368.57718309606729.3452035985427341.32508309
606734.3722035985427325.18538309606735.6952035995427315.39578309
606736.2067035995427258.60858309606712.9873035985427218.92338309
#Sta/Elev= 30
       0    23.2     .98   22.82    2.95   22.63    8.86   20.96    9.84   20.77
   15.75   20.24   17.72   19.95   21.66   18.97   28.55   18.58   30.78   18.34
   32.89   18.04   34.67   17.98   37.03    18.1   43.98   17.85   47.94    17.9
   50.13   18.19   78.23   18.97   95.17   19.32  104.14   19.63   115.1   20.21
   118.1   20.22   120.1    20.1   129.1    20.3   132.1   20.22  135.09   19.99
  141.09   20.12  142.09   20.05  147.09    20.6  151.09   20.88  159.08   21.05
#Mann= 3 , 0 , 0
       0     .06       0   30.78     .04       0   50.13     .06       0
Bank Sta=30.78,50.13
XS Rating Curve= 0 ,0
Exp/Cntr=0.3,0.1

Type RM Length L Ch R = 1 ,0.7068  ,96.89,91.23,93.89
BEGIN DESCRIPTION:
BF4_14 (SEM 2019)
END DESCRIPTION:
XS GIS Cut Line= 6
606834.9141035985427420.17108309606837.2954035985427401.91478309
606846.2912035985427373.33968309606839.4120035985427342.91258309
606838.6183035985427327.03748309606847.5943035995427247.69688309
#Sta/Elev= 30
       0   22.87    1.94   22.94    3.88   22.32    4.85   21.79    7.75   19.39
   10.66   18.55    15.5   18.48   16.65   18.88   22.67   18.61   26.48   18.81
   31.15   18.67   32.15   18.21   36.67   17.82   44.53   17.78   47.34   18.04
   47.53   17.84   78.74   17.14    79.6   17.23   80.32   17.94   84.86   18.04
   89.13   17.86  101.44   18.46  117.39   18.42  119.38   18.51  127.36   19.77
  131.36   19.13  134.36   18.97  140.35   19.75  160.32   20.08  175.31   20.92
#Mann= 3 , 0 , 0
       0     .12       0   32.15     .04       0   84.86     .06       0
Bank Sta=32.15,84.86
XS Rating Curve= 0 ,0
Exp/Cntr=0.3,0.1