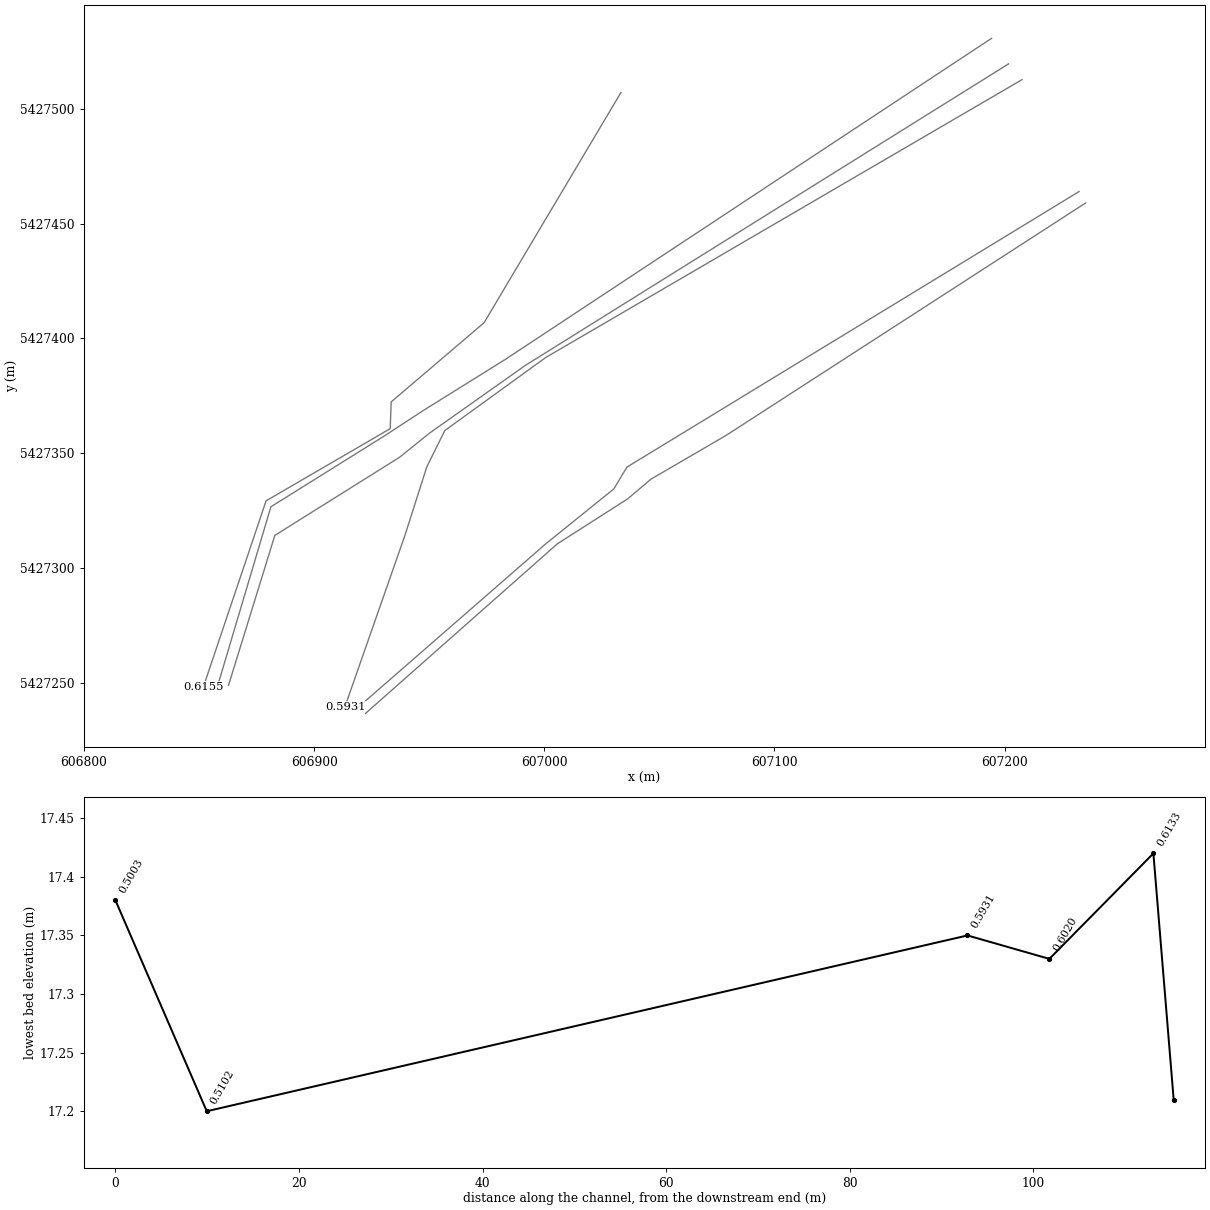
HEC-RAS study Exploits_FMM.prj: Exploits_FMM

--- Exploits_FMM.g01 (geometry) --- (continued)

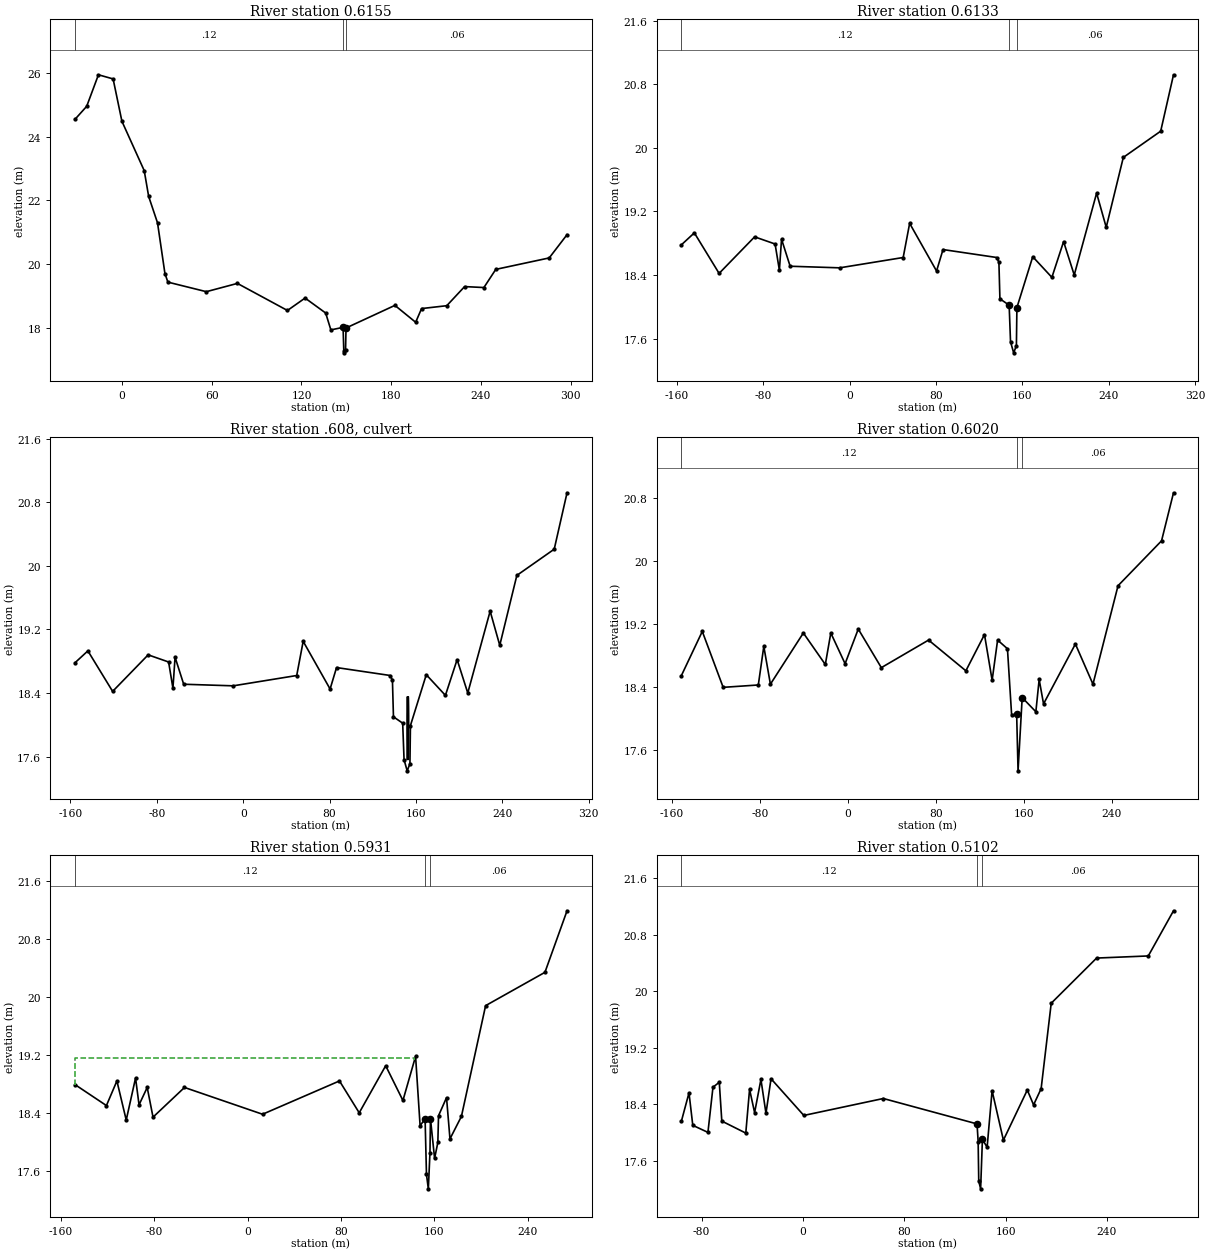
Type RM Length L Ch R = 1 ,0.6155  ,11.5,2.21,1.61
BEGIN DESCRIPTION:
BF4_13 (SEM 2019)
END DESCRIPTION:
XS GIS Cut Line= 6
     607033.3236     5427507.108     606973.8516    5427406.8734
     606933.4716     5427372.374     606933.0483    5427360.7323
     606879.1159    5427329.3056     606851.8938    5427248.3584
#Sta/Elev= 30
   -31.5   24.54  -23.65   24.95   -15.8   25.94   -5.98   25.81    -.09   24.48
   14.83   22.93    17.8   22.12   23.73   21.29   28.68    19.7   30.66   19.43
   56.37   19.13   77.14   19.39  110.62   18.54  122.42   18.93  136.19   18.46
  139.67   17.93  147.84   18.01  148.31   17.27  148.75   17.21   149.5   17.31
   149.8   17.99   182.5    18.7  196.38   18.17  200.34    18.6  217.19   18.69
  229.11   19.29  242.02   19.26  249.96   19.83  285.71   20.19  297.63   20.92
#Mann= 3 , 0 , 0
   -31.5     .12       0  147.84     .04       0   149.8     .06       0
Bank Sta=147.84,149.8
XS Rating Curve= 0 ,0
Exp/Cntr=0.3,0.1

Type RM Length L Ch R = 1 ,0.6133  ,10.44,11.33,11.94
BEGIN DESCRIPTION:
US of BF4 Stream Newfoundland T'Railway Culvert - BF4_12 (SEM 2019)
END DESCRIPTION:
XS GIS Cut Line= 6
     607194.3229     5427530.656     606983.1066    5427390.9105
     606947.6533    5427368.7756     606930.5083    5427357.5573
     606881.2153    5427326.7247     606857.8469    5427248.0276
#Sta/Elev= 30
 -155.84   18.78 -143.87   18.93 -120.94   18.42-88.0399   18.88  -69.09   18.79
   -65.1   18.46-63.1099   18.85  -55.13   18.51-9.26998   18.49   49.56   18.62
55.54001   19.05   80.47   18.45   86.45   18.72  136.23   18.62  138.22   18.56
  139.16    18.1  147.71   18.02  148.98   17.56  151.88   17.42  154.43   17.51
  154.89   17.99  169.56   18.63  187.29   18.37  198.13   18.82  207.99    18.4
  228.72   19.43  237.62      19  253.45   19.88  288.07   20.21  299.94   20.92
#Mann= 3 , 0 , 0
 -155.84     .12       0  147.71     .04       0  154.89     .06       0
Bank Sta=147.71,154.89
XS Rating Curve= 0 ,0
Exp/Cntr=0.3,0.1

Type RM Length L Ch R = 2 ,.608    ,,,
Node Photo=.\Photos\BF4-CR-3.JPG
BEGIN DESCRIPTION:
BF4 Stream Newfoundland T'Railway Culvert
END DESCRIPTION:
Node Name=BF4-CR-3
Bridge Culvert--1,0,-1,-1, 0
Deck Dist Width WeirC Skew NumUp NumDn MinLoCord MaxHiCord MaxSubmerge Is_Ogee
3,5,1.4,0, 466, 466, , , 0.98, 0, 3,3,,
    -151-150.005-149.011-148.017-147.022-146.028-145.034-144.039-143.045 -142.05
-141.056-140.062-139.067-138.073-137.079-136.084 -135.09-134.096-133.101-132.107
-131.113-130.118-129.124 -128.13-127.146-126.162-125.178-124.195-123.211-122.227
-121.243-120.259-119.276-118.292-117.308-116.324 -115.34-114.357-113.373-112.389
-111.405-110.421-109.438-108.454 -107.47-106.486-105.502-104.519-103.535-102.551
-101.567-100.583-99.6001-98.6163-97.6325-96.6487-95.6649-94.6814-93.6979-92.7143
-91.7308-90.7473-89.7638-88.7803-87.7968-86.8132-85.8297-84.8462-83.8627-82.8792
-81.8957-80.9121-79.9286-78.9451-77.9616-76.9781-75.9945 -75.011-74.0275 -73.044
-72.0605 -71.077-70.0934-69.1099-68.1264-67.1429-66.1594-65.1758-64.1923-63.2088
-62.2253-61.2418-60.2582-59.2649-58.2716-57.2782-56.2849-55.2915-54.2982-53.3048
-52.3115-51.3181-50.3248-49.3314-48.3381-47.3447-46.3514 -45.358-44.3647-43.3713
 -42.378-41.3846-40.3913-39.3979-38.4046-37.4112-36.4179-35.4245-34.4452-33.4659
-32.4866-31.5073 -30.528-29.5487-28.5694-27.5901-26.6108-25.6315-24.6522-23.6729
-22.6936-21.7143 -20.735-19.7557-18.7764 -17.797-16.8177-15.8384-14.8591-13.8798
-12.9005-11.9212-10.9419-9.96265-8.98334-8.00404-7.02473-6.04542-5.06612-4.08681
-3.10751 -2.1282 -1.1504-.172594.80521241.7830192.7608263.7386324.7164395.694245
6.6720527.6498588.6276669.60547210.5832811.5610812.53889 13.5167 14.494515.47231
16.4501217.4279318.4057319.3835420.3613421.3391522.3169623.2947624.2595525.22433
26.1891127.1538928.1186729.0834630.0482431.01302 31.977832.9425833.9073634.87215
35.8369336.8017137.7664938.7312839.6960640.6608441.62562 42.590443.5551944.51997
45.4847546.4495347.41431 48.379149.3438850.3086651.2958952.2831153.2703454.25756
55.2447956.2320257.2192458.20647 59.193760.1809261.1681562.15538 63.142664.12983
65.1170666.1042867.0915168.0787469.0659670.0531871.0404172.0276473.0148674.00209
74.9893275.9765576.96377  77.95178.9382279.9254580.9126781.8999682.8872483.87452
 84.861885.8490886.8363687.8236588.8109389.7982190.7854991.7727792.7600693.74734
94.73462 95.721996.7091897.6964698.6837599.67103100.6583101.6456102.6329103.6202
104.6074105.5947 106.582107.5693108.5256109.4818110.4381111.3944112.3506113.3069
114.2632115.2194116.1757 117.132118.0882119.0445120.0008 120.957121.9133122.8696
123.8258124.7821125.7384126.6946127.6509128.6406129.6303  130.62131.6097132.5994
133.5891134.5789135.5686136.5583 137.548138.5377139.5274140.5171141.5068142.4965
143.4862144.4759145.4656146.4553 147.445148.4347149.4245150.4142151.4039152.3936
153.3833 154.373155.3395156.3061157.2726158.2392159.2057160.1723161.1388162.1054
163.0719164.0385 165.005165.9715166.9381167.9046168.8712169.8377170.8317171.8256
172.8196173.8135174.8075175.8014176.7954177.7893178.7833179.7772180.7711181.7651
 182.759 183.753184.7469185.7409186.7348187.7288188.7227189.7167190.7106191.7046
192.6985193.6925194.6864195.6804196.6743197.6683198.6622199.6562200.6501201.6441
 202.638 203.632204.6259205.6199206.6138207.6078208.6017209.5957210.5537211.5118
212.4699 213.428214.3861215.3442216.3023217.2604218.2185219.1766220.1346221.0927
222.0508223.0089 223.967224.9251225.8231226.7211227.6192228.5172229.4152230.3132
 231.305232.2968233.2885234.2803235.2721236.2639237.2556238.2474239.2392240.2309
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    -155-154.005-153.011-152.017-151.022-150.028-149.034-148.039-147.045 -146.05
-145.056-144.062-143.067-142.073-141.079-140.084 -139.09-138.096-137.101-136.107
-135.113-134.118-133.124 -132.13-131.146-130.162-129.178-128.195-127.211-126.227
-125.243-124.259-123.276-122.292-121.308-120.324 -119.34-118.357-117.373-116.389
-115.405-114.421-113.438-112.454 -111.47-110.486-109.502-108.519-107.535-106.551
-105.567-104.583  -103.6-102.616-101.632-100.648-99.6649-98.6814-97.6979-96.7143
-95.7308-94.7473-93.7638-92.7803-91.7968-90.8132-89.8297-88.8462-87.8627-86.8792
-85.8957-84.9121-83.9286-82.9451-81.9616-80.9781-79.9945 -79.011-78.0275 -77.044
-76.0605 -75.077-74.0934-73.1099-72.1264-71.1429-70.1594-69.1758-68.1923-67.2088
-66.2253-65.2418-64.2582-63.2649-62.2716-61.2782-60.2849-59.2915-58.2982-57.3048
-56.3115-55.3181-54.3248-53.3314-52.3381-51.3447-50.3514 -49.358-48.3647-47.3713
 -46.378-45.3846-44.3913-43.3979-42.4046-41.4112-40.4179-39.4245-38.4452-37.4659
-36.4866-35.5073 -34.528-33.5487-32.5694-31.5901-30.6108-29.6315-28.6522-27.6729
-26.6936-25.7143 -24.735-23.7557-22.7764 -21.797-20.8177-19.8384-18.8591-17.8798
-16.9005-15.9212-14.9419-13.9626-12.9833 -12.004-11.0247-10.0454-9.06612-8.08681
-7.10751 -6.1282 -5.1504-4.17259-3.19478-2.21698-1.23917-.261367.71643871.694245
2.6720523.6498584.6276655.6054726.5832787.5610858.5388929.516698 10.494511.47231
12.4501213.4279214.4057315.3835416.3613417.3391518.3169619.2947620.2595521.22433
22.1891123.1538924.1186725.0834626.0482427.01302 27.977828.9425829.9073730.87215
31.8369332.8017133.7664934.7312835.6960636.6608437.62562 38.590439.5551940.51997
41.4847542.4495343.41431 44.379145.3438846.3086647.2958948.2831149.2703450.25756
51.2447952.2320253.2192454.20647 55.193756.1809257.1681558.15538 59.142660.12983
61.1170562.1042863.0915164.0787465.0659666.0531867.0404168.0276469.0148670.00209
70.9893271.9765572.96377  73.95174.9382275.9254576.9126777.8999678.8872479.87452
 80.861881.8490882.8363683.8236584.8109385.7982186.7854987.7727788.7600689.74734
90.73462 91.721992.7091893.6964694.6837595.6710396.6583197.6455998.6328799.62016
100.6074101.5947 102.582103.5693104.5256105.4818106.4381107.3944108.3506109.3069
110.2632111.2194112.1757 113.132114.0882115.0445116.0008 116.957117.9133118.8696
119.8258120.7821121.7384122.6946123.6509124.6406125.6303  126.62127.6097128.5994
129.5891130.5789131.5686132.5583 133.548134.5377135.5274136.5171137.5068138.4965
139.4862140.4759141.4656142.4553 143.445144.4347145.4245146.4142147.4039148.3936
149.3833 150.373151.3395152.3061153.2726154.2392155.2057156.1723157.1388158.1054
159.0719160.0385 161.005161.9715162.9381163.9046164.8712165.8377166.8317167.8256
168.8196169.8135170.8075171.8014172.7954173.7893174.7833175.7772176.7711177.7651
 178.759 179.753180.7469181.7409182.7348183.7288184.7227185.7167186.7106187.7046
188.6985189.6925190.6864191.6804192.6743193.6683194.6622195.6562196.6501197.6441
 198.638 199.632200.6259201.6199202.6138203.6078204.6017205.5957206.5537207.5118
208.4699 209.428210.3861211.3442212.3023213.2604214.2185215.1766216.1346217.0927
218.0508219.0089 219.967220.9251221.8231222.7211223.6192224.5172225.4152226.3132
 227.305228.2968229.2885230.2803231.2721232.2639233.2556234.2474235.2392236.2309
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BR Coef=-1 , 0 , 0 ,, 0 ,,,0.8,-1,,0,
WSPro=,,,, 1 ,,,, 0 ,,,, 0 ,,,,-1 ,-1 ,-1 , 0 , 0 , 0 , 0 , 0
Multiple Barrel Culv=1,0.8,,7.6,0.011,0.9,1,2,3,17.5555,17.534, 2,Culvert #1  , 0 ,1.9
     152  154.75     153  155.75
BC Culvert Barrel=1,Barrel 1,0
BC Culvert Barrel=2,Barrel 2,0
Culvert Bottom n=0.011
BC Design=,, 0 ,, 0 ,,,,,,
BC Use User HTab Curves=0
BC User HTab FreeFlow(D)= 0

Type RM Length L Ch R = 1 ,0.6020  ,6.48,8.92,10.51
BEGIN DESCRIPTION:
DS of BF4 Stream Newfoundland T'Railway Culvert - BF4_11 (SEM 2019)
END DESCRIPTION:
XS GIS Cut Line= 6
     607201.7313    5427519.5434     606991.6194    5427388.1708
     606950.1933    5427358.8273     606937.0699    5427348.2439
     606882.9225    5427314.2691     606862.8079    5427249.0198
#Sta/Elev= 30
  -151.3   18.54 -132.32    19.1 -113.33   18.39  -81.36   18.42  -76.36   18.91
  -70.36   18.43  -40.39   19.08   -20.4   18.68  -15.41   19.08-2.41999   18.69
9.569992   19.13   30.55   18.64   73.52   18.99  107.45    18.6  124.38   19.06
  131.34   18.48  136.32   18.99  145.28   18.88  149.07   18.04  153.65   18.05
  154.92   17.33  158.68   18.26  171.12   18.08  174.12   18.49  178.11   18.18
  207.08   18.94  223.06   18.43  245.87   19.68  285.45   20.25  296.33   20.86
#Mann= 3 , 0 , 0
  -151.3     .12       0  153.65     .04       0  158.68     .06       0
Bank Sta=153.65,158.68
XS Rating Curve= 0 ,0
Exp/Cntr=0.3,0.1

Type RM Length L Ch R = 1 ,0.5931  ,81.97,82.87,82.61
BEGIN DESCRIPTION:
BF4_10 (SEM 2019)
END DESCRIPTION:
XS GIS Cut Line= 6
     607207.5521    5427512.6643     607000.6162    5427391.7105
      606956.755    5427359.8856     606948.9233    5427344.0106
     606939.3937    5427314.1139     606913.4095    5427239.7594
#Sta/Elev= 30
 -148.09   18.79 -121.12    18.5 -112.14   18.84 -104.15    18.3  -96.16   18.88
  -93.16   18.51  -86.17   18.75-81.1799   18.34  -54.21   18.75    12.7   18.38
78.62001   18.8495.54001    18.4  118.23   19.05  133.01   18.57  143.85   19.18
  147.73   18.22     152   18.32  153.18   17.55  154.78   17.35  156.18   17.85
   156.6   18.32  160.14   17.77  162.93   17.99  163.52   18.36  170.38   18.61
  173.32   18.04  183.13   18.35  203.87   19.88  254.72   20.34  273.66   21.19
#Mann= 3 , 0 , 0
 -148.09     .12       0     152     .04       0   156.6     .06       0
#XS Ineff= 2 , 0
          142.88   19.15
Permanent Ineff=
       F       F
Bank Sta=152,156.6
XS Rating Curve= 0 ,0
Exp/Cntr=0.3,0.1

Type RM Length L Ch R = 1 ,0.5102  ,11.49,9.95,8.78
BEGIN DESCRIPTION:
BF4_09 (SEM 2019)
END DESCRIPTION:
XS GIS Cut Line= 5
     607232.3701    5427463.9632     607035.9185    5427344.0106
     607030.2035    5427334.4856     607000.8548    5427310.7809
     606918.3705    5427238.7672
#Sta/Elev= 30
     -96   18.16  -90.02   18.56  -87.03    18.1  -75.07      18  -71.09   18.64
  -66.11   18.71  -64.11   18.16  -45.18   17.99  -42.19   18.61  -38.21   18.28
  -33.22   18.75  -29.24   18.27  -25.25   18.76.6500015   18.2463.42999   18.48
  137.43   18.12   138.3   17.87  138.77   17.31  140.26    17.2  141.67    17.9
  145.39   17.79  149.31   18.59  158.24   17.89  177.11    18.6  182.07   18.39
  188.04   18.62     196   19.83  231.84   20.47  272.65    20.5  292.56   21.14
#Mann= 3 , 0 , 0
     -96     .12       0  137.43     .04       0  141.67     .06       0
Bank Sta=137.43,141.67
XS Rating Curve= 0 ,0
Exp/Cntr=0.3,0.1

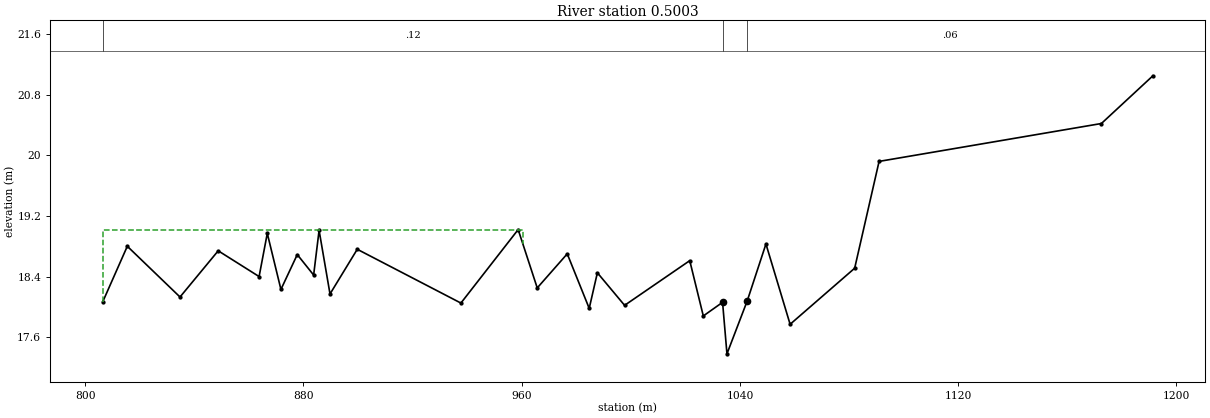
Type RM Length L Ch R = 1 ,0.5003  ,13.99,13.06,12.4
BEGIN DESCRIPTION:
US of BF4 Stream Exploits Valley and Beothuk Trail Culvert - BF4_08 (SEM 2019)
END DESCRIPTION:
XS GIS Cut Line= 6
     607235.2163    5427458.9906     607078.9477    5427357.7692
     607046.2902    5427338.7189     607036.3418    5427330.2522
     607005.6542    5427310.5807     606922.3393    5427236.7828
#Sta/Elev= 30
   806.5   18.07  815.46    18.8  834.78   18.13  848.78   18.74  863.77    18.4
  866.77   18.97  871.77   18.23  877.76   18.69  883.76   18.42  885.76   19.01
  889.76   18.17  899.75   18.76  937.74   18.05  958.73   19.02  965.72   18.25
  976.72    18.7  984.77   17.98  987.76   18.45  997.74   18.02 1021.62   18.61
 1026.59   17.88 1033.65   18.06 1035.26   17.38  1042.7   18.08 1049.55   18.83
 1058.41   17.77 1082.07   18.51 1091.02   19.92 1172.51   20.42 1191.39   21.05
#Mann= 3 , 0 , 0
   806.5     .12       0 1033.65     .04       0  1042.7     .06       0
#XS Ineff= 2 , 0
          960.45   19.02
Permanent Ineff=
       F       F
Bank Sta=1033.65,1042.7
XS Rating Curve= 0 ,0
Exp/Cntr=0.3,0.1