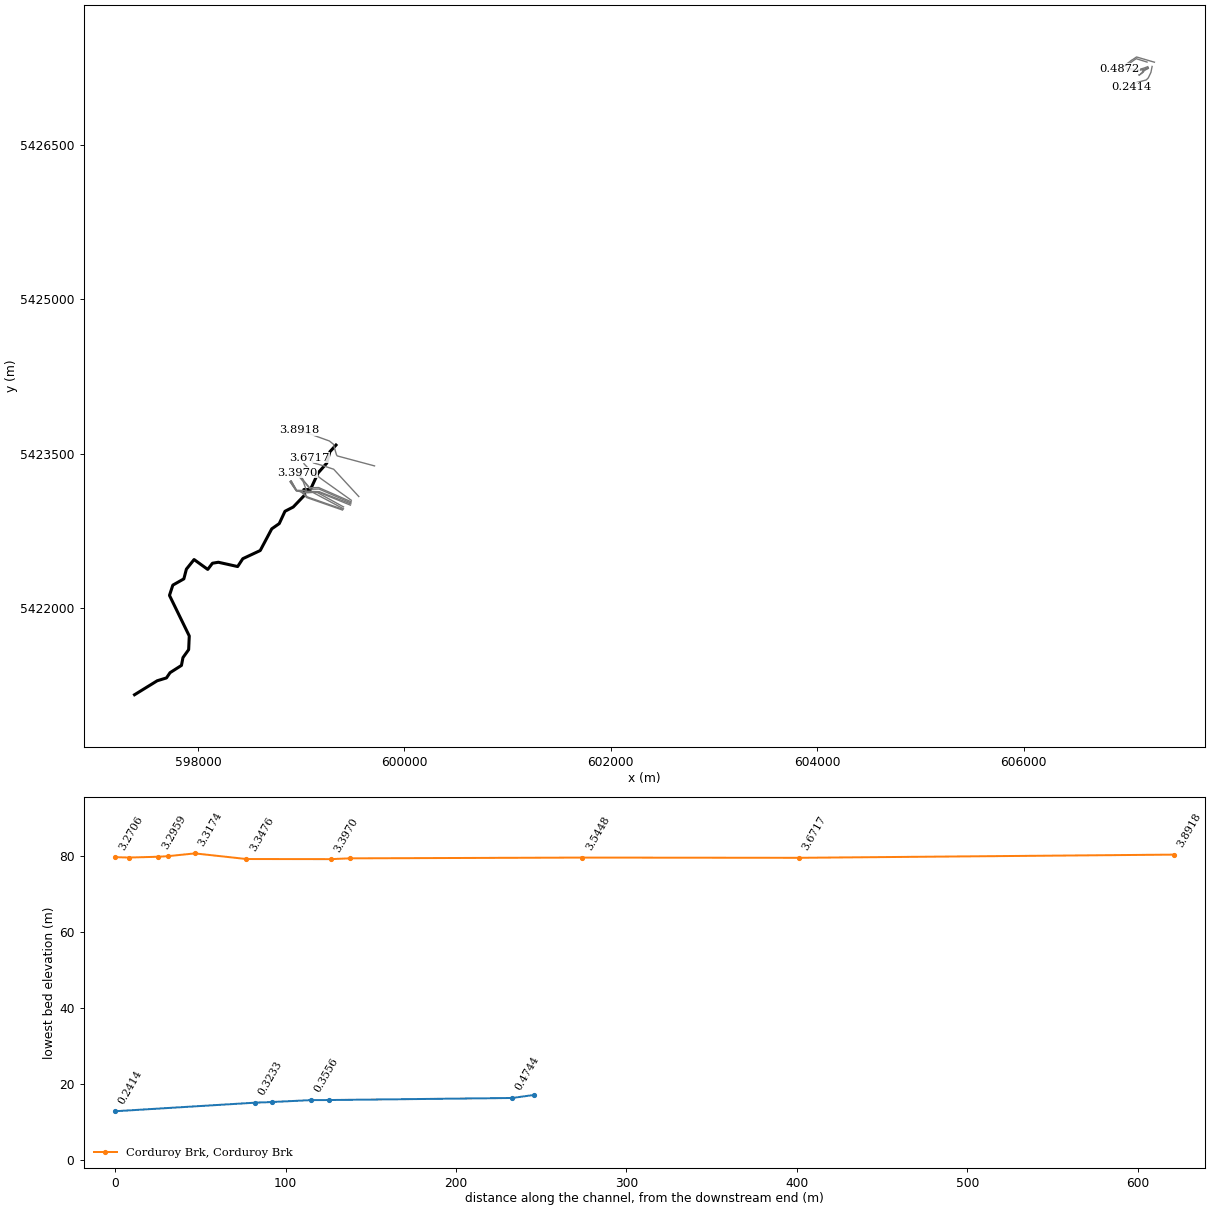
HEC-RAS study Exploits_FMM.prj: Exploits_FMM

--- Exploits_FMM.g01 (geometry) --- (continued)

Type RM Length L Ch R = 2 ,.494    ,,,
Node Photo=.\Photos\BF4-CR-2.JPG
BEGIN DESCRIPTION:
Exploits Valley and Beothuk Trail Culvert
END DESCRIPTION:
Node Name=BF4-CR-2
Bridge Culvert--1,0,-1,-1, 0
Deck Dist Width WeirC Skew NumUp NumDn MinLoCord MaxHiCord MaxSubmerge Is_Ogee
4,2,1.4,0, 400, 400, , , 0.98, 0, 3,3,,
       0 7.99772 19.994322.9934427.9920232.9905935.9897437.9891738.9888840.98832
42.98774 46.986651.9851852.9848961.9823363.9817668.9803370.9797772.9791976.97806
78.9774983.9760687.97492 92.973594.9729297.97207103.9405113.8779116.8592117.8529
118.8467119.8404123.8154128.7841131.7653137.7278138.7215 140.709141.7028143.6903
 144.684145.6777147.6652149.6527153.6277155.6152157.6027161.5777162.5714164.5589
166.5464167.5401170.5213171.5151174.4963176.4838177.4776180.4588182.4463184.4338
186.4213188.4088  191.39194.3712199.3399203.3149209.2774213.2523221.2023 234.121
241.0772245.0522 252.018255.0064265.9641266.9602 271.941279.9102280.9063284.8909
288.8755299.8332301.8255303.8178306.8062307.8024 311.787316.7677  318.76319.7562
321.7485325.7331327.7254329.7177  331.71333.7023334.6984336.6907337.6869340.6753
341.6714343.6638344.6599346.6522349.6407 351.633354.6214357.6099359.6021362.5906
366.5752368.5675371.5559372.5521373.5482377.5329379.5251382.5136383.5098 385.502
388.4905389.4867390.4828392.4751393.4713396.4597399.4482401.4405402.4366407.4174
410.4092413.4079416.4065417.4061418.4056419.4052421.4043423.4034425.4025428.4012
430.4003432.3994 435.398437.3972438.3967440.3958442.3949 444.394447.3927449.3918
451.3909  453.39455.3891456.3887460.3869461.3864466.3842470.3824472.3815474.3806
478.3788481.3775483.3766485.3757490.3735492.3726494.3717496.3708498.3699501.3686
503.3677504.3672505.3668507.3659510.3646514.3628515.3623517.3615519.3605521.3596
525.3578526.3574529.3561531.3552533.3543535.3534 536.353538.3521540.3511541.3507
543.3498545.3489551.3463558.3431559.3427560.3422563.3409566.3395567.3391570.3378
573.3342 574.333578.3283582.3236583.3224586.3188589.3153591.3129593.3106594.3094
595.3082596.3071598.3047600.3023603.2988605.2964607.2941609.2917610.2905614.2858
617.2822618.2811620.2787622.2763625.2728627.2704631.2657632.2645636.2598638.2574
642.2527644.2504649.2444652.2409654.2385658.2338661.2303663.2279666.2244669.2208
672.2173676.2125677.2114678.2102680.2078682.2054686.2007687.1995689.1972 690.196
692.1937697.1627698.1552701.1328703.1179 705.103706.0956708.0807710.0658711.0583
713.0434716.0211717.0136718.9987720.9838722.9689726.9391727.9316729.9167731.9018
734.8795737.8571739.8422741.8273  746.79748.7751751.7527752.7453 755.723757.7081
 766.641770.6112771.6037774.5814779.5441785.4994787.4845789.4696793.4398799.3951
803.3652 808.328812.2982815.2923818.2864821.2805825.2726828.2668830.2629 833.257
835.2531838.2472845.2334849.2256853.2177855.2138857.2099863.1981868.1883871.1824
874.1765883.1589 886.153 888.149890.1451893.1392895.1353900.1255906.1137910.1059
915.0961917.0922923.0804928.0706929.0686933.0607934.0588935.0568 938.051 940.047
942.0431946.0352950.0274956.0156959.0097961.0058962.0038964.9979969.9882971.9842
975.9764976.9744979.9685980.9666983.9607987.9528989.9489 992.943996.93521000.927
1004.9191011.8911018.8261019.8171027.7421032.6961036.6591042.6031043.5931049.538
 1052.51  1053.51057.4631058.4541063.407 1066.381070.3421072.3241074.3051080.249
 1081.241088.1841090.1741094.1541101.1191104.1041110.0741116.044 1119.031125.995
 1130.971141.9151144.9011145.8961150.8711157.8361160.8211168.7111173.6271176.577
1182.4761186.4091190.3421194.2751199.1911204.108 1210.991212.9571214.923 1219.84
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    -842-834.002-822.005-819.006-814.008-809.009 -806.01 -804.01-803.011-801.011
-799.012-795.013-790.014-789.015-780.017-778.018-773.019 -771.02 -769.02-765.021
-763.022-758.023-754.025-749.026-747.027-744.028-738.059-728.122 -725.14-724.147
-723.153-722.159-718.184-713.215-710.234-704.272-703.278-701.291-700.297-698.309
-697.316-696.322-694.334-692.347-688.372-686.384-684.397-680.422-679.428-677.441
-675.453-674.459-671.478-670.484-667.503-665.516-664.522-661.541-659.553-657.566
-655.578-653.591 -650.61-647.628 -642.66-638.685-632.722-628.747-620.797-607.879
-600.922-596.947-589.982-586.993-576.035-575.039-570.059-562.089-561.093-557.109
-553.124-542.166-540.174-538.182-535.193-534.197-530.213-525.232 -523.24-522.243
-520.251-516.266-514.274-512.282 -510.29-508.297-507.301-505.309-504.313-501.324
-500.328-498.336 -497.34-495.347-492.359-490.367-487.378 -484.39-482.397-479.409
-475.424-473.432-470.444-469.447-468.451-464.467-462.474-459.486 -458.49-456.498
-453.509-452.513-451.517-449.524-448.528 -445.54-442.551-440.559-439.563-434.582
 -431.59-428.592-425.593-424.593-423.594-422.594-420.595-418.596-416.597-413.598
-411.599  -409.6-406.602-404.602-403.603-401.604-399.605-397.606-394.607-392.608
-390.609 -388.61 -386.61-385.611-381.613-380.613-375.615-371.617-369.618-367.619
-363.621-360.622-358.623-356.624-351.626-349.627-347.628-345.629 -343.63-340.631
-338.632-337.632-336.633-334.634-331.635-327.637-326.637-324.638-322.639 -320.64
-316.642-315.642-312.643-310.644-308.645-306.646-305.647-303.647-301.648-300.649
 -298.65-296.651-290.653-283.656-282.657-281.657-278.659 -275.66 -274.66-271.662
-268.665-267.667-263.671-259.676-258.677-255.681-252.684-250.687-248.689 -247.69
-246.691-245.692-243.695-241.697-238.701-236.703-234.705-232.708-231.709-227.714
-224.717-223.718-221.721-219.723-216.727-214.729-210.734-209.735 -205.74-203.742
-199.747-197.749-192.755-189.759-187.761-183.766-180.769-178.772-175.775-172.779
-169.782-165.787-164.788-163.789-161.792-159.794-155.799  -154.8-152.802-151.804
-149.806-144.837-143.844-140.867-138.882-136.897-135.904-133.919-131.934-130.941
-128.956-125.978-124.986-123.001-121.016-119.031 -115.06-114.068-112.083-110.098
 -107.12-104.142-102.157-100.172  -95.21-93.2249-90.2473-89.2547 -86.277-84.2919
 -75.359-71.3888-70.3963-67.4186-62.4559-56.5006-54.5155-52.5304-48.5602-42.6049
-38.6348 -33.672-29.7018-26.7077-23.7136-20.7195-16.7274-13.7332-11.7371  -8.743
 -6.7469 -3.7528  3.2334  7.2256 11.2177 13.2138 15.2099 21.1981 26.1883 29.1824
 32.1765 41.1589  44.153  46.149 48.1451 51.1392 53.1353 58.1255 64.1137 68.1059
 73.0961 75.0922 81.0804 86.0706 87.0686 91.0607 92.0588 93.0568  96.051  98.047
100.0431104.0352108.0274114.0156117.0097119.0058120.0038122.9979127.9882129.9842
133.9764134.9744137.9685138.9666141.9607145.9528147.9489 150.943154.9352 158.927
 162.919 169.891 176.826 177.817 185.742 190.696 194.659 200.603 201.593 207.538
  210.51   211.5 215.463 216.454 221.407  224.38 228.342 230.324 232.305 238.249
  239.24 246.184 248.174 252.154 259.119 262.104 268.074 274.044  277.03 283.995
  288.97 299.915 302.901 303.896 308.871 315.836 318.821 326.711 331.627 334.577
 340.476 344.409 348.342 352.275 357.191 362.108  368.99 370.957 372.923  377.84
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BR Coef=-1 , 0 , 0 ,, 0 ,,,0.8,-1,,0,
WSPro=,,,, 1 ,,,, 0 ,,,, 0 ,,,,-1 ,-1 ,-1 , 0 , 0 , 0 , 0 , 0
Multiple Barrel Culv=1,0.9,,9.2,0.024,0.9,1,2,3,17.463,17.449, 2,Culvert #1  , 0 ,2.7
  1035.5   191.5  1036.5   192.5
BC Culvert Barrel=1,Barrel 1,0
BC Culvert Barrel=2,Barrel 2,0
Culvert Bottom n=0.024
BC Design=,, 0 ,, 0 ,,,,,,
BC Use User HTab Curves=0
BC User HTab FreeFlow(D)= 0

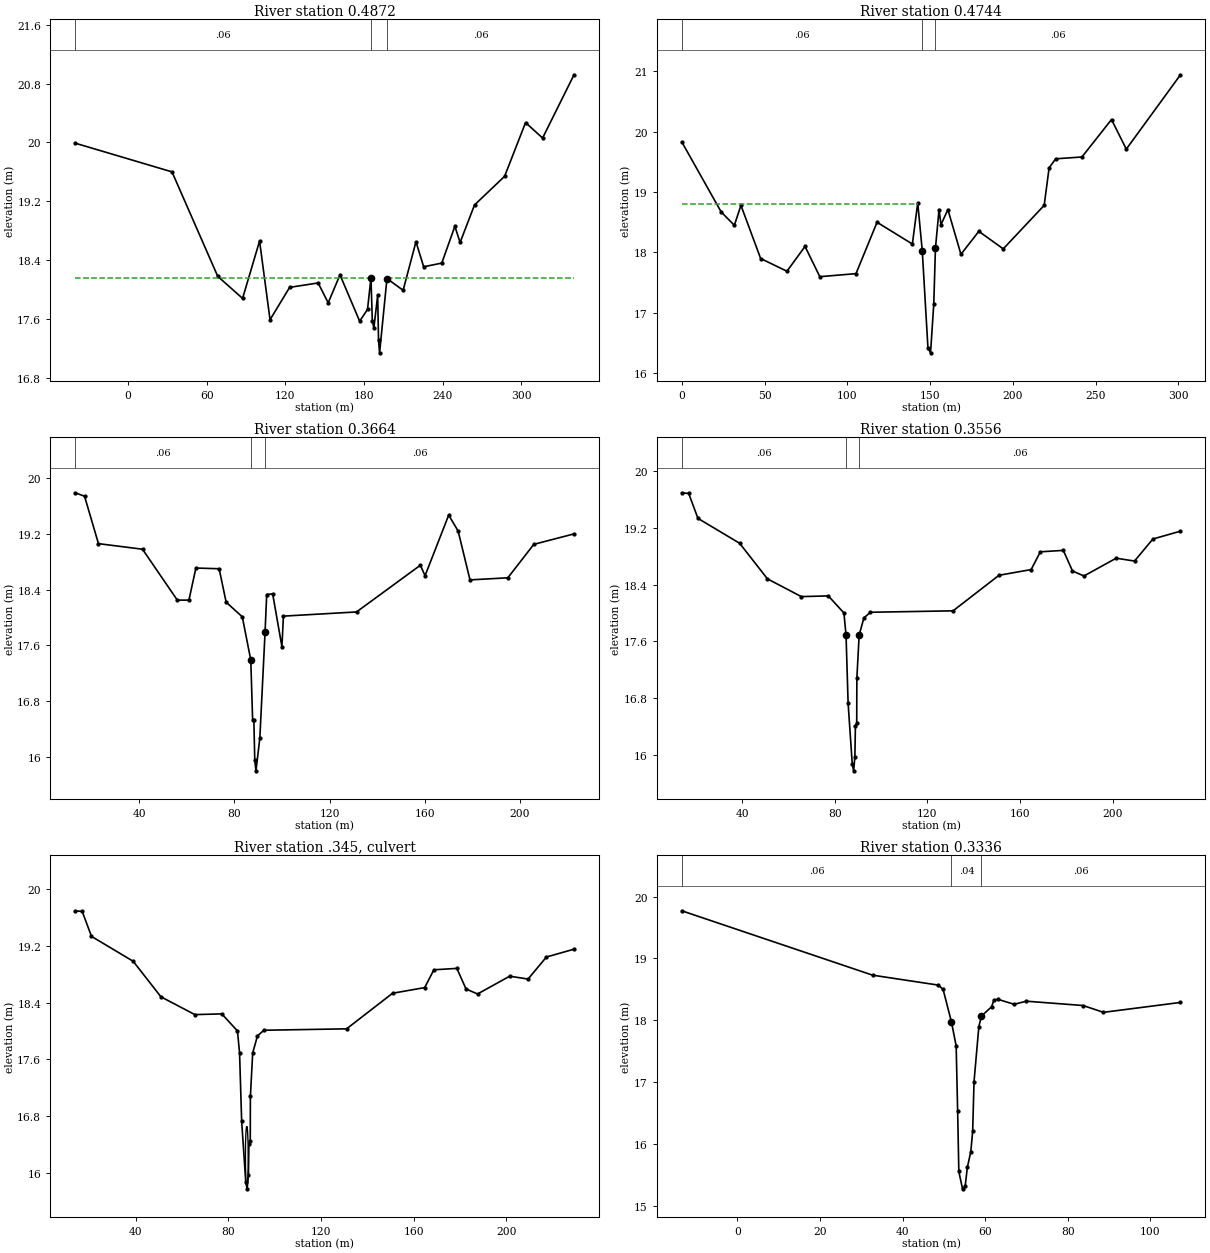
Type RM Length L Ch R = 1 ,0.4872  ,12.05,12.82,13.35
BEGIN DESCRIPTION:
DS of BF4 Stream Exploits Valley and Beothuk Trail Culvert - BF4_07 (SEM 2019)
END DESCRIPTION:
XS GIS Cut Line= 6
     607266.3474    5427302.3045     607093.2177     5427353.171
     607057.5085    5427328.7706     607044.8085    5427321.9972
     607015.9892    5427298.4002     606928.8968    5427239.9959
#Sta/Elev= 30
   -40.3   19.9933.46002    19.668.35999   18.1887.29999   17.88  100.26   18.66
  108.24   17.59  123.19   18.03  144.92   18.09   152.6   17.82   161.6    18.2
   176.6   17.57  182.59   17.73  185.23   18.16  186.26   17.57  187.46   17.48
  190.34   17.92     191   17.31  191.79   17.14  197.43   18.15  209.75   17.99
  219.55   18.65  225.43   18.31  239.23   18.36  249.22   18.86  253.21   18.64
   264.2   19.15  287.17   19.54  303.14   20.27  316.13   20.06   340.1   20.92
#Mann= 3 , 0 , 0
   -40.3     .06       0  185.23     .04       0  197.43     .06       0
#XS Ineff= 2 , 0
          185.18   18.16  198.13           18.16
Permanent Ineff=
       F       F
Bank Sta=185.23,197.43
XS Rating Curve= 0 ,0
Exp/Cntr=0.3,0.1

Type RM Length L Ch R = 1 ,0.4744  ,108.08,107.43,106.24
BEGIN DESCRIPTION:
BF4_06 (SEM 2019)
END DESCRIPTION:
XS GIS Cut Line= 6
607195.1343035995427303.49598309607089.9376035985427336.44608309
607063.2235035985427318.82218309607050.1002035985427308.66218309
607015.5792035985427280.96748309606928.2353035985427236.02708309
#Sta/Elev= 30
       0   19.83   23.83   18.67   31.78   18.45   35.75   18.78   47.67    17.9
   63.56   17.69   74.48    18.1   83.42    17.6  105.27   17.65  117.99    18.5
  139.33   18.14  142.57   18.82  145.31   18.03  148.75   16.42  150.31   16.34
  152.27   17.15  153.27   18.07  155.45   18.71  156.61   18.46   160.8   18.71
  168.67   17.97  179.49   18.35  194.24   18.06  218.97   18.78  221.95    19.4
  225.91   19.55  241.79   19.58  259.65    20.2  268.58   19.71  301.32   20.94
#Mann= 3 , 0 , 0
       0     .06       0  145.31     .04       0  153.27     .06       0
#XS Ineff= 2 , 0
          142.64    18.8  155.53           18.69
Permanent Ineff=
       F       F
Bank Sta=145.31,153.27
XS Rating Curve= 0 ,0
Exp/Cntr=0.3,0.1

Type RM Length L Ch R = 1 ,0.3664  ,12.4,10.77,10.13
BEGIN DESCRIPTION:
BF4_05 (SEM 2019)
END DESCRIPTION:
XS GIS Cut Line= 6
      607201.072    5427258.6979     607164.5594    5427244.9396
     607137.3073     5427237.002      607117.622     5427229.287
     607088.8885    5427231.4458     606997.3424    5427244.9396
#Sta/Elev= 30
      13   19.79    16.9   19.74   22.75   19.06   41.29   18.98   55.93   18.25
   60.83   18.25   63.76   18.71   73.55    18.776.49001   18.22   83.29   18.01
   86.86   17.39   87.64   16.53   88.15   16.53   88.54   15.95   89.04    15.8
   90.67   16.27   92.87   17.79   93.56   18.33   96.07   18.34   99.97   17.58
  100.59   18.02  131.36   18.08  158.22   18.75  160.21    18.6  170.16   19.47
  174.14   19.24  179.12   18.54  195.04   18.57  205.98   19.05   222.9    19.2
#Mann= 3 , 0 , 0
      13     .06       0   86.86     .04       0   92.87     .06       0
Bank Sta=86.86,92.87
XS Rating Curve= 0 ,0
Exp/Cntr=0.3,0.1

Type RM Length L Ch R = 1 ,0.3556  ,16.74,22.57,28.37
BEGIN DESCRIPTION:
US of BF4 Stream Main Street Culvert - BF4_04 (SEM 2019)
END DESCRIPTION:
XS GIS Cut Line= 6
     607205.3054    5427250.7604     607168.5282      5427235.15
     607130.9573    5427226.1541      607119.051     5427224.302
     607094.7093    5427222.1853     606995.2258    5427233.2979
#Sta/Elev= 30
      14   19.69      17   19.68   20.99   19.33   38.97   18.98   50.96   18.48
   65.59   18.23   77.23   18.24   83.97      18   84.88   17.69   85.78   16.73
   87.57   15.87   88.16   15.78    88.7   15.98   88.92   16.4189.49001   16.45
   89.55   17.08   90.54   17.69   92.59   17.93   95.37   18.01  131.06   18.03
  150.88   18.53  164.75   18.61  168.72   18.86  178.63   18.88  182.59   18.59
  187.55   18.52  201.42   18.77  209.35   18.73  217.28   19.04  229.18   19.15
#Mann= 3 , 0 , 0
      14     .06       0   84.88     .04       0   90.54     .06       0
Bank Sta=84.88,90.54
XS Rating Curve= 0 ,0
Exp/Cntr=0.3,0.1

Type RM Length L Ch R = 2 ,.345    ,,,
Node Photo=.\Photos\BF4-CR-1.JPG
BEGIN DESCRIPTION:
BF4 Stream Main Street Culvert
END DESCRIPTION:
Node Name=BF4-CR-1
Bridge Culvert--1,0,-1,-1, 0
Deck Dist Width WeirC Skew NumUp NumDn MinLoCord MaxHiCord MaxSubmerge Is_Ogee
1.35,9.3,1.4,0, 265, 265, , , 0.98, 0, 3,3,,
     -21-20.0234-19.0468-18.0703-17.0937-16.1172-15.1406-14.1641-13.1875-12.2109
-11.2344-10.2578-9.28132-8.30477-7.32821-6.35165 -5.3751-4.39854-3.42198-2.44543
-1.46887 -.49232.48423621.4607922.4373493.4139054.3904615.3670176.3435737.320129
8.2966859.273242 10.249811.2263512.2029113.1794714.1560215.1325816.1091317.08569
18.06225 19.0388 20.030321.0217922.0132823.0047723.9962624.9877525.9792526.97074
27.9622328.9537229.94521 30.9367 31.928232.9196933.9111834.9026735.8941636.88565
37.8771438.8686439.8601340.8516241.84311 42.8346 43.826144.8175845.8090846.80057
47.7920648.7835549.7750450.7665451.7580352.7495253.74101 54.7325  55.72456.71548
57.7069858.6984759.6899660.6814561.6729462.6560763.6391964.6223165.6054366.58855
67.5716868.5547969.5379270.5210471.5041772.4872873.4704174.4535375.4366576.41977
77.4028978.3860279.3691480.3522681.33538 82.318583.3016384.2847485.2678786.25099
87.2341288.2172389.2003690.18348 91.166692.1497293.1328494.1111595.0894596.06775
97.0460598.0243599.0026599.98095100.9593101.9376102.9158103.8941104.8725105.8508
106.8291107.8074108.7857 109.764110.7423111.7206112.6989113.6772114.6555115.6338
116.6121117.5904118.5687 119.547120.5253121.5144122.5035123.4926124.4817125.4708
126.4599127.4491128.4382129.4273130.4164131.4055132.3946133.3837134.3728 135.362
136.3511137.3402138.3293139.3184140.3162141.3141142.3119143.3097144.3076145.3054
146.3032147.3011148.2989149.2967150.2946151.2924152.2902153.2881154.2859155.2837
156.2816157.2794158.2772159.2751160.2729161.2707162.2685163.2664164.2642 165.262
166.2599167.2577168.2555169.2534170.2281171.2027172.1774173.1521174.1268175.1015
176.0762177.0509178.0256179.0002179.9749180.9496181.9243 182.899183.8737184.8484
 185.823186.7977187.7724188.7471189.7218190.6965191.6712192.6459193.6205194.5952
195.5699196.5446197.5193 198.494199.4687200.4433 201.418202.3927203.3674204.3421
205.3168206.3122207.3076 208.303209.2984210.2938211.2892212.2847213.2801214.2755
215.2709216.2663217.2617218.2571219.2525 220.248221.2434222.2388223.2342224.2296
 225.225226.2204227.2158228.2112229.2066230.2021231.1975232.1929233.1883234.1837
235.1791236.1745  237.17238.1654239.1608
 20.1528 20.1476 20.1356 20.1371 20.1313 20.1239 20.1093 20.0937 20.0725 20.0749
 20.0689 20.0712 20.0588 20.0475 20.0368 20.0355 20.0266 20.0257 20.0205 20.0143
 20.0105 20.0012  19.992 19.9725 19.9758  19.964 19.9541 19.9527 19.9418 19.9287
 19.9246 19.9129 19.9002 19.8922 19.8855 19.8811  19.864 19.8559  19.841 19.8391
 19.8246 19.8068 19.7837  19.758 19.7397 19.7102 19.6916 19.6667 19.6421  19.619
 19.5894 19.5709 19.5441 19.5118 19.5053 19.4557 19.4299 19.4032 19.3735 19.3535
 19.3262 19.3049 19.2768 19.2487 19.2125 19.1849 19.1479 19.1536 19.1348 19.1093
 19.0855 19.0649 19.0424 19.0198 18.9841 18.9598 18.9418 18.9183 18.8943 18.8717
  18.853 18.8199 18.7894 18.7717 18.7483 18.7219  18.707   18.69 18.6848 18.6675
 18.6612 18.6596 18.6577 18.6487 18.6354 18.6294 18.6191 18.6025 18.5927 18.5982
 18.5868 18.5673 18.5693 18.5578  18.564 18.5658 18.5667  18.566 18.5635 18.5532
 18.5681 18.5747 18.5689 18.5643 18.5605 18.5746   18.58 18.5705 18.5631 18.5592
 18.5699 18.5593 18.5738 18.5632 18.5491 18.5478 18.5906 18.5481 18.5357  18.539
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     -38-37.0234-36.0468-35.0703-34.0937-33.1172-32.1406-31.1641-30.1875-29.2109
-28.2344-27.2578-26.2813-25.3047-24.3282-23.3516-22.3751-21.3985-20.4219-19.4454
-18.4688-17.4923-16.5157-15.5392-14.5626 -13.586-12.6095-11.6329-10.6564-9.67987
-8.70331-7.72675 -6.7502-5.77364-4.79709-3.82053-2.84397-1.86742-.890864   .0856
1.0622482.0388043.0302954.0217875.013278 6.004776.9962627.9877538.9792459.970737
10.9622311.9537212.94521 13.936714.9281915.9196916.9111817.9026718.8941619.88565
20.8771521.8686422.8601323.8516224.84311 25.8346 26.826127.8175928.8090829.80057
30.7920631.7835532.7750433.7665434.7580335.7495236.74101 37.7325  38.72439.71548
40.7069841.6984742.6899643.6814544.6729445.6560746.6391947.6223148.6054349.58855
50.57167 51.554852.5379253.5210454.5041655.4872956.4704157.4535358.4366559.41977
60.4028961.3860262.3691463.3522664.33538 65.318566.3016367.2847468.2678769.25099
70.2341271.2172372.2003673.18348 74.166675.1497276.1328477.1111578.0894579.06775
80.0460581.0243582.0026582.9809583.9592584.9375585.9158586.8941587.8724588.85075
89.8290690.8073691.7856592.7639593.7422694.7205695.6988696.6771597.6554698.63376
99.61206100.5904101.5687 102.547103.5253104.5144105.5035106.4926107.4817108.4708
109.4599110.4491111.4382112.4273113.4164114.4055115.3946116.3837117.3728 118.362
119.3511120.3402121.3293122.3184123.3162124.3141125.3119126.3097127.3076128.3054
129.3032130.3011131.2989132.2967133.2946134.2924135.2902136.2881137.2859138.2837
139.2816140.2794141.2772142.2751143.2729144.2707145.2685146.2664147.2642 148.262
149.2599150.2577151.2555152.2534153.2281154.2027155.1774156.1521157.1268158.1015
159.0762160.0509161.0256162.0002162.9749163.9496164.9243 165.899166.8737167.8484
 168.823169.7977170.7724171.7471172.7218173.6965174.6712175.6459176.6205177.5952
178.5699179.5446180.5193 181.494182.4687183.4433 184.418185.3927186.3674187.3421
188.3168189.3122190.3076 191.303192.2984193.2938194.2892195.2847196.2801197.2755
198.2709199.2663200.2617201.2571202.2525 203.248204.2434205.2388206.2342207.2296
 208.225209.2204210.2158211.2112212.2066213.2021214.1975215.1929216.1883217.1837
218.1791219.1745  220.17221.1654222.1608
 20.1528 20.1476 20.1356 20.1371 20.1313 20.1239 20.1093 20.0937 20.0725 20.0749
 20.0689 20.0712 20.0588 20.0475 20.0368 20.0355 20.0266 20.0257 20.0205 20.0143
 20.0105 20.0012  19.992 19.9725 19.9758  19.964 19.9541 19.9527 19.9418 19.9287
 19.9246 19.9129 19.9002 19.8922 19.8855 19.8811  19.864 19.8559  19.841 19.8391
 19.8246 19.8068 19.7837  19.758 19.7397 19.7102 19.6916 19.6667 19.6421  19.619
 19.5894 19.5709 19.5441 19.5118 19.5053 19.4557 19.4299 19.4032 19.3735 19.3535
 19.3262 19.3049 19.2768 19.2487 19.2125 19.1849 19.1479 19.1536 19.1348 19.1093
 19.0855 19.0649 19.0424 19.0198 18.9841 18.9598 18.9418 18.9183 18.8943 18.8717
  18.853 18.8199 18.7894 18.7717 18.7483 18.7219  18.707   18.69 18.6848 18.6675
 18.6612 18.6596 18.6577 18.6487 18.6354 18.6294 18.6191 18.6025 18.5927 18.5982
 18.5868 18.5673 18.5693 18.5578  18.564 18.5658 18.5667  18.566 18.5635 18.5532
 18.5681 18.5747 18.5689 18.5643 18.5605 18.5746   18.58 18.5705 18.5631 18.5592
 18.5699 18.5593 18.5738 18.5632 18.5491 18.5478 18.5906 18.5481 18.5357  18.539
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BR Coef=-1 , 0 , 0 ,, 0 ,,,0.8,-1,,0,
WSPro=,,,, 1 ,,,, 0 ,,,, 0 ,,,,-1 ,-1 ,-1 , 0 , 0 , 0 , 0 , 0
Culvert=3,0.83,1.18,21.6,0.024,0.9,1,36,1,15.828,88,15.394,54.5,Culvert #1  , 0 ,0.9
      88    54.5
BC Culvert Barrel=1,Barrel 1,0
Culvert Bottom n=0.024
BC Design=,, 0 ,, 0 ,,,,,,
BC Use User HTab Curves=0
BC User HTab FreeFlow(D)= 0

Type RM Length L Ch R = 1 ,0.3336  ,12.63,10.34,6.74
BEGIN DESCRIPTION:
DS ofBF4 Stream Main Street Culvert - BF4_03 (SEM 2019)
END DESCRIPTION:
XS GIS Cut Line= 5
  607206.1798036 5427246.0554831  607173.4375036 5427228.1960831
  607150.0951036 5427217.0588831  607153.6934036 5427204.9938831
  607116.4400036 5427179.3821831
#Sta/Elev= 24
   -13.5   19.77   32.75   18.73   48.66   18.57   49.82    18.5   51.82   17.98
   52.98   17.59   53.34   16.54   53.63   15.56   54.52   15.28   55.16   15.32
    55.7   15.63   56.53   15.88   56.98   16.21   57.31   17.01   58.48    17.9
   59.11   18.07   61.57   18.22   62.13   18.33   63.11   18.34   67.04   18.26
   69.99   18.31   83.75   18.24   88.66   18.13  107.33   18.29
#Mann= 3 , 0 , 0
   -13.5     .06       0   51.82     .04       0   59.11     .06       0
Bank Sta=51.82,59.11
XS Rating Curve= 0 ,0
Exp/Cntr=0.3,0.1

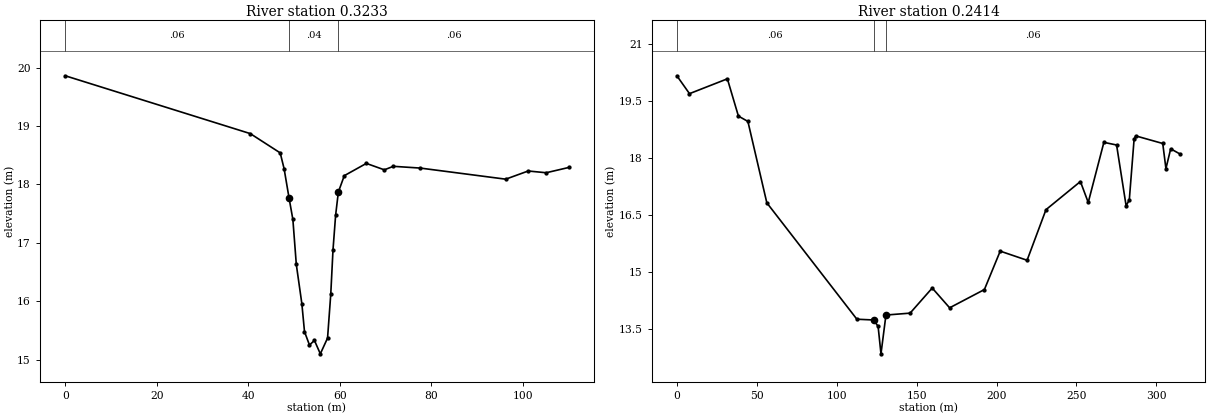
Type RM Length L Ch R = 1 ,0.3233  ,82.15,81.87,81.67
BEGIN DESCRIPTION:
BF4_02 (SEM 2019)
END DESCRIPTION:
XS GIS Cut Line= 4
607207.0335035995427242.03558309607169.3568035985427222.56228309
607157.0801035995427204.99388309607120.4617035995427176.84218309
#Sta/Elev= 26
       0   19.86   40.44   18.87   46.98   18.54   47.83   18.27   48.91   17.77
   49.75    17.4    50.5   16.63   51.71   15.96   52.29   15.48   53.38   15.25
   54.46   15.33   55.75    15.1   57.33   15.37   58.03   16.12   58.52   16.88
   59.09   17.47   59.69   17.87   60.99   18.15   65.81   18.36   69.74   18.25
   71.71   18.31    77.6   18.28   96.27   18.09  101.19   18.23  105.12    18.2
  110.03   18.29
#Mann= 3 , 0 , 0
       0     .06       0   48.91     .04       0   59.69     .06       0
Bank Sta=48.91,59.69
XS Rating Curve= 0 ,0
Exp/Cntr=0.3,0.1

Type RM Length L Ch R = 1 ,0.2414  ,16.56,241.39,18
BEGIN DESCRIPTION:
BF4_01 (SEM 2019)
END DESCRIPTION:
XS GIS Cut Line= 6
607244.0206035985427261.12108309607232.3571035985427203.02898309
607207.1148035985427150.44098309607187.2710035985427130.20038309
607069.6083035985427097.80918309607041.6139035985427060.30198309
#Sta/Elev= 30
       0   20.16     7.9   19.69    31.6   20.08   38.51    19.1   44.44   18.96
   56.29   16.82  112.64   13.76  123.18   13.74  125.92   13.57  127.71   12.85
  130.82   13.87  145.93   13.92  159.78   14.58  170.66   14.06  192.42   14.54
  202.31   15.55  219.13   15.31  230.95   16.64  252.49   17.38  257.39   16.83
  267.18   18.41  275.13   18.34   281.1   16.74  283.09    16.9  286.08   18.49
  287.08   18.58  304.01   18.38     306   17.72  308.98   18.24  314.96    18.1
#Mann= 3 , 0 , 0
       0     .06       0  123.18     .04       0  130.82     .06       0
#XS Ineff= 2 , 0
                          160.06           14.56
Permanent Ineff=
       F       F
Bank Sta=123.18,130.82
XS Rating Curve= 0 ,0
Exp/Cntr=0.3,0.1

River Reach=Corduroy Brk    ,Corduroy Brk
Reach XY= 30
599337.9305035985423585.45328309599278.6637035985423520.36568309
599247.9719035985423409.24038309599164.3634035985423314.51938309
599090.8091035985423154.71078309599026.2507035985423153.12328309
599035.2465035985423100.73568309598923.5921035995422983.78958309
598843.6878035985422942.51448309598788.1252035985422822.92258309
598715.6292035985422772.12248309598603.9748035995422561.51368309
598435.0380035985422482.13858309598385.0846035985422405.89868309
598198.1826035995422447.59718309598141.0324035995422438.07208309
598095.5240035985422377.95868309597963.0204035985422473.84388309
597888.5136035985422380.49868309597863.9602035985422286.30678309
597757.2800035985422225.55838309597724.6833035985422125.86318309
597916.4537035985421731.95068309597910.5270035985421599.23548309
597855.4935035995421522.18858309597840.6768035985421445.98848309
597730.1866035985421375.50338309597695.6849035985421324.70328309
597605.7264035995421296.97488309597386.2387024965421161.31664681

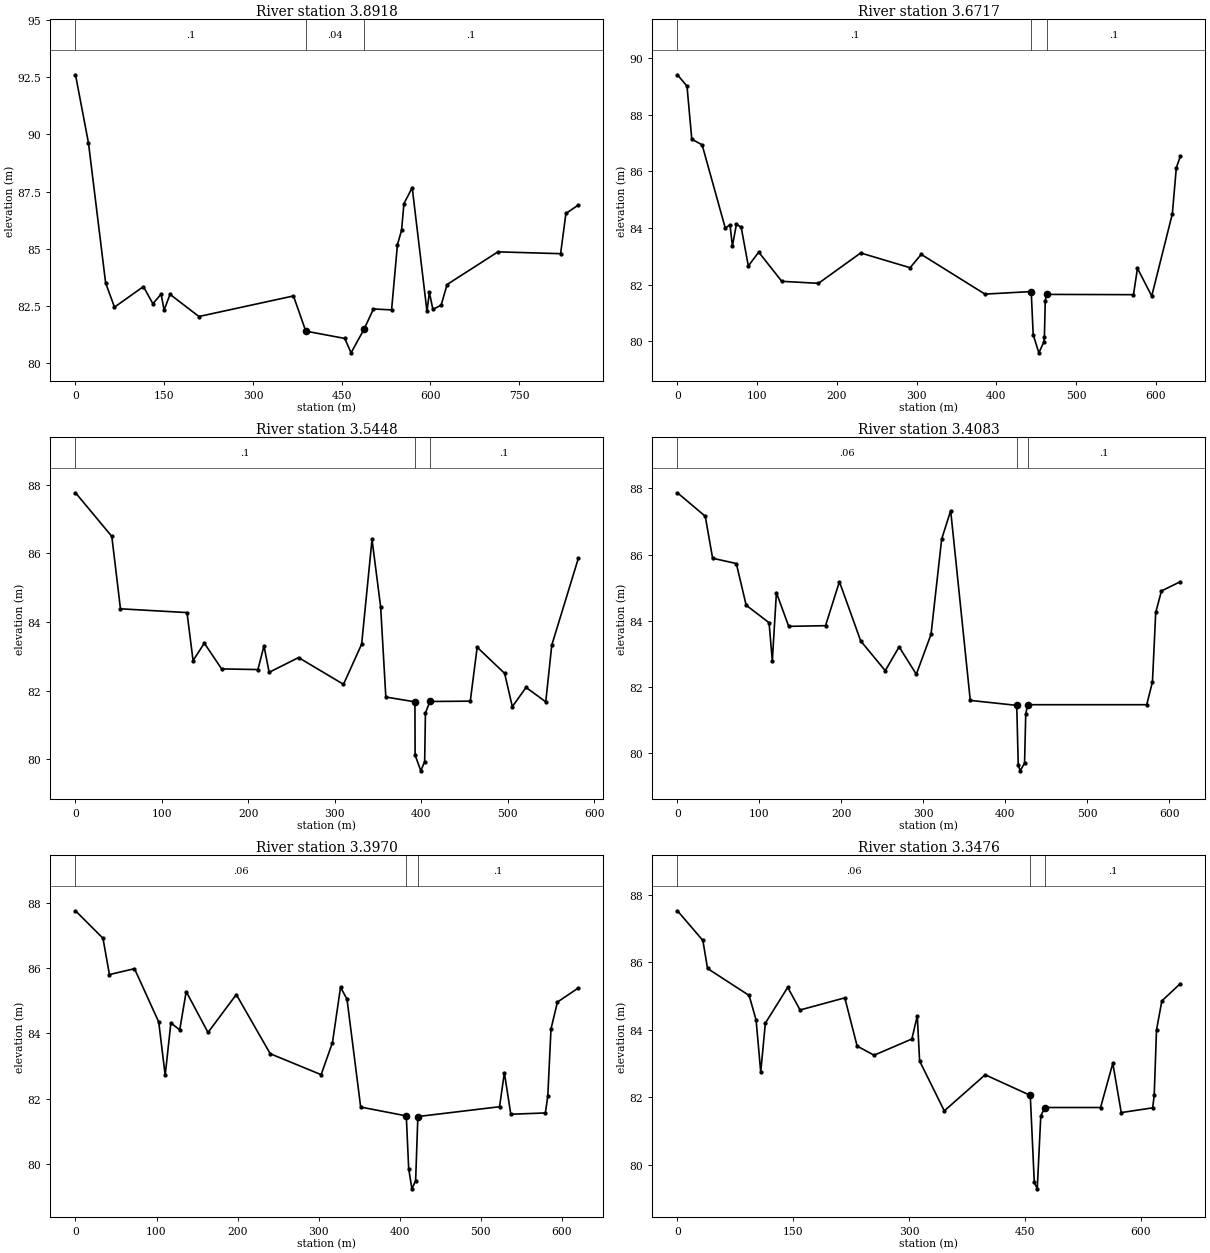
Type RM Length L Ch R = 1 ,3.8918  ,209.99,220.11,229.64
BEGIN DESCRIPTION:
CB80 (SEM 2019)
END DESCRIPTION:
XS GIS Cut Line= 6
599711.1681035985423383.01138309599349.5493035985423480.13768309
599341.7757035985423493.35298309599312.4068035995423594.15938309
599273.7051035995423624.90378309598986.2083035995423729.08708309
#Sta/Elev= 30
       0   92.61   21.97   89.62   50.92    83.5    65.9   82.44  114.83   83.34
   130.8   82.59  144.78   83.01  149.77   82.31  159.76      83  208.68   82.03
  368.44   82.93  389.26   81.39  455.23   81.07   465.8   80.44  487.88   81.48
  503.66   82.36   534.3   82.32  544.19   85.17  551.19   85.81  555.18   86.97
  569.17   87.67  594.16   82.25  598.15   83.09  604.15   82.34  618.14   82.53
  628.13   83.43  714.08   84.86  820.01   84.78     829   86.54  849.99   86.91
#Mann= 3 , 0 , 0
       0      .1       0  389.26     .04       0  487.88      .1       0
Bank Sta=389.26,487.88
XS Rating Curve= 0 ,0
Exp/Cntr=0.3,0.1

Type RM Length L Ch R = 1 ,3.6717  ,123.78,126.87,130.48
BEGIN DESCRIPTION:
CB79 (SEM 2019)
END DESCRIPTION:
XS GIS Cut Line= 6
599558.7678035985423085.61908309599315.4879035985423350.61478309
599235.8098035995423377.17418309599218.8765035985423383.78878309
599119.5591035985423411.58818309599079.3418035985423463.44488309
#Sta/Elev= 30
       0    89.4   11.99      89   17.99   87.13   30.98   86.93   59.96      84
   65.95   84.11   68.95   83.36   73.95   84.13   79.94   84.03   88.93   82.66
  101.92   83.15   130.9   82.12  176.87   82.05  229.83   83.12  291.78    82.6
  305.77   83.07  385.73   81.67  443.72   81.76  446.18   80.24   453.3    79.6
   459.5   79.98  460.25   80.17  461.34   81.43  462.89   81.66  571.99   81.65
  576.96   82.58  594.86    81.6  620.71    84.5  625.69   86.12  630.66   86.52
#Mann= 3 , 0 , 0
       0      .1       0  443.72     .04       0  462.89      .1       0
Bank Sta=443.72,462.89
XS Rating Curve= 0 ,0
Exp/Cntr=0.3,0.1

Type RM Length L Ch R = 1 ,3.5448  ,133.74,136.53,140.66
BEGIN DESCRIPTION:
CB78 (SEM 2019)
END DESCRIPTION:
XS GIS Cut Line= 6
599485.7426035985423049.63568309599196.1164035985423256.47348309
599167.1503035985423278.88128309599150.6138035985423286.48808309
599105.8087035995423321.33648309599027.4834035985423404.17808309
#Sta/Elev= 30
       0   87.76   41.99   86.49   51.99   84.38  128.96   84.27  135.96   82.87
  148.96   83.38  168.95   82.63  210.94   82.61  217.94    83.3  223.94   82.53
  257.93   82.96  309.91   82.18  330.91   83.35   342.9    86.4   352.9   84.43
  358.87   81.81  392.52   81.67  392.73   80.12  399.33   79.66  403.79   79.93
  404.65   81.34  409.77   81.68  456.53   81.69   464.5   83.26  496.24    82.5
  505.16   81.53  521.02   82.09  543.82   81.67  550.76   83.32  581.49   85.85
#Mann= 3 , 0 , 0
       0      .1       0  392.52     .04       0  409.77      .1       0
Bank Sta=392.52,409.77
XS Rating Curve= 0 ,0
Exp/Cntr=0.3,0.1

Type RM Length L Ch R = 1 ,3.4083  ,12.63,11.27,9.77
BEGIN DESCRIPTION:
CB77 (SEM 2019)
END DESCRIPTION:
XS GIS Cut Line= 6
599484.6843035985423034.81898309599169.2814035985423173.01258309
599106.6268035985423171.06338309599083.1449035985423170.73258309
599027.8614035985423235.47648309598977.7416035985423319.51118309
#Sta/Elev= 30
       0   87.87   33.94   87.16   42.92   85.89   71.86   85.73   83.84   84.47
  111.79   83.94  115.78   82.79  120.77   84.85  135.74   83.83  180.66   83.85
  197.63   85.18  223.58   83.39  253.52   82.49  270.49   83.21  291.45   82.38
  309.41   83.59  322.39   86.47  333.37   87.33  357.28   81.59  413.97   81.44
  415.82   79.64   418.1   79.46  423.52   79.69  424.98   81.19  427.41   81.46
  572.56   81.46  579.55   82.15  583.55   84.25  590.54    84.9   613.5   85.18
#Mann= 3 , 0 , 0
       0     .06       0  413.97     .04       0  427.41      .1       0
Bank Sta=413.97,427.41
XS Rating Curve= 0 ,0
Exp/Cntr=0.3,0.1

Type RM Length L Ch R = 1 ,3.3970  ,21.81,49.4,38.68
BEGIN DESCRIPTION:
CB76 (SEM 2019)
END DESCRIPTION:
XS GIS Cut Line= 6
599481.5093035995423024.23568309599174.4264035985423158.49558309
599106.9575035985423156.51128309599085.1293035985423160.81068309
599027.1463035985423231.61378309598965.0416035985423315.27788309
#Sta/Elev= 30
       0   87.75   33.91   86.91   41.89    85.8   72.82   85.98  102.74   84.35
  110.72   82.72   117.7   84.32  128.67   84.11  136.65   85.28  163.59   84.03
   198.5   85.19  240.39   83.38  303.23   82.74  317.19   83.72  327.17   85.41
  335.15   85.05  352.02   81.75  408.33   81.48  411.29   79.87  415.27   79.25
  419.86    79.5  422.63   81.46  523.46   81.76  529.41    82.8  537.35   81.53
  580.02   81.57     583   82.08  586.97   84.14  594.91   84.96  620.71   85.39
#Mann= 3 , 0 , 0
       0     .06       0  408.33     .04       0  422.63      .1       0
Bank Sta=408.33,422.63
XS Rating Curve= 0 ,0
Exp/Cntr=0.3,0.1

Type RM Length L Ch R = 1 ,3.3476  ,2.69,30.24,49.78
BEGIN DESCRIPTION:
CB75 (SEM 2019)
END DESCRIPTION:
XS GIS Cut Line= 6
599480.3848035985423014.37988309599174.7905035985423132.78118309
599049.1035035985423136.52988309599047.4261035985423156.18048309
599019.8422035985423231.30278309598958.6916035985423305.75288309
#Sta/Elev= 30
       0   87.52   32.97   86.64   38.97   85.81   92.92   85.01  101.92   84.28
  107.91   82.74  113.91   84.19  142.88   85.25  158.87   84.58  216.82   84.94
  232.81   83.51  254.79   83.24  303.75   83.72  310.74   84.41  313.74   83.07
  345.71   81.59  398.67   82.66  457.12   82.05  462.33   79.47  466.15   79.28
  470.73   81.44  476.06   81.69  548.19   81.69  564.04      83  574.97   81.54
  615.69   81.68  617.68   82.05  620.66   83.99  627.61   84.85  651.45   85.36
#Mann= 3 , 0 , 0
       0     .06       0  457.12     .04       0  476.06      .1       0
Bank Sta=457.12,476.06
XS Rating Curve= 0 ,0
Exp/Cntr=0.3,0.1

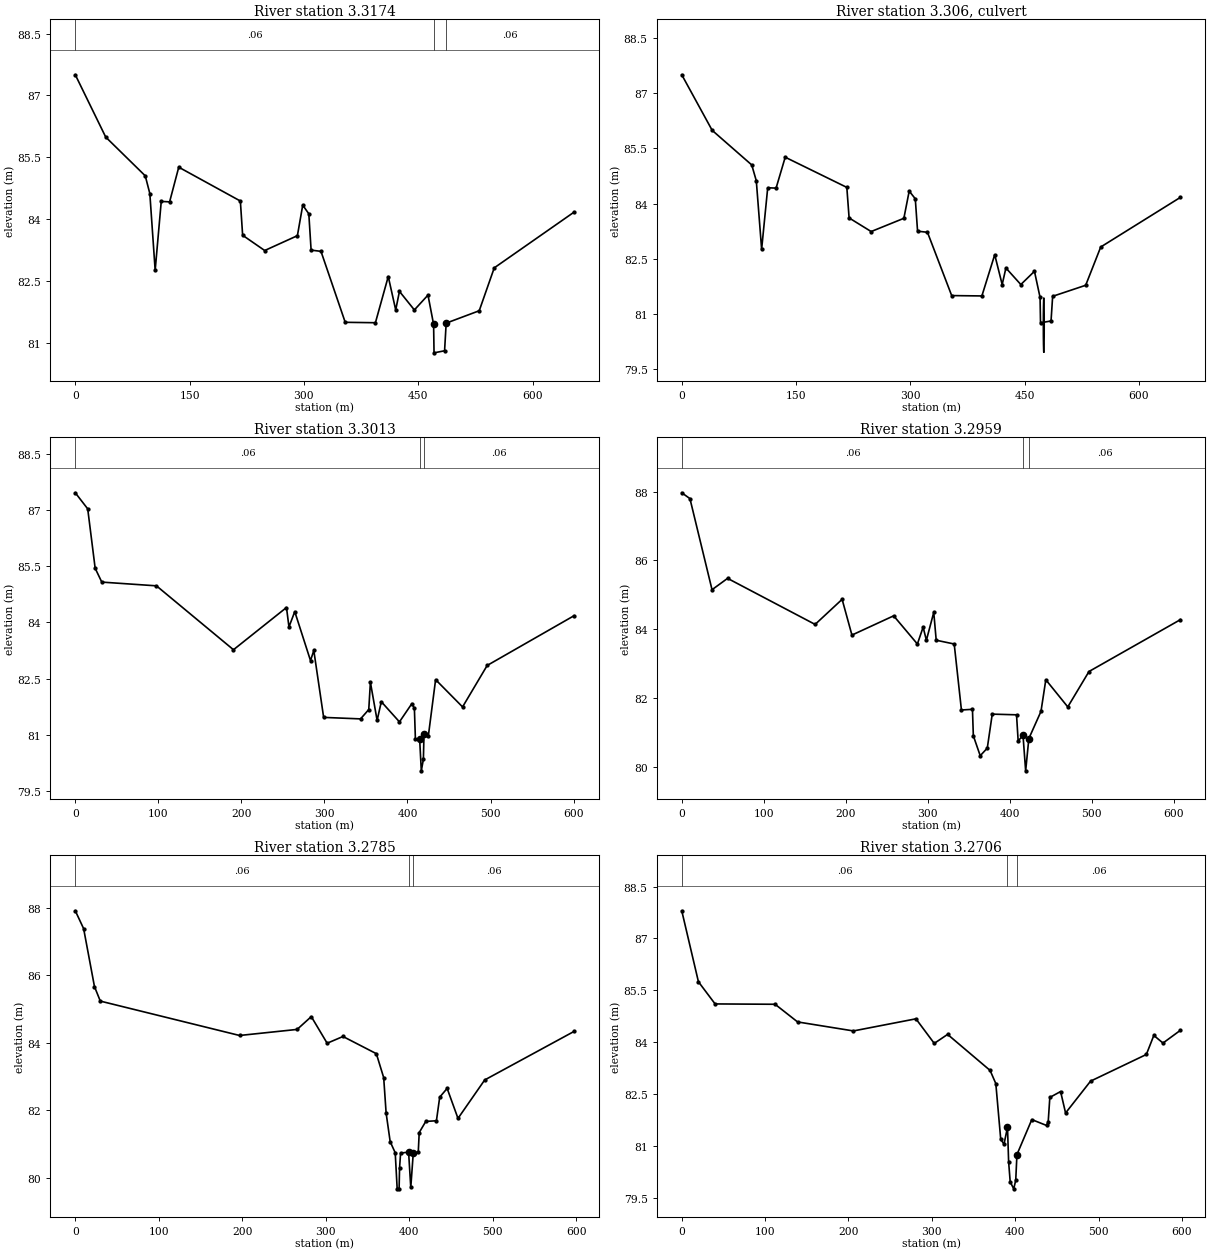
Type RM Length L Ch R = 1 ,3.3174  ,1.18,16.02,16.39
BEGIN DESCRIPTION:
US of Corduroy Brook Newoundland T'Railway Culvert - CB74 (SEM 2019)
END DESCRIPTION:
XS GIS Cut Line= 6
599477.3156035985423002.26198309599167.7525035985423128.60078309
599046.8245035985423134.69938309599034.5276035985423143.94348309
598956.0028035995423146.19228309598903.9227035995423236.96108309
#Sta/Elev= 30
       0    87.5   39.92   85.99   91.82   85.05   97.81   84.62   104.8   82.76
  112.78   84.43  123.76   84.42  135.74   85.26  216.58   84.44  219.57   83.61
  248.52   83.24  291.43    83.6  298.42   84.34  306.41   84.13   309.4   83.25
  322.37   83.22  354.16    81.5  393.79   81.49  410.63   82.61  420.42    81.8
  425.31   82.25  444.89    81.8  462.77   82.16  470.13   81.45  470.71   80.76
  484.53   80.81  486.63   81.48  529.98   81.78  549.71   82.82  654.36   84.17
#Mann= 3 , 0 , 0
       0     .06       0  470.13     .04       0  486.63     .06       0
Bank Sta=470.13,486.63
XS Rating Curve= 0 ,0
Exp/Cntr=0.3,0.1

Type RM Length L Ch R = 2 ,3.306   ,,,
Node Photo=.\Photos\CB-CR-14.JPG
BEGIN DESCRIPTION:
Corduroy Brook Newoundland T'Railway Culvert
END DESCRIPTION:
Node Name=CB-CR-14
Bridge Culvert--1,0,-1,-1, 0
Deck Dist Width WeirC Skew NumUp NumDn MinLoCord MaxHiCord MaxSubmerge Is_Ogee
3,7,1.4,0, 400, 400, , , 0.98, 0, 3,3,,
     -19 -17.008 -15.016  -14.02 -12.027 -10.035  -8.043  -7.047  -5.055  -4.059
  -2.067  -1.071   -.074    .922   1.918   2.914    3.91   4.906   5.902   7.894
    8.89  10.882  11.879  13.871  15.863  17.855  18.851  19.847  20.843  22.835
  23.832  24.828   26.82  27.816  29.808  30.804    31.8  32.796  33.792  35.785
  36.781  37.777  39.769  40.765  41.761  43.753  44.749  45.745  46.741  47.738
   49.73  50.726  51.722  52.718  53.714   54.71  55.706  56.702  59.691  62.679
  63.675  65.667  67.659  68.655  70.647  71.643   72.64  74.632  76.624  79.612
  81.604    82.6  85.589  88.577  90.569  93.557  94.553   95.55  96.546  97.542
  98.538  99.534 102.522 104.514 108.499 109.495 111.487 113.479 115.471 116.467
 118.459 120.452  123.44 125.432 127.424 132.405 135.393 138.381 140.373 141.369
 144.358  146.35 147.346 150.334  151.33 153.322 157.307 161.291 162.287 165.275
 166.271 168.264  169.26 171.252 173.244 175.236 177.228  179.22 180.217 181.213
 183.205 184.201 185.195 186.189 188.178 192.155 194.144 196.133 197.127 198.121
  200.11 201.104 203.093 204.087 206.076 208.064 211.047 213.036  214.03 215.024
 217.013  220.99 221.985 223.973 225.962  227.95 228.945 230.933 232.922 233.916
 234.911 235.905 237.894 238.888 240.876 241.871 243.859 244.854 246.842 247.837
 249.825 251.814 253.802 254.797 256.785  257.78 258.774 259.768 260.763 261.757
 262.751  264.74 265.734 266.728 267.723 268.717 269.711 270.706   271.7  272.69
 273.681 274.671 275.662 277.643 278.633 279.623 280.614 281.604 282.595 283.585
 285.566 286.557 287.547 288.537 290.518 291.509 292.499  293.49  295.47 296.461
 297.451 298.442 299.432 301.413 302.403 303.394 305.375 308.346 311.317 314.289
 316.269  318.25 321.222 322.212 323.203 325.183 326.174 327.164 329.145 331.126
 332.116 336.074 337.063 338.052  340.03 342.007 342.996 343.985 344.974 347.941
  348.93 350.908 351.897 353.875 354.864 355.853 356.842 359.809 360.798 362.776
 363.765 364.754 365.743 366.731 368.709 370.687 371.676 372.665 373.654 374.643
 375.632 376.621 378.599 379.588 380.577 381.566 382.555 383.544 384.533 386.511
 388.489 389.478 390.467 391.456 392.444 393.433 394.422  395.41 397.387 399.363
 400.352  401.34 403.317 404.305 405.293 408.258 409.247 411.223 414.188 416.165
 418.141  419.13 421.106  425.06 427.036 429.013 430.001 430.989 431.978 432.958
 434.919   435.9  436.88 438.841 439.822 440.802 441.783 442.763 444.724 445.704
 446.685 447.665 449.626 451.587 452.568 453.548 455.509  456.49  457.47 458.451
 459.431 461.392 462.373 464.333 466.294 468.255 470.216 472.177 474.146 476.116
 478.085 480.054 481.039 483.992 485.962 486.946 488.915   489.9 490.885 492.854
 493.838 494.823 495.808 497.745 499.683 500.652 501.621  502.59 503.559 504.528
 506.466 508.403 509.372 510.341  511.31 512.279 514.217 515.186  516.18 517.174
 518.168 519.162 520.156  521.15 523.139 524.133 525.127 527.115 529.103 534.074
 537.056 541.968 544.916 547.863 549.828 552.775 553.758 556.705 559.652 565.547
 569.477  572.44 575.435 579.429 581.426 582.424 585.419 588.415 594.405 599.397
 601.394 603.391 607.385 609.381 612.377 614.373 617.369 621.362 626.354 631.346
 634.342 636.338 640.332 642.329 643.327 645.324 649.318  654.31 656.307 662.297
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     -79 -77.008 -75.016  -74.02 -72.027 -70.035 -68.043 -67.047 -65.055 -64.059
 -62.067 -61.071 -60.074 -59.078 -58.082 -57.086  -56.09 -55.094 -54.098 -52.106
  -51.11 -49.118 -48.121 -46.129 -44.137 -42.145 -41.149 -40.153 -39.157 -37.165
 -36.168 -35.172  -33.18 -32.184 -30.192 -29.196   -28.2 -27.204 -26.208 -24.215
 -23.219 -22.223 -20.231 -19.235 -18.239 -16.247 -15.251 -14.255 -13.259 -12.262
  -10.27  -9.274  -8.278  -7.282  -6.286   -5.29  -4.294  -3.298   -.309   2.679
   3.675   5.667   7.659   8.655  10.647  11.643   12.64  14.632  16.624  19.612
  21.604    22.6  25.589  28.577  30.569  33.557  34.553   35.55  36.546  37.542
  38.538  39.534  42.522  44.514  48.499  49.495  51.487  53.479  55.471  56.467
  58.459  60.452   63.44  65.432  67.424  72.405  75.393  78.381  80.373  81.369
  84.358   86.35  87.346  90.334   91.33  93.322  97.307 101.291 102.287 105.275
 106.271 108.264  109.26 111.252 113.244 115.236 117.228  119.22 120.217 121.213
 123.205 124.201 125.195 126.189 128.178 132.155 134.144 136.133 137.127 138.121
  140.11 141.104 143.093 144.087 146.076 148.064 151.047 153.036  154.03 155.024
 157.013  160.99 161.985 163.973 165.962  167.95 168.945 170.933 172.922 173.916
 174.911 175.905 177.894 178.888 180.876 181.871 183.859 184.854 186.842 187.837
 189.825 191.814 193.802 194.797 196.785  197.78 198.774 199.768 200.763 201.757
 202.751  204.74 205.734 206.728 207.723 208.717 209.711 210.706   211.7  212.69
 213.681 214.671 215.662 217.643 218.633 219.623 220.614 221.604 222.595 223.585
 225.566 226.557 227.547 228.537 230.518 231.509 232.499  233.49  235.47 236.461
 237.451 238.442 239.432 241.413 242.403 243.394 245.375 248.346 251.317 254.289
 256.269  258.25 261.222 262.212 263.203 265.183 266.174 267.164 269.145 271.126
 272.116 276.074 277.063 278.052  280.03 282.007 282.996 283.985 284.974 287.941
  288.93 290.908 291.897 293.875 294.864 295.853 296.842 299.809 300.798 302.776
 303.765 304.754 305.743 306.731 308.709 310.687 311.676 312.665 313.654 314.643
 315.632 316.621 318.599 319.588 320.577 321.566 322.555 323.544 324.533 326.511
 328.489 329.478 330.467 331.456 332.444 333.433 334.422  335.41 337.387 339.363
 340.352  341.34 343.317 344.305 345.293 348.258 349.247 351.223 354.188 356.165
 358.141  359.13 361.106  365.06 367.036 369.013 370.001 370.989 371.978 372.958
 374.919   375.9  376.88 378.841 379.822 380.802 381.783 382.763 384.724 385.704
 386.685 387.665 389.626 391.587 392.568 393.548 395.509  396.49  397.47 398.451
 399.431 401.392 402.373 404.333 406.294 408.255 410.216 412.177 414.146 416.116
 418.085 420.054 421.039 423.992 425.962 426.946 428.915   429.9 430.885 432.854
 433.838 434.823 435.808 437.745 439.683 440.652 441.621  442.59 443.559 444.528
 446.466 448.403 449.372 450.341  451.31 452.279 454.217 455.186  456.18 457.174
 458.168 459.162 460.156  461.15 463.139 464.133 465.127 467.115 469.103 474.074
 477.056 481.968 484.916 487.863 489.828 492.775 493.758 496.705 499.652 505.547
 509.477  512.44 515.435 519.429 521.426 522.424 525.419 528.415 534.405 539.397
 541.394 543.391 547.385 549.381 552.377 554.373 557.369 561.362 566.354 571.346
 574.342 576.338 580.332 582.329 583.327 585.324 589.318  594.31 596.307 602.297
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BR Coef=-1 , 0 , 0 ,, 0 ,,,0.8,-1,,0,
WSPro=,,,, 1 ,,,, 0 ,,,, 0 ,,,,-1 ,-1 ,-1 , 0 , 0 , 0 , 0 , 0
Culvert=1,1.5,,12.5,0.024,0.5,1,2,1,79.944,475,79.914,417,Culvert #1  , 0 ,1.4
     475     417
BC Culvert Barrel=1,1,0
Culvert Bottom n=0.024
BC Design=,, 0 ,, 0 ,,,,,,
BC Use User HTab Curves=0
BC User HTab FreeFlow(D)= 0

Type RM Length L Ch R = 1 ,3.3013  ,7.44,5.4,6.09
BEGIN DESCRIPTION:
DS of Corduroy Brook Newoundland T'Railway Culvert - CB71/CB73 (SEM 2019)
END DESCRIPTION:
XS GIS Cut Line= 6
599410.6008035985422985.07718309599159.8489035985423123.08088309
599091.7439035985423135.01378309599022.2906035995423126.74558309
598954.9709035985423145.02808309598903.5358035985423236.04498309
#Sta/Elev= 30
       0   87.47   14.96   87.04   23.93   85.45   31.91   85.08   97.73   84.98
  190.48   83.27  254.31    84.4   257.3   83.88  264.28   84.29  283.23   82.98
  287.21   83.25  299.06   81.46  343.51   81.42  353.39   81.67  355.36    82.4
  363.45   81.38  368.49   81.88  390.34   81.34  405.33   81.83  408.33    81.7
  409.56   80.87  414.66   80.88  416.66   80.03  419.17   80.34   419.9   81.02
  425.11   80.96  433.87   82.47  466.34   81.74  495.99   82.85  600.54   84.18
#Mann= 3 , 0 , 0
       0     .06       0  414.66     .04       0   419.9     .06       0
Bank Sta=414.66,419.9
XS Rating Curve= 0 ,0
Exp/Cntr=0.3,0.1

Type RM Length L Ch R = 1 ,3.2959  ,54.54,17.44,13.07
BEGIN DESCRIPTION:
CB70/CB72 (SEM 2019)
END DESCRIPTION:
XS GIS Cut Line= 6
599409.9923035995422966.96318309599113.5534035985423125.58988309
599022.2906035995423120.13098309599007.4776035995423132.94988309
598953.8861035985423143.94328309598897.1626035985423233.00218309
#Sta/Elev= 30
       0   87.97    9.98    87.8   36.91   85.15   55.87   85.48  162.62   84.14
  195.54   84.87  207.51   83.83  258.39   84.39  287.33   83.57  294.31   84.06
   298.3   83.68  307.28   84.49  310.27   83.68  332.22   83.57  341.02   81.65
  354.47   81.67  355.55    80.9  363.93   80.32  372.55   80.54   378.6   81.53
  408.22   81.51  410.19   80.75  416.12   80.91  419.34   79.88  423.24   80.82
  438.04   81.61  443.92   82.53  470.71   81.74  496.57   82.77  608.13   84.28
#Mann= 3 , 0 , 0
       0     .06       0  416.12     .04       0  423.24     .06       0
Bank Sta=416.12,423.24
XS Rating Curve= 0 ,0
Exp/Cntr=0.3,0.1

Type RM Length L Ch R = 1 ,3.2785  ,9.6,7.88,7.18
BEGIN DESCRIPTION:
CB69 (SEM 2019)
END DESCRIPTION:
XS GIS Cut Line= 6
599403.6787035995422961.60088309599061.5941035985423081.50428309
599048.7490035985423093.34188309599001.9104035985423132.89598309
598952.9600035995423142.88498309598894.4870035985423231.25598309
#Sta/Elev= 30
       0   87.92    9.99   87.39   22.97   85.67   29.96   85.24  196.72   84.22
  265.63    84.4   282.6   84.78  301.58   83.99  320.55   84.19  360.49   83.68
  369.28   82.97  372.19   81.92  377.05   81.07  383.09   80.74  385.43   79.67
  387.74   79.68  388.31    80.3  389.53   80.73  399.11   80.76  401.72   79.71
  404.69   80.73  410.69   80.76  411.82   81.34  419.68   81.67  432.43   81.69
  436.36   82.39  445.26   82.65  458.25   81.76  490.22    82.9  597.18   84.34
#Mann= 3 , 0 , 0
       0     .06       0  399.11     .04       0  404.69     .06       0
Bank Sta=399.11,404.69
XS Rating Curve= 0 ,0
Exp/Cntr=0.3,0.1

Type RM Length L Ch R = 1 ,3.2706  ,26.06,28.04,29.19
BEGIN DESCRIPTION:
US of Princess Drive Culvert - CB68 (SEM 2019)
END DESCRIPTION:
XS GIS Cut Line= 6
599400.5036035985422954.72178309599052.1877035985423076.31608309
599028.5745035985423104.91738309598998.6392035985423131.85918309
598952.6955035985423141.56208309598893.4287035995423228.08098309
#Sta/Elev= 30
       0    87.8      20   85.75   39.99   85.11  111.98    85.1  138.97   84.59
  205.96   84.33  280.95   84.68  302.94   83.97  318.94   84.23  369.91   83.19
  376.79   82.81  382.69    81.2  386.63   81.06   390.8   81.55  392.16   80.55
  394.05   79.97  398.29   79.77  400.69   80.02  402.14   80.76  419.98   81.77
  437.66    81.6  439.63    81.7  441.59   82.41   454.5   82.58  460.49   81.96
  490.47   82.88  557.38   83.65  566.37    84.2  577.36   83.98  598.34   84.35
#Mann= 3 , 0 , 0
       0     .06       0   390.8     .04       0  402.14     .06       0
Bank Sta=390.8,402.14
XS Rating Curve= 0 ,0
Exp/Cntr=0.3,0.1