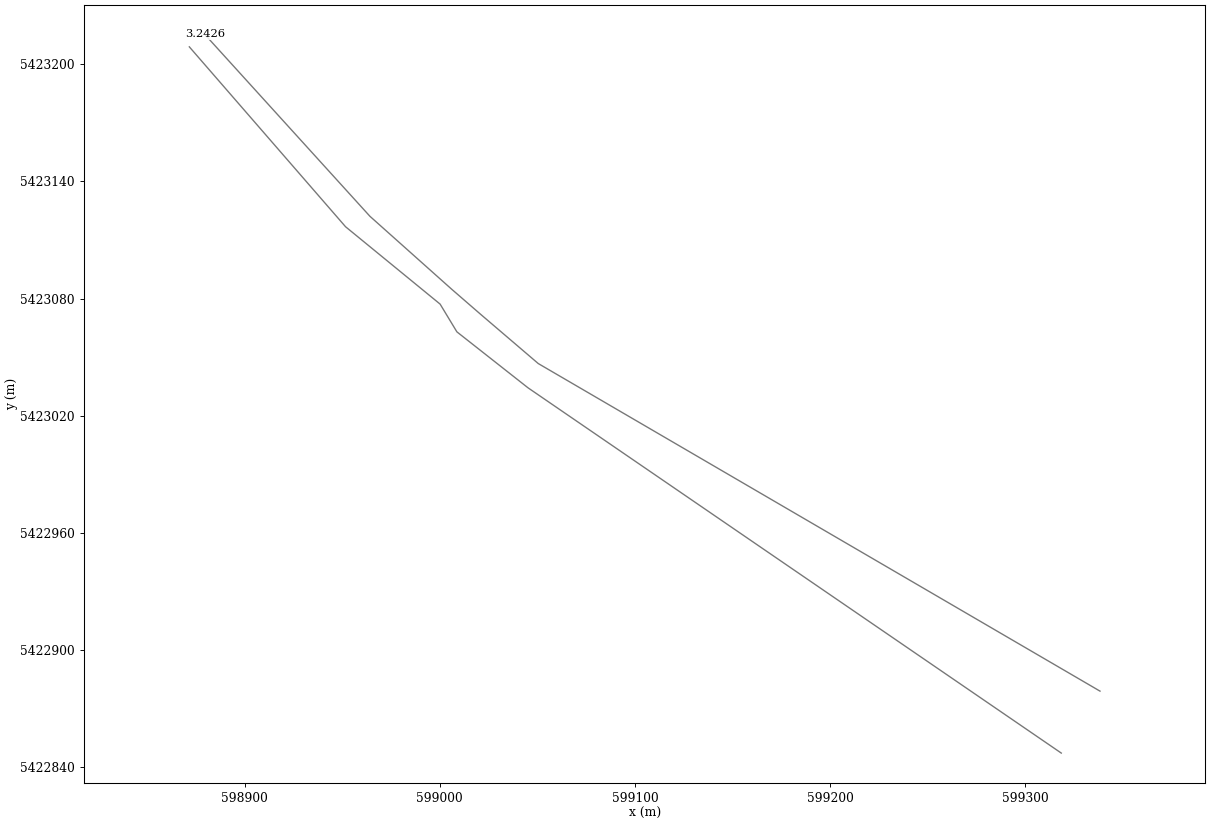
HEC-RAS study Exploits_FMM.prj: Exploits_FMM

--- Exploits_FMM.g01 (geometry) --- (continued)

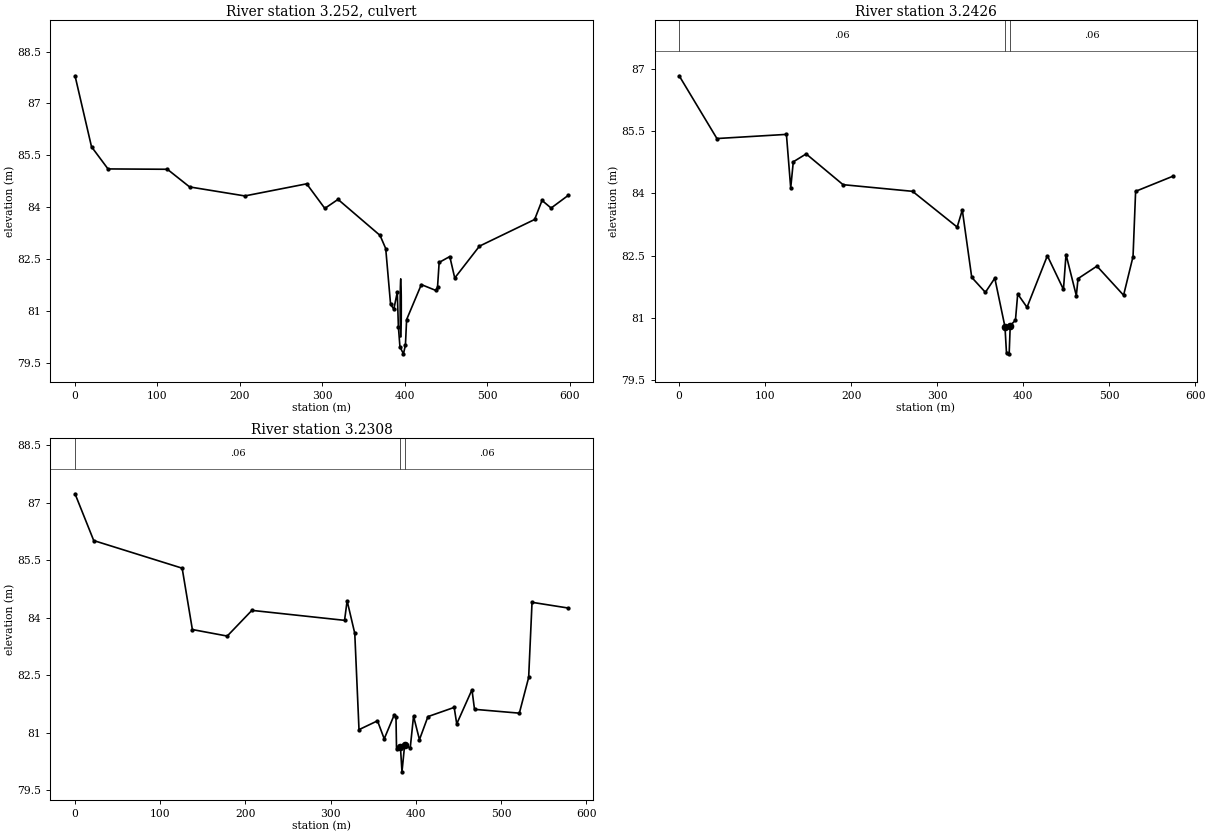
Type RM Length L Ch R = 2 ,3.252   ,,,
Node Photo=.\Photos\CB-CR-13.JPG
BEGIN DESCRIPTION:
Princess Drive Culvert
END DESCRIPTION:
Node Name=CB-CR-13
Bridge Culvert--1,0,-1,-1, 0
Deck Dist Width WeirC Skew NumUp NumDn MinLoCord MaxHiCord MaxSubmerge Is_Ogee
7,15,1.4,0, 400, 400, , , 0.98, 0, 3,3,,
       01.9953972.9930954.988492 5.986196.9838887.9815869.97698310.9746811.97238
12.9700813.9677815.9631717.9585718.9562719.9539722.9470623.9447624.9424625.94016
28.9332529.9309531.9263532.9240534.9194435.9171436.9148437.9125439.9079340.90563
41.9033342.9010343.8987344.8964245.8941246.8918248.8872249.8849150.8826151.88031
54.8734155.87111 57.8665 58.8642 59.8619 60.8596 61.8573  62.85564.8503965.84809
67.8434868.8411969.8388870.8365871.8342873.8296774.8273875.8250776.8227777.82047
78.8181779.8158681.8112683.8066684.8043685.8020686.7997588.7951589.7928591.78825
93.7836594.7813495.7790496.7767497.7744499.76983100.7675102.7629103.7606104.7583
 105.756106.7537107.7514108.7491110.7445111.7422112.7399113.7376 115.733116.7307
118.7261119.7238120.7215121.7192123.7146124.7123127.7054129.7008131.6962132.6939
133.6916134.6893 135.687136.6847138.6801139.6778141.6732142.6709143.6686 145.664
147.6593 148.657150.6525152.6478153.6455157.6363 158.634161.6271163.6225164.6202
165.6179167.6133 168.611169.6087171.6041172.6018173.5995174.5972175.5949 178.588
179.5857180.5834181.5811182.5788184.5742186.5696 188.565189.5627190.5604191.5581
195.5489196.5466199.5397200.5374202.5328204.5282206.5236207.5213209.5166 211.512
214.5051215.5028216.5005217.4982219.4883221.4783225.4583227.4483228.4433229.4384
231.4284233.4184234.4134236.4034237.3984238.3934239.3885240.3835241.3785242.3735
243.3685244.3635245.3585246.3535248.3435251.3286252.3236254.3136255.3086256.3036
257.2986258.2936259.2886261.2787262.2339264.1445266.0551267.0104267.9657 268.921
270.8315272.7421273.6974274.6526275.6079276.5632 279.434281.3495282.3072 283.265
284.2227285.1805286.1382287.0959288.0537289.9691291.9654292.9636293.9617294.9598
295.9579297.9542298.9524299.9505301.9468 303.943304.9412306.9374309.9318311.9281
312.9262313.9244315.9207317.9169 318.915322.9076323.9057324.9039 325.902327.8983
329.8945331.8908333.8871335.8833337.8802338.8789339.8777340.8764342.8738344.8713
346.8688347.8675350.8637351.8624352.8611353.8599355.8573 356.856359.8522361.8497
363.8472364.8459366.8434368.8408370.8383374.8332375.8319376.8306377.8294379.8268
380.8256381.8243 382.823383.8217384.8205385.8192387.8167388.8154389.8141390.8128
391.8116392.8103393.8091395.8065396.8052 397.804399.8014400.8001401.7989402.7976
403.7963404.7951405.7938406.7925407.7793 409.753411.7266 414.687416.6606418.6342
419.6211420.6079422.5815425.5419426.5287427.5156428.5024 430.476431.4628432.4496
436.3969438.3705439.3573440.3441441.3309443.3045444.2914 446.265447.2518 451.199
452.1859453.1727455.1463456.1331458.1192460.1177 461.117463.1155 465.114467.1125
468.1118469.1111471.1096472.1089475.1067 476.106478.1045 480.103482.1015483.1008
484.1001486.0986488.0971489.0964491.0949496.0912497.0905498.0898499.0891500.0883
501.0655502.0426503.9969505.9513506.9284507.9055508.8827 510.837513.7685514.7457
   516.7518.6542520.6086522.5629524.5172525.4943526.4715527.4487528.4258530.3801
531.3573533.3116534.2888535.2659 536.243538.1973539.1745540.1517542.1115544.0768
545.0594546.0421547.0248548.0074550.9554551.9381555.8688558.8167559.7994 560.782
561.7647  563.73564.7127565.6954 566.678568.6434 569.626571.5913 572.574573.5566
574.5393 575.522576.5046  578.47580.4353582.4006583.3833586.3312587.3139589.2792
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     -16-14.0046-13.0069-11.0115-10.0138-9.01611-8.01841-6.02301-5.02532-4.02762
-3.02992-2.03222 -.03683 1.95857 2.95627 3.95397 6.94706 7.94476 8.94246 9.94016
12.9332513.9309515.9263516.9240518.9194419.9171420.9148421.9125423.9079324.90563
25.9033326.9010327.8987328.8964229.8941230.8918232.8872233.8849134.8826135.88031
38.8734139.87111 41.8665 42.8642 43.8619 44.8596 45.8573  46.85548.8503949.84809
51.8434852.8411953.8388854.8365855.8342857.8296758.8273859.8250760.8227761.82047
62.8181763.8158665.8112667.8066668.8043669.8020670.7997572.7951573.7928575.78825
77.7836578.7813479.7790480.7767481.7744483.76983 84.7675 86.7629 87.7606 88.7583
  89.756 90.7537 91.7514 92.7491 94.7445 95.7422 96.7399 97.7376  99.733100.7307
102.7261103.7238104.7215105.7192107.7146108.7123111.7054113.7008115.6962116.6939
117.6916118.6893 119.687120.6847122.6801123.6778125.6732126.6709127.6686 129.664
131.6593 132.657134.6525136.6478137.6455141.6363 142.634145.6271147.6225148.6202
149.6179151.6133 152.611153.6087155.6041156.6018157.5995158.5972159.5949 162.588
163.5857164.5834165.5811166.5788168.5742170.5696 172.565173.5627174.5604175.5581
179.5489180.5466183.5397184.5374186.5328188.5282190.5236191.5213193.5166 195.512
198.5051199.5028200.5005201.4982203.4883205.4783209.4583211.4483212.4433213.4384
215.4284217.4184218.4134220.4034221.3984222.3934223.3885224.3835225.3785226.3735
227.3685228.3635229.3585230.3535232.3435235.3286236.3236238.3136239.3086240.3036
241.2986242.2936243.2886245.2787246.2339248.1445250.0551251.0104251.9657 252.921
254.8315256.7421257.6974258.6526259.6079260.5632 263.434265.3495266.3072 267.265
268.2227269.1805270.1382271.0959272.0537273.9691275.9654276.9636277.9617278.9598
279.9579281.9542282.9524283.9505285.9468 287.943288.9412290.9374293.9318295.9281
296.9262297.9244299.9207301.9169 302.915306.9076307.9057308.9039 309.902311.8983
313.8945315.8908317.8871319.8833321.8802322.8789323.8777324.8764326.8738328.8713
330.8688331.8675334.8637335.8624336.8611337.8599339.8573 340.856343.8522345.8497
347.8472348.8459350.8434352.8408354.8383358.8332359.8319360.8306361.8294363.8268
364.8256365.8243 366.823367.8217368.8205369.8192371.8167372.8154373.8141374.8128
375.8116376.8103377.8091379.8065380.8052 381.804383.8014384.8001385.7989386.7976
387.7963388.7951389.7938390.7925391.7793 393.753395.7266 398.687400.6606402.6342
403.6211404.6079406.5815409.5419410.5287411.5156412.5024 414.476415.4628416.4496
420.3969422.3705423.3573424.3441425.3309427.3045428.2914 430.265431.2518 435.199
436.1859437.1727439.1463440.1331442.1192444.1177 445.117447.1155 449.114451.1125
452.1118453.1111455.1096456.1089459.1067 460.106462.1045 464.103466.1015467.1008
468.1001470.0986472.0971473.0964475.0949480.0912481.0905482.0898483.0891484.0883
485.0655486.0426487.9969489.9513490.9284491.9055492.8827 494.837497.7685498.7457
   500.7502.6542504.6086506.5629508.5172509.4943510.4715511.4487512.4258514.3801
515.3573517.3116518.2888519.2659 520.243522.1973523.1745524.1517526.1115528.0768
529.0594530.0421531.0248532.0074534.9554535.9381539.8688542.8167543.7994 544.782
545.7647  547.73548.7127549.6954 550.678552.6434 553.626555.5913 556.574557.5566
558.5393 559.522560.5046  562.47564.4353566.4006567.3833570.3312571.3139573.2792
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BR Coef=-1 , 0 , 0 ,, 0 ,,,0.8,-1,,0,
WSPro=,,,, 1 ,,,, 0 ,,,, 0 ,,,,-1 ,-1 ,-1 , 0 , 0 , 0 , 0 , 0
Culvert=1,1.7,,22.2,0.024,0.9,1,2,3,80.245,395,80.064,383,Culvert #1  , 0 ,1.7
     395     383
BC Culvert Barrel=1,1,0
Culvert Bottom n=0.024
BC Design=,, 0 ,, 0 ,,,,,,
BC Use User HTab Curves=0
BC User HTab FreeFlow(D)= 0

Type RM Length L Ch R = 1 ,3.2426  ,13.61,11.78,10.9
BEGIN DESCRIPTION:
DS of Princess Drive Culvert - CB67 (SEM 2019)
END DESCRIPTION:
XS GIS Cut Line= 6
599338.3264035985422878.78618309599050.4271035995423046.67518309
599020.9677035995423071.84438309599006.0849035985423084.74288309
598964.1711035995423122.13348309598879.5380035985423215.33688309
#Sta/Elev= 30
       0   86.83    43.9   85.32  124.73   85.42  129.72   84.13  132.71   84.76
  147.68   84.95  190.59   84.21  271.41   84.05   323.3   83.19  329.28    83.6
  340.23   81.98  356.13   81.62  367.06   81.96  378.89   80.79  380.68   80.15
  383.77   80.14  385.01   80.82  391.08   80.95  393.69   81.58  404.53   81.26
  428.18    82.5   446.9   81.69  449.88   82.53  461.87   81.54  463.87   81.95
  485.85   82.25  516.83   81.55  527.82   82.48  530.82   84.05  573.78   84.41
#Mann= 3 , 0 , 0
       0     .06       0  378.89     .04       0  385.01     .06       0
Bank Sta=378.89,385.01
XS Rating Curve= 0 ,0
Exp/Cntr=0.3,0.1

Type RM Length L Ch R = 1 ,3.2308  ,100.22,105.35,107.73
BEGIN DESCRIPTION:
CB66 (SEM 2019)
END DESCRIPTION:
XS GIS Cut Line= 6
599318.4826035985422847.03608309599045.1710035985423034.24478309
599008.7307035985423062.91468309599000.1317035985423077.13608309
598951.6682035985423116.78798309598871.6005035985423208.98678309
#Sta/Elev= 30
       0   87.23   21.95   86.01  125.73   85.29   137.7   83.69  178.61   83.52
  207.55   84.19  316.31   83.93  319.31   84.44  328.29   83.59  333.25   81.08
  354.96   81.31  362.85   80.84  374.69   81.47  376.66    81.4  377.28   80.58
  381.85   80.64  383.69   79.98  386.86   80.69  393.35    80.6  397.25   81.43
  404.21   80.82  414.14   81.42  444.96   81.66  447.94   81.23  465.82   82.12
   468.8   81.61  521.41   81.51  532.34   82.44  536.31    84.4  578.99   84.25
#Mann= 3 , 0 , 0
       0     .06       0  381.85     .04       0  386.86     .06       0
Bank Sta=381.85,386.86
XS Rating Curve= 0 ,0
Exp/Cntr=0.3,0.1