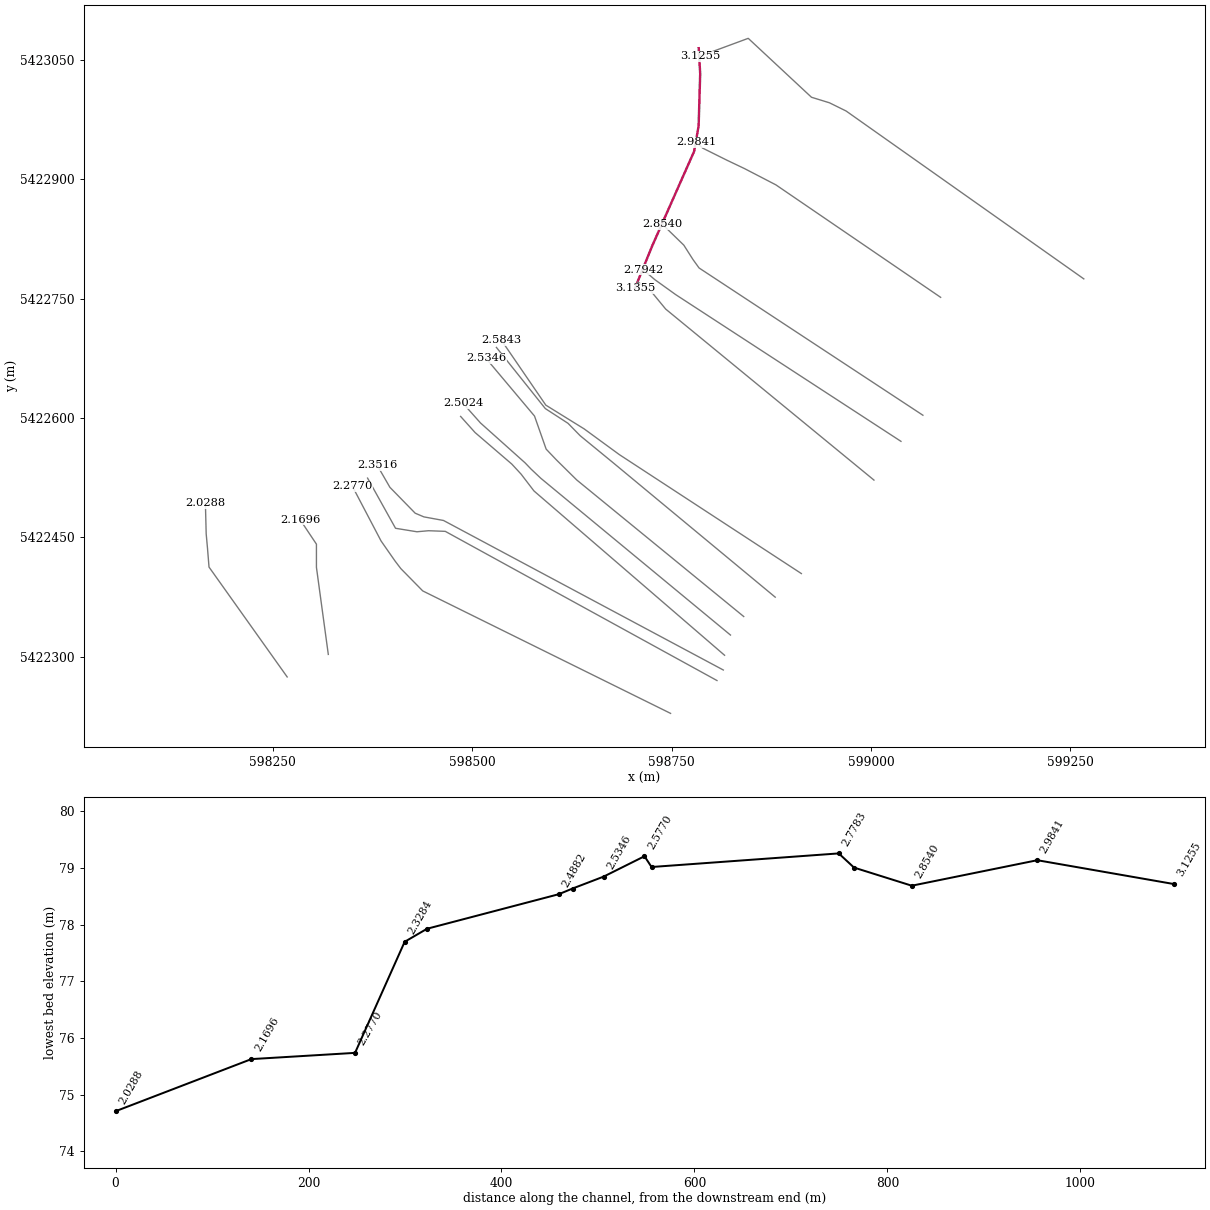
HEC-RAS study Exploits_FMM.prj: Exploits_FMM

--- Exploits_FMM.g01 (geometry) --- (continued)

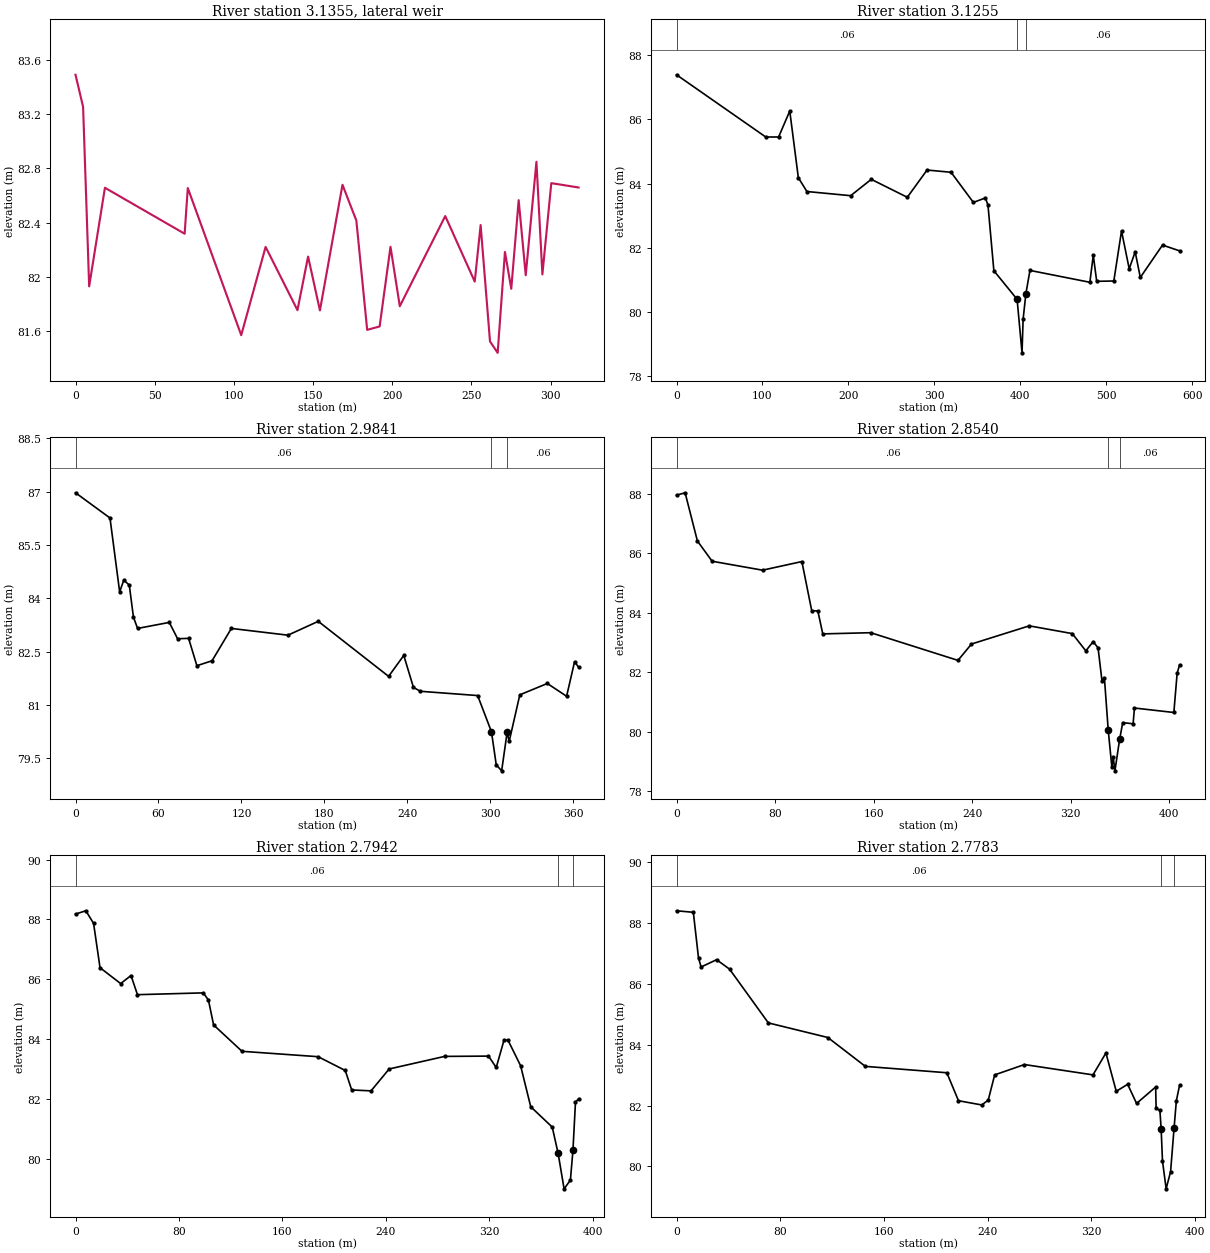
Type RM Length L Ch R = 6 ,3.1355  ,,,
BEGIN DESCRIPTION:
Earle Ave Lateral Structure
END DESCRIPTION:
Node Name=Overland Flood L
Lateral Weir Pos= 3
Lateral Weir Distance=170
Lateral Weir TW Multiple XS=0
Lateral Weir WD=2
Lateral Weir Coef=1.4
LW OverFlow Method 2D=0
LW OverFlow Use Velocity Into 2D=0
Lateral Weir WSCriteria=-1
Lateral Weir Flap Gates= 0
Lateral Weir Hagers EQN= 0 ,,,,,
Lateral Weir SS=0.05,0.05,
Lateral Weir Type= 0
Lateral Weir Connection Pos and Dist= 3 ,
Lateral Weir SE= 30
       0  83.488   4.792  83.252   8.626  81.932  18.578  82.657  68.911  82.319
  70.906  82.655 104.662  81.573 120.044  82.222 140.164  81.757 146.879  82.151
 154.352  81.755 168.593  82.679  177.35  82.416 184.189  81.612 192.047  81.637
 198.914  82.223 204.788  81.786 233.494  82.449  252.12  81.967  255.83  82.383
 261.752  81.527  266.59  81.443 271.195  82.185 275.183  81.914 279.857  82.566
 284.314  82.014 291.074  82.848 294.838   82.02 300.457  82.691  317.69  82.659
Lateral Weir Centerline= 6
     598784.0014     5423064.672     598785.8363     5423032.498
     598783.8728     5422967.001     598778.1891     5422934.955
     598725.5215     5422815.929         598704.        5422763.
LW Div RC= 0 ,False,,

Type RM Length L Ch R = 1 ,3.1255  ,140.89,141.34,141.87
BEGIN DESCRIPTION:
CB65 (SEM 2019)
END DESCRIPTION:
XS GIS Cut Line= 6
  599266.8888036 5422774.8046831  598968.7684036 5422985.7969831
  598947.8764036 5422996.1072831  598925.3868036 5423003.0525831
  598846.0789036 5423077.0938831  598785.5560036 5423054.6643831
#Sta/Elev= 30
       0   87.39  103.78   85.45  118.75   85.45  131.72   86.26   141.7   84.18
  151.68   83.75  202.57   83.62  226.52   84.13  268.43   83.57  291.39   84.42
  319.33   84.35  345.27   83.41  359.24   83.55  362.24   83.33  369.11   81.28
  396.13   80.39  401.86   78.72  403.13   79.77  406.37   80.57  411.08   81.29
  480.75   80.92  484.73   81.76  488.71   80.95  508.62   80.96  517.58   82.52
  526.52   81.34  533.47   81.87  539.43   81.07  565.25   82.08  585.11    81.9
#Mann= 3 , 0 , 0
       0     .06       0  396.13     .04       0  406.37     .06       0
Bank Sta=396.13,406.37
XS Rating Curve= 0 ,0
Exp/Cntr=0.3,0.1

Type RM Length L Ch R = 1 ,2.9841  ,132.18,130.08,127.31
BEGIN DESCRIPTION:
CB64 (SEM 2019)
END DESCRIPTION:
XS GIS Cut Line= 6
  599087.3422036 5422751.6271831  598880.7607036 5422892.9679831
  598841.3814036 5422913.4247831  598819.2225036 5422924.0081831
  598788.9800036 5422939.1293831  598781.0770036 5422946.2952831
#Sta/Elev= 30
       0   86.97   24.93   86.26   31.91   84.18    34.9   84.51   38.89   84.37
   41.88   83.47   44.88   83.15   67.81   83.32    73.8   82.86   81.77   82.87
   87.76    82.1   98.73   82.24  112.69   83.15  153.57   82.96  175.51   83.35
  226.37    81.8  237.34   82.39  244.32   81.49  249.31   81.38  290.74   81.26
  300.73   80.24  304.19   79.31   308.1   79.14  312.04   80.22  313.55   79.97
  321.23   81.28  341.12    81.6  355.05   81.24  360.81   82.21  363.72   82.06
#Mann= 3 , 0 , 0
       0     .06       0  300.73     .04       0  312.04     .06       0
Bank Sta=300.73,312.04
XS Rating Curve= 0 ,0
Exp/Cntr=0.3,0.1

Type RM Length L Ch R = 1 ,2.8540  ,57.31,59.87,61.24
BEGIN DESCRIPTION:
CB63 (SEM 2019)
END DESCRIPTION:
XS GIS Cut Line= 5
  599065.1171036 5422603.4601831  598784.4433036 5422788.5138831
  598776.8891036 5422798.9922831  598765.3136036 5422817.1823831
  598738.3420036 5422843.4443831
#Sta/Elev= 30
       0   87.95    6.98   88.03   16.96   86.41   28.93   85.73   69.83   85.43
  101.75   85.72  109.74   84.07  114.72   84.06  118.71   83.29  157.62   83.33
  228.45    82.4  239.42   82.95  286.31   83.56  321.23    83.3   332.2   82.72
  338.18   83.03  342.15   82.82   345.3   81.72  347.28   81.82  350.41   80.05
  353.33   78.82  354.49   79.14  355.83   78.69  359.65   79.75  362.16   80.31
  370.59   80.27  371.67    80.8  403.66   80.65  406.33   81.97  408.31   82.25
#Mann= 3 , 0 , 0
       0     .06       0  350.41     .04       0  359.65     .06       0
Bank Sta=350.41,359.65
XS Rating Curve= 0 ,0
Exp/Cntr=0.3,0.1

Type RM Length L Ch R = 1 ,2.7942  ,15.15,15.84,16.54
BEGIN DESCRIPTION:
CB62 (SEM 2019)
END DESCRIPTION:
XS GIS Cut Line= 4
  599037.6004036 5422570.6517831  598755.1677036 5422755.0008831
  598728.9333036 5422773.8567831  598714.1960036 5422786.4449831
#Sta/Elev= 30
       0   88.18    7.98   88.29   13.97   87.87   18.96   86.39   34.92   85.86
   42.91   86.13    47.9   85.49   98.79   85.55  102.78   85.31  106.77   84.48
  128.72    83.6   187.6   83.42  208.55   82.96  213.54   82.31  228.51   82.28
  242.48   83.01  285.38   83.43  319.31   83.44   325.3   83.06  331.29   83.97
  334.28   83.98  344.13   83.12  351.96   81.75   368.6   81.07  373.16   80.19
  377.76   79.01  382.63    79.3   384.6   80.29  386.57   81.91  388.96   82.01
#Mann= 3 , 0 , 0
       0     .06       0  373.16     .04       0   384.6     .06       0
Bank Sta=373.16,384.6
XS Rating Curve= 0 ,0
Exp/Cntr=0.3,0.1

Type RM Length L Ch R = 1 ,2.7783  ,193.4,194.01,193.92
BEGIN DESCRIPTION:
US of Harris Ave Culvert - CB61 (SEM 2019)
END DESCRIPTION:
XS GIS Cut Line= 4
  599003.7337036 5422521.9683831  598742.5944036 5422736.8439831
  598723.3109036 5422760.2968831  598707.1600036 5422771.1619831
#Sta/Elev= 30
       0   88.41   12.97   88.36   16.96   86.86   18.95   86.56   30.92    86.8
    40.9   86.49   70.83   84.72  116.72   84.24  145.65   83.29  208.49   83.08
  217.47   82.16  235.43   82.02  240.42   82.18   245.4   83.01  268.35   83.35
  321.22   83.01   331.2   83.73  339.16   82.47  347.97    82.7  354.83   82.07
  369.54   82.61  369.92   81.91  372.83   81.84  373.79   81.23  374.82   80.18
  377.64   79.26  381.08   79.83  383.76   81.26  385.52   82.16  388.01   82.67
#Mann= 3 , 0 , 0
       0     .06       0  373.79     .04       0  383.76     .06       0
Bank Sta=373.79,383.76
XS Rating Curve= 0 ,0
Exp/Cntr=0.3,0.1

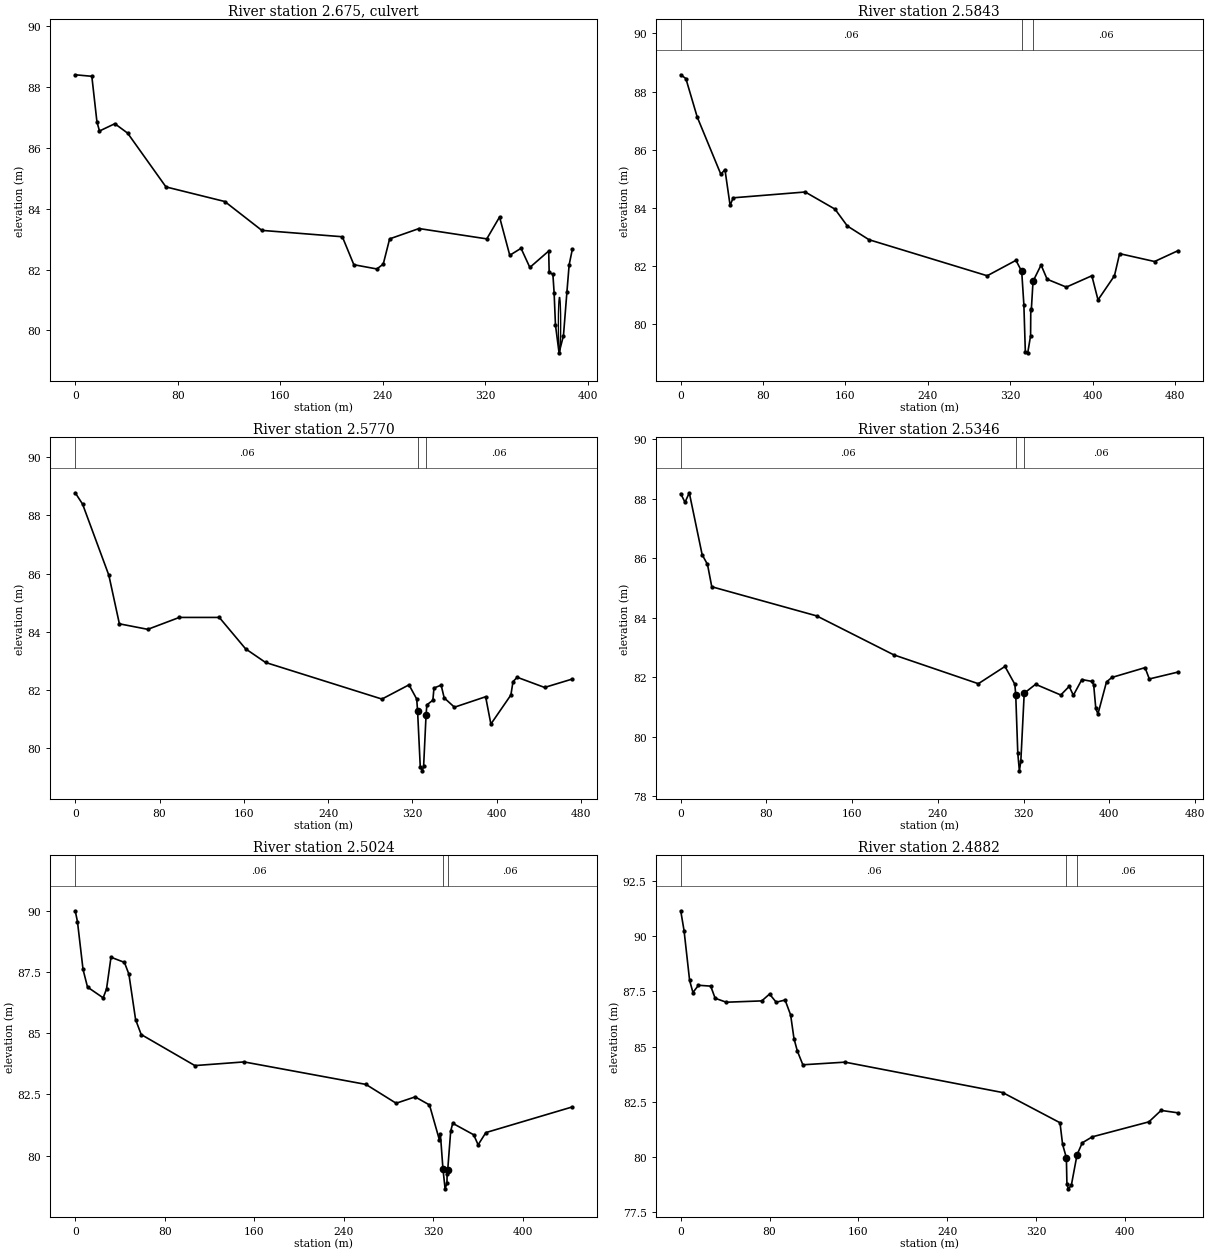
Type RM Length L Ch R = 2 ,2.675   ,,,
Node Photo=.\Photos\CB-CR-12.JPG
BEGIN DESCRIPTION:
Harris Ave Culvert
END DESCRIPTION:
Node Name=CB-CR-12
Bridge Culvert--1,0,-1,-1, 0
Deck Dist Width WeirC Skew NumUp NumDn MinLoCord MaxHiCord MaxSubmerge Is_Ogee
6.5,185,1.4,0, 400, 400, , , 0.98, 0, 3,3,,
       0    .996   5.979   7.972   9.965  12.954  17.936  19.929  21.922  25.908
  29.894   30.89  35.873  37.866  42.848   47.83   50.82  54.805  59.788  63.774
  66.763  69.752  72.742   78.72  82.706  90.678   95.66  99.646 101.639 106.621
 108.614 109.611 111.604 114.593 116.586 119.575 122.565 124.558 128.544 133.485
 141.292 143.244 149.099 151.051 153.003  155.93 156.906  159.89 166.852 167.846
 172.819 173.813 175.802 179.781  181.77 182.764 184.753 190.721 193.704 197.682
 198.677 201.661 205.639 210.612 213.595 215.565 222.461 224.431 227.386 231.327
 236.252 238.222 241.177 244.133 245.118 253.983 256.939 265.834 266.826 267.818
 273.772 280.719 282.704 286.673 288.658 296.597 298.581 301.517 307.348 309.291
  314.15 316.094 318.038 319.981 321.925 322.897 326.784 327.755 329.699 331.641
 335.521 337.461 340.371 342.311 345.221 348.131 349.101 351.041 353.951 354.927
 355.902 356.877 358.827 359.802 361.752 363.702 364.678 366.628 368.578 370.524
 371.497 372.471 374.417  375.39 376.363 378.328 382.256 384.147 385.092 386.037
 388.873 390.849 392.825 394.801 396.767 401.658 402.636 406.549 408.506 410.462
 412.419 414.375 415.353  417.31 418.288 421.223 422.201 423.179 426.114 431.983
 432.961 434.918 436.874 438.831  441.45  444.25 445.214  447.14 449.067 450.031
 451.021 453.994 454.985 457.957 459.939  461.92 465.883 470.837 471.828 472.819
  473.81 475.791 476.782 477.773 480.745 481.736  486.69 488.672 491.644 493.626
 495.607 496.598 500.561 504.525 505.515 507.497 509.479  511.46 514.433 517.377
 518.354 520.307 521.284  522.26 526.167 527.144  528.12 530.074  531.05 533.004
 534.957  536.91  539.84 543.788 545.782  546.78 548.774 550.768  553.76 554.757
 556.751 559.743  560.74 562.734 564.729 566.723 568.717 570.712 571.709 573.703
 575.697 577.692 579.686 580.683 584.672 585.653 588.595 589.576 591.537 593.499
  595.46 596.441 599.383 601.345 602.326 605.268 607.229 609.191 610.172 612.133
 614.095 615.076 618.999 620.981 623.954 626.927 627.919 629.901 631.883 633.865
 635.847 637.829 639.812 641.794 643.776 645.758 646.749 648.731 650.714 652.695
 654.675 661.607 666.558 667.548 671.509  677.45 683.391 686.362 690.328 693.317
 695.309 696.305 699.293 700.289 703.278 707.262 711.247 712.243 714.235 716.227
 718.219 720.212 721.208   723.2 725.192 727.184 728.147 731.036 732.962 734.888
 736.814 739.703 741.628 743.554 746.443 751.258 753.203 755.168 758.115  760.08
  764.01 764.992 766.957  767.94 770.887 772.852 775.799 777.764  778.73 782.597
 784.531 785.498 787.431 789.365 791.298 793.231 794.198 796.132 799.032 801.932
 804.833 807.735 811.603 814.505 818.373 824.176  826.11  828.06 830.025 833.956
 836.904 837.886 839.852   842.8 844.765  847.74 850.715 852.699 855.674 857.658
 861.625 865.553 868.414 869.368 870.321 872.228 873.182 876.043 878.903 881.764
 882.718 884.713  885.71 888.702 890.697 892.692 895.684 897.679 901.669 904.661
 906.656 911.643 914.636 921.618 925.608 930.595 933.587 937.577 940.569 944.559
 952.539 955.531 958.523 960.518 961.515 962.513 964.508 966.503   967.5 969.495
 971.488 974.476 992.4011006.3421013.3131016.2931030.1831034.1521036.1361041.097
1046.0571048.042 1052.011054.9871056.9711064.9081070.8611076.8141078.7981083.759
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     -50 -49.004 -44.021 -42.028 -40.035 -37.046 -32.064 -30.071 -28.078 -24.092
 -20.106  -19.11 -14.127 -12.134  -7.152   -2.17     .82   4.805   9.788  13.774
  16.763  19.752  22.742   28.72  32.706  40.678   45.66  49.646  51.639  56.621
  58.614  59.611  61.604  64.593  66.586  69.575  72.565  74.558  78.544  83.485
  91.292  93.244  99.099 101.051 103.003  105.93 106.906  109.89 116.852 117.846
 122.819 123.813 125.802 129.781  131.77 132.764 134.753 140.721 143.704 147.682
 148.677 151.661 155.639 160.612 163.595 165.565 172.461 174.431 177.386 181.327
 186.252 188.222 191.177 194.133 195.118 203.983 206.939 215.834 216.826 217.818
 223.772 230.719 232.704 236.673 238.658 246.597 248.581 251.517 257.348 259.291
  264.15 266.094 268.038 269.981 271.925 272.897 276.784 277.755 279.699 281.641
 285.521 287.461 290.371 292.311 295.221 298.131 299.101 301.041 303.951 304.927
 305.902 306.877 308.827 309.802 311.752 313.702 314.678 316.628 318.578 320.524
 321.497 322.471 324.417  325.39 326.363 328.328 332.256 334.147 335.092 336.037
 338.873 340.849 342.825 344.801 346.767 351.658 352.636 356.549 358.506 360.462
 362.419 364.375 365.353  367.31 368.288 371.223 372.201 373.179 376.114 381.983
 382.961 384.918 386.874 388.831  391.45  394.25 395.214  397.14 399.067 400.031
 401.021 403.994 404.985 407.957 409.939  411.92 415.883 420.837 421.828 422.819
  423.81 425.791 426.782 427.773 430.745 431.736  436.69 438.672 441.644 443.626
 445.607 446.598 450.561 454.525 455.515 457.497 459.479  461.46 464.433 467.377
 468.354 470.307 471.284  472.26 476.167 477.144  478.12 480.074  481.05 483.004
 484.957  486.91  489.84 493.788 495.782  496.78 498.774 500.768  503.76 504.757
 506.751 509.743  510.74 512.734 514.729 516.723 518.717 520.712 521.709 523.703
 525.697 527.692 529.686 530.683 534.672 535.653 538.595 539.576 541.537 543.499
  545.46 546.441 549.383 551.345 552.326 555.268 557.229 559.191 560.172 562.133
 564.095 565.076 568.999 570.981 573.954 576.927 577.919 579.901 581.883 583.865
 585.847 587.829 589.812 591.794 593.776 595.758 596.749 598.731 600.714 602.695
 604.675 611.607 616.558 617.548 621.509  627.45 633.391 636.362 640.328 643.317
 645.309 646.305 649.293 650.289 653.278 657.262 661.247 662.243 664.235 666.227
 668.219 670.212 671.208   673.2 675.192 677.184 678.147 681.036 682.962 684.888
 686.814 689.703 691.628 693.554 696.443 701.258 703.203 705.168 708.115  710.08
  714.01 714.992 716.957  717.94 720.887 722.852 725.799 727.764  728.73 732.597
 734.531 735.498 737.431 739.365 741.298 743.231 744.198 746.132 749.032 751.932
 754.833 757.735 761.603 764.505 768.373 774.176  776.11  778.06 780.025 783.956
 786.904 787.886 789.852   792.8 794.765  797.74 800.715 802.699 805.674 807.658
 811.625 815.553 818.414 819.368 820.321 822.228 823.182 826.043 828.903 831.764
 832.718 834.713  835.71 838.702 840.697 842.692 845.684 847.679 851.669 854.661
 856.656 861.643 864.636 871.618 875.608 880.595 883.587 887.577 890.569 894.559
 902.539 905.531 908.523 910.518 911.515 912.513 914.508 916.503   917.5 919.495
 921.488 924.476 942.401 956.342 963.313 966.293 980.183 984.152 986.136 991.097
 996.057 998.042 1002.011004.9871006.9711014.9081020.8611026.8141028.7981033.759
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BR Coef=-1 , 0 , 0 ,, 0 ,,,0.8,-1,,0,
WSPro=,,,, 1 ,,,, 0 ,,,, 0 ,,,,-1 ,-1 ,-1 , 0 , 0 , 0 , 0 , 0
Culvert=1,1.8,,193,0.024,0.5,1,2,1,79.291,378,79.084,336,Culvert #1  , 0 ,1
     378     336
BC Culvert Barrel=1,1,0
Culvert Bottom n=0.024
BC Design=,, 0 ,, 0 ,,,,,,
BC Use User HTab Curves=0
BC User HTab FreeFlow(D)= 0

Type RM Length L Ch R = 1 ,2.5843  ,8.39,7.31,6.47
BEGIN DESCRIPTION:
DS of Harris Ave Culvert - CB55 (SEM 2019)
END DESCRIPTION:
XS GIS Cut Line= 6
  598912.7168036 5422404.4931831  598684.5476036 5422553.9206831
  598640.2977036 5422586.3329831  598623.7612036 5422596.5856831
  598592.2485036 5422616.1576831  598536.5895036 5422697.6742831
#Sta/Elev= 30
       0   88.58       5   88.45   15.99   87.13   38.96   85.16   42.96   85.32
   47.96   84.09   50.95   84.35  120.89   84.55  149.86   83.96  161.85   83.38
  182.83   82.91  297.68   81.67   325.6    82.2  331.18   81.82  333.29   80.67
   334.7   79.06  337.04   79.02  339.81   79.61  339.99   80.48  340.56   80.52
  342.18   81.48     350   82.04  355.88   81.55  374.52   81.28   399.3   81.67
   405.3   80.84  421.27   81.67  426.27   82.43  460.22   82.16  482.85   82.53
#Mann= 3 , 0 , 0
       0     .06       0  331.18     .04       0  342.18     .06       0
Bank Sta=331.18,342.18
XS Rating Curve= 0 ,0
Exp/Cntr=0.3,0.1

Type RM Length L Ch R = 1 ,2.5770  ,42.36,42.41,42.21
BEGIN DESCRIPTION:
CB54 (SEM 2019)
END DESCRIPTION:
XS GIS Cut Line= 6
  598879.9084036 5422374.8597831  598678.0383036 5422542.6368831
  598635.3367036 5422577.7340831  598620.1232036 5422593.2783831
  598591.6191036 5422611.8452831  598530.3116036 5422688.6821831
#Sta/Elev= 30
       0   88.78    6.99   88.39   31.94   85.94   41.92   84.27   68.87   84.08
   98.81   84.49  136.73   84.49  161.69   83.41  180.65   82.94  291.11   81.68
  316.78   82.17  324.13   81.68  324.95   81.26   327.5   79.34  329.51   79.21
   330.7   79.39     333   81.14  333.74   81.48  339.45   81.64  340.49   82.06
  347.29   82.16  350.21   81.72  359.92    81.4  389.52   81.76  394.51   80.82
   413.5   81.82   415.5   82.28  419.49   82.43  445.47   82.08  471.83   82.37
#Mann= 3 , 0 , 0
       0     .06       0  324.95     .04       0     333     .06       0
Bank Sta=324.95,333
XS Rating Curve= 0 ,0
Exp/Cntr=0.3,0.1

Type RM Length L Ch R = 1 ,2.5346  ,32.49,32.18,32.57
BEGIN DESCRIPTION:
CB53 (SEM 2019)
END DESCRIPTION:
XS GIS Cut Line= 6
  598840.4193036 5422350.5179831  598631.0253036 5422522.1264831
  598605.5711036 5422547.3068831  598592.6726036 5422560.8667831
  598578.0785036 5422602.4461831  598517.2877036 5422674.8868831
#Sta/Elev= 30
       0   88.17       4   87.88    7.99    88.2   19.98   86.12   24.98   85.79
   28.97   85.04  126.87   84.06   198.8   82.75  277.69   81.78  302.56   82.36
  311.78   81.76   312.6    81.4  314.52   79.44     316   78.85  317.35   79.17
  320.51   81.46  331.13   81.76  354.63    81.4  362.46   81.69  366.38   81.39
  374.31   81.92   383.3   81.86   385.3   81.75   387.3   80.95   389.3   80.76
  397.29   81.84  402.28   81.99  433.25   82.32  437.25   81.94  463.88   82.17
#Mann= 3 , 0 , 0
       0     .06       0   312.6     .04       0  320.51     .06       0
Bank Sta=312.6,320.51
XS Rating Curve= 0 ,0
Exp/Cntr=0.3,0.1

Type RM Length L Ch R = 1 ,2.5024  ,14.1,14.23,14.22
BEGIN DESCRIPTION:
CB52 (SEM 2019)
END DESCRIPTION:
XS GIS Cut Line= 6
  598823.8167036 5422327.2346831  598585.9026036 5422524.3086831
  598573.8210036 5422535.7313831  598566.2142036 5422543.6688831
  598510.3601036 5422593.7239831  598488.4919036 5422618.3471831
#Sta/Elev= 30
       0   90.01       2   89.57       7   87.61      11   86.89   24.99   86.45
   27.99   86.81   31.99   88.11   43.99    87.9   47.99   87.42   53.99   85.56
   58.99   84.95  106.98   83.68  150.97   83.83  259.95   82.91  286.94   82.14
  303.94    82.4  316.76   82.07  325.56   80.65  326.49   80.89  328.77   79.47
  330.71   78.64  332.36   78.87  332.53   79.25  333.03    79.4  335.71      81
  337.54   81.32  356.29   80.85  360.24   80.44  367.15   80.94  444.49   81.99
#Mann= 3 , 0 , 0
       0     .06       0  328.77     .04       0  333.03     .06       0
Bank Sta=328.77,333.03
XS Rating Curve= 0 ,0
Exp/Cntr=0.3,0.1

Type RM Length L Ch R = 1 ,2.4882  ,135.22,136.59,137.12
BEGIN DESCRIPTION:
US of Cromer Avenue Culvert - CB51 (SEM 2019)
END DESCRIPTION:
XS GIS Cut Line= 6
  598816.4083036 5422301.8345831  598577.3856036 5422508.3330831
  598561.2533036 5422529.4474831  598549.6777036 5422542.0151831
  598503.4702036 5422581.7887831  598485.4116036 5422601.9763831
#Sta/Elev= 30
       0   91.16       3   90.26       8      88      11   87.45   15.99   87.78
   26.99   87.74   30.99   87.19   40.98   87.01   72.97   87.07   79.97   87.38
   85.96   87.01   93.96   87.11   98.96   86.43  101.96   85.36  104.96    84.8
  109.95   84.17  147.94   84.29  289.88   82.91  341.46   81.54  343.79   80.56
  347.21   79.95  347.69   78.77  348.95   78.54  351.67    78.7  356.82   80.09
  361.53   80.63  370.52    80.9  421.49   81.58  432.48    82.1  447.58   81.99
#Mann= 3 , 0 , 0
       0     .06       0  347.21     .04       0  356.82     .06       0
Bank Sta=347.21,356.82
XS Rating Curve= 0 ,0
Exp/Cntr=0.3,0.1

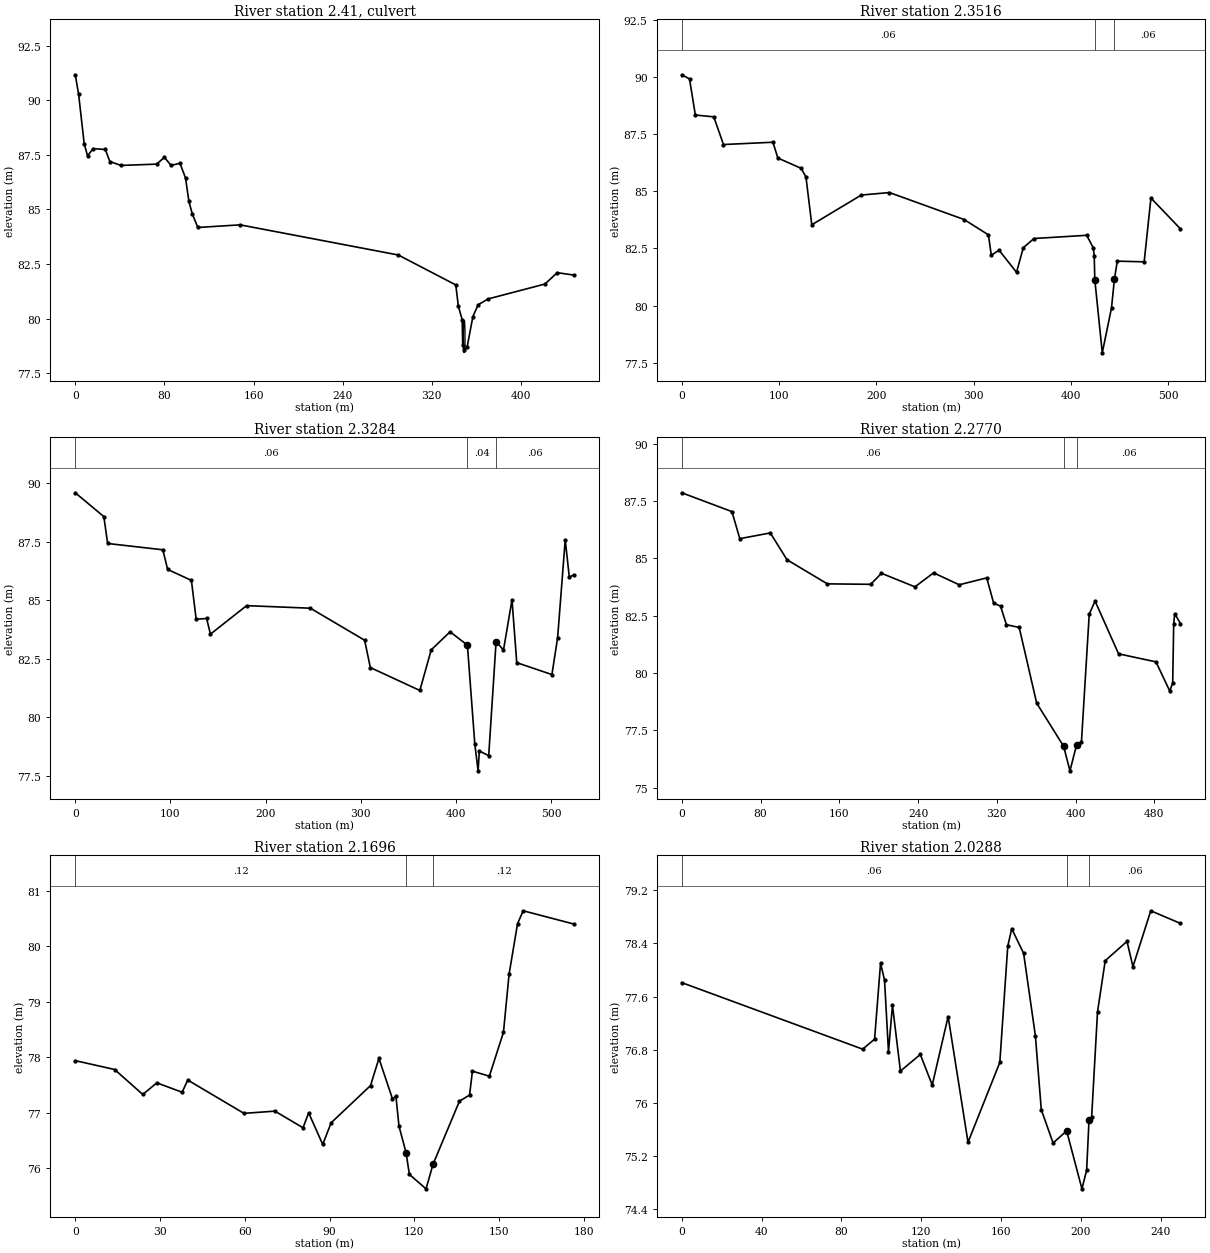
Type RM Length L Ch R = 2 ,2.41    ,,,
Node Photo=.\Photos\CB-CR-11.JPG
BEGIN DESCRIPTION:
Cromer Avenue Culvert
END DESCRIPTION:
Node Name=CB-CR-11
Bridge Culvert--1,0,-1,-1, 0
Deck Dist Width WeirC Skew NumUp NumDn MinLoCord MaxHiCord MaxSubmerge Is_Ogee
4,128,1.4,0, 400, 400, , , 0.98, 0, 3,3,,
     111112.9864114.9728122.9184123.9116 125.898127.8844129.8708132.8504134.8368
136.8232139.8027142.7823145.7619147.7483149.7347153.7075155.6939158.6735160.6599
165.6259170.5919173.5817174.5783175.5749177.5682178.5648184.5444 185.541187.5343
190.5241194.5105196.5037198.4969199.4936201.4868204.4766 208.463209.4597211.4529
214.4427215.4393217.4325218.4291 221.419225.4054 226.402229.3918232.3716233.3633
238.3213240.3045243.2793245.2625247.2457250.2205251.2121254.1869257.1618259.1491
261.1406266.1194275.0813279.0643284.0431290.0177292.0092295.9922297.9837299.9753
301.9403303.8788305.8174308.7252 311.633314.5408316.4794321.3257323.2643325.2028
329.0799331.0185334.9821340.9275342.9093348.8547351.8274353.8092358.7637361.7364
362.7273   365.7366.6909368.6727369.6636371.6085375.4983377.4432 381.333385.2228
387.1677389.1126390.0851  392.03393.0024394.9692398.9462399.9405 401.929404.9118
407.8945409.8831412.8658415.8486417.8372418.8314421.8142424.7787429.6589430.6349
 432.587434.5391436.4911438.4432439.4193441.3713442.3474443.3234445.2755447.2275
449.1796450.1556451.1317453.0837456.9879458.9399 459.916462.8441463.8371466.8161
 470.788 473.767 477.739 479.725 482.704 485.683 486.676 489.655 491.641 493.627
494.6199496.6059500.5779505.5429510.5079511.5009515.4729517.4589518.4569520.4529
 521.451 522.449 524.445526.4411528.4371529.4352531.4312534.4253535.4233537.4193
539.4154540.4134542.4095543.4075544.4055545.3839547.3406550.2757553.2108554.1891
556.1458557.1242558.1026560.0593562.9944563.9727564.9511566.9078567.8862569.8429
573.7563577.6698581.6408583.6263 584.619587.5973594.5465595.5392598.5175599.5102
601.4957605.4667609.4377612.4159615.3942618.3724621.3506622.3434623.3362627.3071
630.2854633.2717634.2672 636.258639.2443643.2261646.2124647.2078649.1987650.1942
651.1896654.1759655.1713658.1576663.1348664.1302666.1211670.1028672.0938673.0892
675.0801678.0663679.0618682.0481 684.039692.9979694.9888 699.966701.9568704.9432
705.9386 706.934708.9167712.8821714.8647722.7954724.7781726.7607728.7434730.7261
732.7087734.6915737.6655738.6568739.6481740.6395741.6308743.6135745.5961746.5875
748.5701750.5528751.5441754.5182755.5095759.4749762.4489763.4402765.4229768.3969
770.3795773.3535776.3276777.3189779.3016783.2669785.2496786.2409788.2236790.2062
791.1976794.1794 800.174803.1714804.1705807.1678 809.166812.1634815.1607816.1599
819.1572821.1554825.1519826.1509  827.15830.1474832.1456833.1447835.1429843.1359
845.1341847.1323850.1296852.1279854.1261855.1252857.1234858.1225861.1199863.1181
865.1163872.0981873.0913881.0366885.0092888.9819891.9613892.9545894.9408897.9203
899.9066904.8773907.8715909.8676910.8657911.8638913.8599 915.856919.8483922.8425
924.8386927.8328 930.827934.8193937.8135938.8115941.8057943.8019944.7999947.7941
948.7922951.7864953.7825955.7786959.7709 961.767963.7632964.7612966.7574968.7535
970.7496  975.74977.7361980.7303985.7206989.7129990.7109995.7013997.6974999.6935
 1001.691002.6881004.6841007.6781013.6661014.6651015.6631017.6591022.6491023.647
1026.6411030.634 1032.631034.626 1037.621039.6161041.6121044.6061046.6031047.601
1049.5971052.5911054.5871058.5791061.5741064.5681069.5581071.5541072.5521074.548
1078.5411080.5371082.5331086.525 1089.521090.5171092.5141093.512 1094.511101.496
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     193194.9864196.9728204.9184205.9116 207.898209.8844211.8708214.8504216.8368
218.8232221.8027224.7823227.7619229.7483231.7347235.7075237.6939240.6735242.6599
247.6259252.5919255.5817256.5783 257.575259.5681260.5648266.5444 267.541269.5342
272.5241276.5105278.5037280.4969281.4936283.4868286.4766 290.463291.4597293.4529
296.4427297.4393299.4325300.4291 303.419307.4054 308.402311.3918314.3716315.3633
320.3213322.3045325.2793327.2625329.2457332.2205333.2121336.1869339.1618341.1491
343.1406348.1194357.0813361.0643366.0431372.0177374.0092377.9922379.9837381.9753
383.9403385.8788387.8174390.7252 393.633396.5408398.4794403.3257405.2643407.2028
411.0799413.0185416.9821422.9275424.9093430.8547433.8274435.8092440.7637443.7364
444.7273   447.7448.6909450.6727451.6636453.6085457.4983459.4432 463.333467.2228
469.1677471.1126472.0851  474.03475.0024476.9692480.9462481.9405 483.929486.9118
489.8945491.8831494.8658497.8486499.8372500.8314503.8142506.7787511.6589512.6349
 514.587516.5391518.4911520.4432521.4193523.3713524.3474525.3234527.2755529.2275
531.1796532.1556533.1317535.0837538.9879540.9399 541.916544.8441545.8371548.8161
 552.788 555.767 559.739 561.725 564.704 567.683 568.676 571.655 573.641 575.627
576.6199578.6059582.5779587.5429592.5079593.5009597.4729599.4589600.4569602.4529
 603.451 604.449 606.445608.4411610.4371611.4352613.4312616.4253617.4233619.4193
621.4154622.4134624.4095625.4075626.4055627.3839629.3406632.2757635.2108636.1891
638.1458639.1242640.1026642.0593644.9944645.9727646.9511648.9078649.8862651.8429
655.7563659.6698663.6408665.6263 666.619669.5973676.5465677.5392680.5175681.5102
683.4957687.4667691.4377694.4159697.3942700.3724703.3506704.3434705.3362709.3071
712.2854715.2717716.2672 718.258721.2443725.2261728.2124729.2078731.1987732.1942
733.1896736.1759737.1713740.1576745.1348746.1302748.1211752.1028754.0938755.0892
757.0801760.0663761.0618764.0481 766.039774.9979776.9888 781.966783.9568786.9432
787.9386 788.934790.9167794.8821796.8647804.7954806.7781808.7607810.7434812.7261
814.7087816.6915819.6655820.6568821.6481822.6395823.6308825.6135827.5961828.5875
830.5701832.5528833.5441836.5182837.5095841.4749844.4489845.4402847.4229850.3969
852.3795855.3535858.3276859.3189861.3016865.2669867.2496868.2409870.2236872.2062
873.1976876.1794 882.174885.1714886.1705889.1678 891.166894.1634897.1607898.1599
901.1572903.1554907.1519908.1509  909.15912.1474914.1456915.1447917.1429925.1359
927.1341929.1323932.1296934.1279936.1261937.1252939.1234940.1225943.1199945.1181
947.1163954.0981955.0913963.0366967.0092970.9819973.9613974.9545976.9408979.9203
981.9066986.8773989.8715991.8676992.8657993.8638995.8599 997.8561001.8481004.843
1006.8391009.8331012.8271016.8191019.8131020.8121023.8061025.802  1026.81029.794
1030.7921033.7861035.7821037.7791041.7711043.7671045.7631046.7611048.7571050.754
 1052.75 1057.741059.736 1062.731067.7211071.7131072.7111077.7011079.6971081.693
 1083.691084.6881086.6841089.6781095.6661096.6651097.6631099.6591104.6491105.647
1108.6411112.634 1114.631116.626 1119.621121.6161123.6121126.6061128.6031129.601
1131.5971134.5911136.5871140.5791143.5741146.5681151.5581153.5541154.5521156.548
1160.5411162.5371164.5331168.525 1171.521172.5171174.5141175.512 1176.511183.496
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BR Coef=-1 , 0 , 0 ,, 0 ,,,0.8,-1,,0,
WSPro=,,,, 1 ,,,, 0 ,,,, 0 ,,,,-1 ,-1 ,-1 , 0 , 0 , 0 , 0 , 0
Culvert=1,1.5,,134,0.024,0.9,1,2,3,78.431,349,77.839,432.5,Culvert #1  , 0 ,1
     349   432.5
BC Culvert Barrel=1,Barrel 1,0
Culvert Bottom n=0.024
BC Design=,, 0 ,, 0 ,,,,,,
BC Use User HTab Curves=0
BC User HTab FreeFlow(D)= 0

Type RM Length L Ch R = 1 ,2.3516  ,21.57,23.16,24.6
BEGIN DESCRIPTION:
DS of Cromer Avenue Culvert - CB47A (SEM 2019)
END DESCRIPTION:
XS GIS Cut Line= 6
  598814.8208036 5422283.3137831  598463.9485036 5422471.2181831
  598439.3462036 5422475.7369831  598428.4321036 5422480.3671831
  598396.7289036 5422512.8974831  598380.5929036 5422540.9687831
#Sta/Elev= 30
       0   90.09    7.98   89.91   13.97   88.33   32.92   88.25   42.89   87.04
   93.77   87.14   98.76   86.45   122.7      86  127.69   85.62  133.67   83.53
  184.55   84.83  213.47   84.94  290.28   83.76  315.22   83.09  318.22    82.2
   326.2   82.42  344.15   81.45  351.13   82.53  362.11   82.93   416.3   83.07
  423.03   82.52  424.02   82.18  424.61   81.13   432.3   77.93   441.8    79.9
  444.76   81.15  447.73   81.94  475.37   81.91  482.31    84.7  512.69   83.35
#Mann= 3 , 0 , 0
       0     .06       0  424.61     .04       0  444.76     .06       0
Bank Sta=424.61,444.76
XS Rating Curve= 0 ,0
Exp/Cntr=0.3,0.1

Type RM Length L Ch R = 1 ,2.3284  ,54.28,51.41,47.74
BEGIN DESCRIPTION:
CB47 (SEM 2019)
END DESCRIPTION:
XS GIS Cut Line= 6
  598806.8833036 5422270.0844831  598466.1847036 5422457.5424831
  598445.1671036 5422458.3405831  598430.6150036 5422457.0176831
  598403.7920036 5422461.4068831  598368.7474036 5422524.4549831
#Sta/Elev= 30
       0    89.6   29.99   88.58   33.99   87.43   91.97   87.16   96.97   86.32
  121.96   85.85  126.96   84.19  137.95   84.22  141.95   83.55  179.94   84.77
  246.91   84.66   303.9   83.29  309.89   82.12  361.88   81.14  373.87   82.88
  393.65   83.65  411.85   83.08  419.64   78.84  423.09    77.7  424.36   78.55
  434.22   78.35  441.98   83.23  449.75   82.87  458.68   85.02  463.67   82.33
  500.62   81.82  506.61    83.4  514.59   87.59  518.88   85.99  523.82   86.09
#Mann= 3 , 0 , 0
       0     .06       0  411.85     .04       0  441.98     .06       0
Bank Sta=411.85,441.98
XS Rating Curve= 0 ,0
Exp/Cntr=0.3,0.1

Type RM Length L Ch R = 1 ,2.2770  ,109.14,107.44,105.29
BEGIN DESCRIPTION:
CB46 (SEM 2019)
END DESCRIPTION:
XS GIS Cut Line= 6
  598748.6748036 5422228.8094831  598437.9404036 5422382.6762831
  598410.4405036 5422410.7154831  598403.1644036 5422420.3066831
  598385.6653036 5422445.4461831  598349.5527036 5422514.4237831
#Sta/Elev= 30
       0   87.86   50.96   87.04   58.96   85.86   89.93   86.11  106.92   84.94
  147.89   83.89  191.86   83.87  202.85   84.35  236.83   83.76  255.81   84.37
  281.79   83.85  309.77   84.15  316.77   83.05  323.76   82.92  329.76   82.11
  342.75   81.99  360.49   78.69  387.87   76.81  394.28   75.74  401.02   76.87
  405.96      77  413.87   82.57  419.79   83.14  443.68   80.84  481.66   80.49
  495.65   79.22  498.65   79.57  499.65   82.13  500.65   82.59  506.55   82.16
#Mann= 3 , 0 , 0
       0     .06       0  387.87     .04       0  401.02     .06       0
Bank Sta=387.87,401.02
XS Rating Curve= 0 ,0
Exp/Cntr=0.3,0.1

Type RM Length L Ch R = 1 ,2.1696  ,140.3,140.79,140.92
BEGIN DESCRIPTION:
CB45 (SEM 2019)
END DESCRIPTION:
XS GIS Cut Line= 4
598319.4898035985422302.89758309598304.6069035995422412.36908309
598304.6069035995422441.47338309598284.1017035985422472.23118309
#Sta/Elev= 30
       0   77.94   13.93   77.78   23.89   77.33   28.86   77.54   37.82   77.37
   39.81   77.59   59.72   76.99   70.67   77.03   80.62   76.73   82.61      77
   87.59   76.43   90.57   76.82  104.51   77.49  107.49   77.98  112.29   77.25
   113.5    77.3  114.59   76.76   117.1   76.28  118.27   75.89  124.17   75.63
  126.62   76.07     136   77.21  139.58   77.32  140.58   77.75  146.58   77.66
  151.57   78.45  153.57    79.5  156.57   80.41  158.57   80.64  176.55    80.4
#Mann= 3 , 0 , 0
       0     .12       0   117.1     .04       0  126.62     .12       0
Bank Sta=117.1,126.62
XS Rating Curve= 0 ,0
Exp/Cntr=0.3,0.1

Type RM Length L Ch R = 1 ,2.0288  ,109.29,107.77,103.25
BEGIN DESCRIPTION:
CB44 (SEM 2019)
END DESCRIPTION:
XS GIS Cut Line= 5
598267.9260035995422274.58248309598169.9077035985422412.66408309
598168.0155035985422436.18168309598166.3618035985422454.37178309
598165.3697035985422493.06718309
#Sta/Elev= 30
       0   77.81   90.64   76.81   96.62   76.96   99.61    78.1   101.6   77.85
  103.59   76.77  105.58   77.47  109.57   76.48  119.53   76.73  125.51   76.27
  133.48    77.3  143.44   75.41  159.37   76.61  163.36   78.36  165.35   78.62
   171.3   78.25   177.2   77.01  180.15    75.9  186.05    75.4  192.87   75.58
  200.52   74.71  202.88   74.99  204.06   75.74  205.39   75.79  208.33   77.37
  212.19   78.14   223.1   78.43  226.08   78.05  235.01   78.89   249.9    78.7
#Mann= 3 , 0 , 0
       0     .06       0  192.87     .04       0  204.06     .06       0
Bank Sta=192.87,204.06
XS Rating Curve= 0 ,0
Exp/Cntr=0.3,0.1