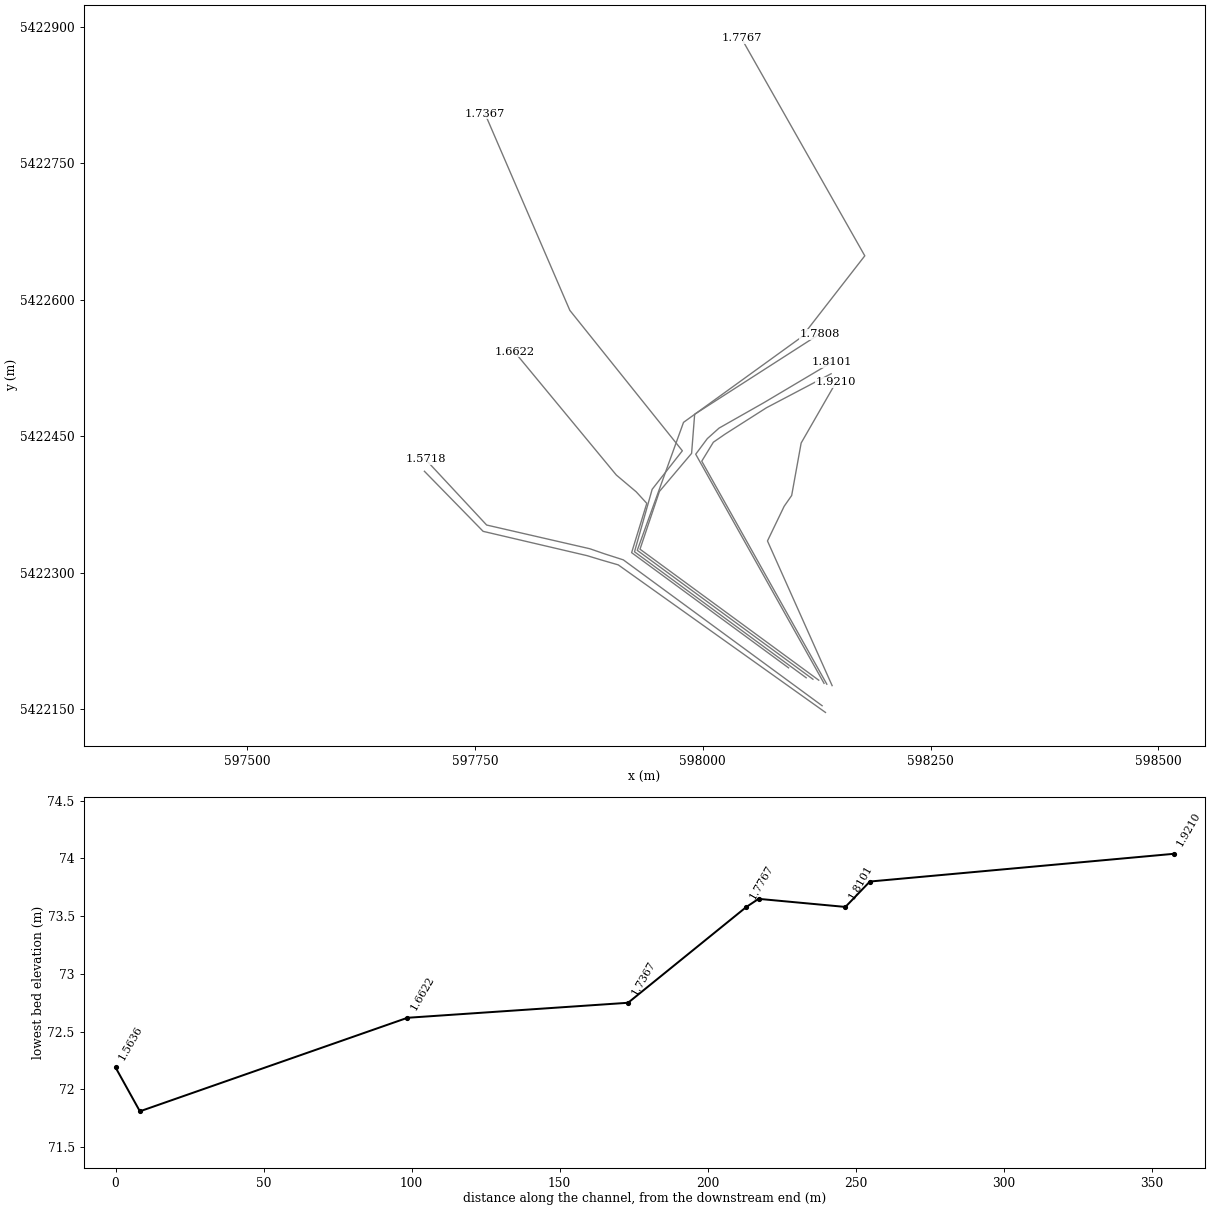
HEC-RAS study Exploits_FMM.prj: Exploits_FMM

--- Exploits_FMM.g01 (geometry) --- (continued)

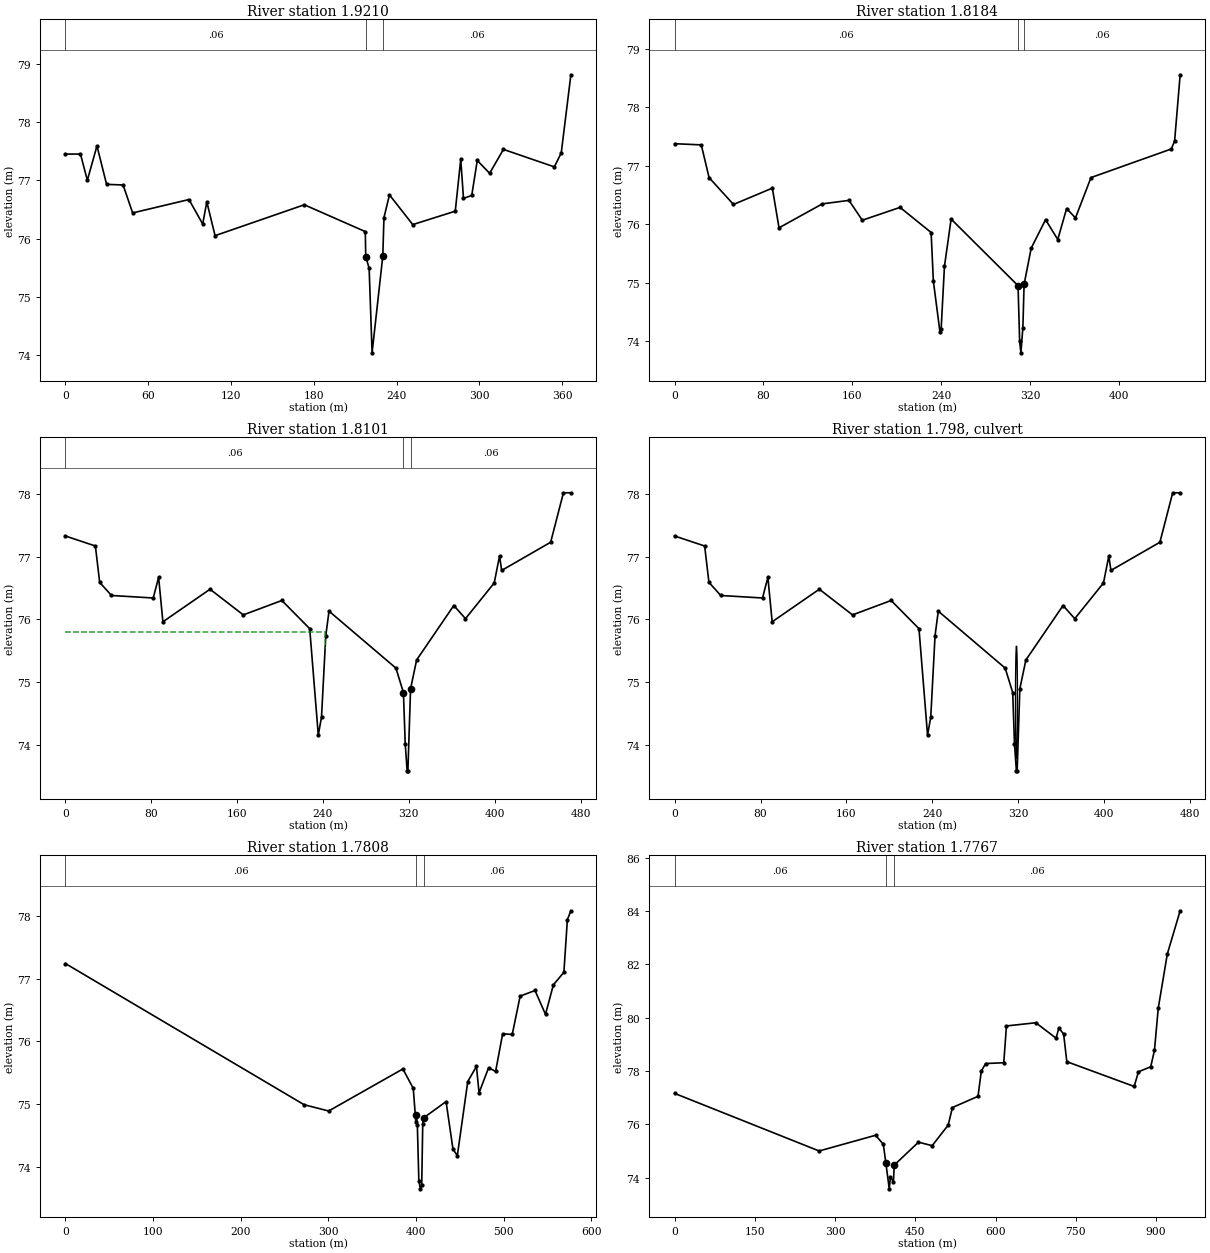
Type RM Length L Ch R = 1 ,1.9210  ,103.73,102.63,101.07
BEGIN DESCRIPTION:
CB43 (SEM 2019)
END DESCRIPTION:
XS GIS Cut Line= 6
598141.9840035985422175.89268309598071.0043035985422334.94178309
598089.3018035985422373.01228309598097.5700035985422384.91858309
598107.9798035985422442.61798309598146.2174035985422509.26838309
#Sta/Elev= 30
       0   77.45   10.95   77.45   15.92      77   22.89   77.59   29.86   76.93
    41.8   76.92   48.77   76.44   89.57   76.67   99.52   76.25  102.51   76.63
  108.48   76.05  173.17   76.58  217.37   76.12   217.7   75.69  220.16   75.49
  222.29   74.04  230.05    75.7   230.9   76.36  234.88   76.75  251.77   76.24
  282.58   76.47  286.55   77.36  288.54   76.69  294.52   76.74  298.52   77.34
   307.5   77.12  317.48   77.53   354.4   77.23  359.39   77.47  366.37   78.81
#Mann= 3 , 0 , 0
       0     .06       0   217.7     .04       0  230.05     .06       0
Bank Sta=217.7,230.05
XS Rating Curve= 0 ,0
Exp/Cntr=0.3,0.1

Type RM Length L Ch R = 1 ,1.8184  ,7.84,8.26,8.68
BEGIN DESCRIPTION:
CB42 (SEM 2019)
END DESCRIPTION:
XS GIS Cut Line= 6
598136.1632035985422177.48018309597998.8662035995422422.63288309
598011.5803035985422443.45768309598024.4788035985422452.38738309
598069.8827035995422481.36228309598140.9257035985422518.79338309
#Sta/Elev= 30
       0   77.38      24   77.36      31    76.8      53   76.34   87.99   76.62
   93.99   75.94  132.99   76.35  156.99   76.41  168.99   76.07  202.99   76.29
  230.98   75.86  232.98   75.03  238.98   74.15  239.98    74.2  242.98   75.28
  248.98   76.09  309.25   74.95  310.69      74  311.81    73.8   313.6   74.23
  314.69   74.97  321.07   75.59  334.04   76.08  345.01   75.74  352.99   76.27
  360.97   76.11  374.93    76.8   447.3   77.29  450.27   77.43  455.23   78.56
#Mann= 3 , 0 , 0
       0     .06       0  309.25     .04       0  314.69     .06       0
Bank Sta=309.25,314.69
XS Rating Curve= 0 ,0
Exp/Cntr=0.3,0.1

Type RM Length L Ch R = 1 ,1.8101  ,28.7,29.33,29.9
BEGIN DESCRIPTION:
US of Duggan Street 2 Culvert - CB41 (SEM 2019)
END DESCRIPTION:
XS GIS Cut Line= 6
598133.0940035985422178.43268309597992.2276035995422430.28798309
598004.9657035985422447.42648309598017.8642035985422459.00198309
598066.9365035985422486.87738309598141.9840035985422531.49338309
#Sta/Elev= 30
       0   77.33   27.96   77.17   31.95   76.59   42.94   76.38   81.88   76.34
   86.87   76.67   90.87   75.96   134.8   76.48  165.75   76.07   201.7    76.3
  227.66   75.85  235.65   74.15  238.65   74.44  242.64   75.74  245.64   76.13
  307.99   75.22  314.98   74.83  316.65   74.01  318.43   73.58  319.14   73.58
  321.63   74.89  327.26   75.35  361.91   76.22   372.8   76.01  399.57   76.58
  404.53   77.01  406.51   76.78  452.15   77.23  464.06   78.02     471   78.02
#Mann= 3 , 0 , 0
       0     .06       0  314.98     .04       0  321.63     .06       0
#XS Ineff= 2 , 0
             242    75.8
Permanent Ineff=
       T       F
Bank Sta=314.98,321.63
XS Rating Curve= 0 ,0
Exp/Cntr=0.3,0.1

Type RM Length L Ch R = 2 ,1.798   ,,,
Node Photo=.\Photos\CB-CR-10.JPG
BEGIN DESCRIPTION:
Duggan Street 2 Culvert
END DESCRIPTION:
Node Name=CB-CR-10
Bridge Culvert--1,0,-1,-1, 0
Deck Dist Width WeirC Skew NumUp NumDn MinLoCord MaxHiCord MaxSubmerge Is_Ogee
5,13,1.4,0, 400, 400, , , 0.98, 0, 3,3,,
     -87-85.0058-83.0116-81.0174-79.0232-78.0261-76.0319-75.0348-73.0406-72.0435
-69.0522 -67.058-64.0667-63.0696-61.0754-60.0783-56.0899-53.0986-51.1044-50.1073
-48.1131 -47.116-45.1218-44.1247-41.1334-40.1363-39.1392-37.1451-35.1509-33.1567
-31.1625-30.1654-28.1712-27.1741-24.1828-22.1886-21.1915-19.1973-18.2002-17.2031
 -16.206-14.2118-13.2147-12.2176-9.22636-8.22926-6.23506-4.24087-3.24377-2.24667
-1.24957 -.25247  .74463 2.73882 3.73592 4.73302 6.72721 8.72141 9.7185111.71271
 13.7069 15.7011 16.6982 18.6924 19.6895 20.6866 21.6837 22.6808 23.6745 24.6683
 25.6621 26.6558 28.6434 30.6309 32.6184 33.6122  34.606 36.5935 37.5873 41.5623
 45.5374 46.5311 48.5187 49.5124 52.4937 54.4813 56.4688 57.4626 58.4563 60.4439
 61.4376 62.4314 63.4252  68.394 71.3753  72.369 73.3628 74.3566 76.3441 79.3254
 81.3129 82.3067 83.3004 84.2942  85.288 86.2818 88.2693  89.263 90.2568 94.2319
 96.2194 99.2007100.1945105.1633109.1384111.1259112.1196114.1072115.1009116.0947
117.0885 119.076122.0573123.0511124.0448126.0323127.0261131.0012131.9949132.9887
136.9638137.9575138.9513139.9451141.9326144.9139145.9077148.8889150.8765153.8578
154.8515156.8391158.8266160.8223161.8201163.8157164.8136165.8114167.8071169.8027
171.7984174.7918175.7897176.7875177.7853178.7832 179.781180.7788182.7745184.7701
 185.768187.7636189.7593191.7549194.7484195.7462197.7419199.7376200.7354201.7332
 202.731203.7289204.7267206.7224207.7202 208.718211.7115212.7094213.7072 214.705
216.7007218.6963 220.692221.6898222.6876224.6833225.6811226.6789227.6768228.6746
229.6602230.6459231.6315232.6172233.6028234.5885235.5741236.5598237.5454238.5311
239.5167240.5023 241.488243.4593244.4449245.4306246.4162247.4019248.3875249.3732
250.3588251.3445252.3301253.3157254.3014 255.287256.2727257.2583 258.244259.2296
260.2153261.2009262.1866264.1579265.1435266.1292267.1148268.1004269.0861270.0717
 272.043273.0287274.0143     275275.9856276.9713277.9569278.9425279.9282 280.901
281.8737282.8465 284.792285.7648286.7375288.6831289.6559290.6286291.6014292.5741
293.5469295.4924296.4652 297.438299.3835300.3562 301.329302.3018303.2745305.2201
306.1928307.1916308.1903 309.189310.1877311.1864312.1852313.1839314.1826315.1813
316.1801317.1788318.1775319.1762 320.175321.1737322.1724323.1711324.1604325.1497
 326.139327.1283328.1176329.1069330.0963331.0855332.0749333.0641334.0535335.0428
 336.032337.0214338.0107339.9893340.9786341.9679342.9572344.9358345.9251347.9037
 348.893349.8823350.8622 351.842352.8218353.8017355.7614356.7412358.7009359.6807
360.6606361.6404362.6202363.6001364.5799365.5598366.5396367.5194368.4993369.4791
 370.459371.4388372.4186374.3783375.3582 376.338377.3178378.2977379.2775380.2574
381.2372 382.217383.1969384.1767388.0961390.0558391.0356392.0155392.9953394.9735
 395.972396.9704397.9688398.9672399.9656 400.964401.9624402.9608403.9592 405.956
406.9544408.9512409.9496413.9433415.9401416.9385417.9369418.9353419.9337421.9305
423.9273424.9257426.9225428.9194429.9178430.9161 432.913433.9114434.9098435.9082
436.9066438.9034440.9002441.8986 442.897445.8923446.8906  447.89448.8892450.8878
 451.887453.8856455.8842457.8828460.8806461.8798463.8784464.8777466.8762468.8748
469.8741470.8734472.8719473.8712474.8705477.8683479.8669480.8661481.8654482.8647
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       0   1.994   3.988   5.983   7.977   8.974  10.968  11.965  13.959  14.956
  17.948  19.942  22.933   23.93  25.925  26.922   30.91  33.901  35.896  36.893
  38.887  39.884  41.878  42.875  45.867  46.864  47.861  49.855  51.849  53.843
  55.837  56.835  58.829  59.826  62.817  64.811  65.808  67.803    68.8  69.797
  70.794  72.788  73.785  74.782  77.774  78.771  80.765  82.759  83.756  84.753
   85.75  86.748  87.745  89.739  90.736  91.733  93.727  95.721  96.719  98.713
 100.707 102.701 103.698 105.692  106.69 107.687 108.684 109.681 110.675 111.668
 112.662 113.656 115.643 117.631 119.618 120.612 121.606 123.594 124.587 128.562
 132.537 133.531 135.519 136.512 139.494 141.481 143.469 144.463 145.456 147.444
 148.438 149.431 150.425 155.394 158.375 159.369 160.363 161.357 163.344 166.325
 168.313 169.307   170.3 171.294 172.288 173.282 175.269 176.263 177.257 181.232
 183.219 186.201 187.195 192.163 196.138 198.126  199.12 201.107 202.101 203.095
 204.089 206.076 209.057 210.051 211.045 213.032 214.026 218.001 218.995 219.989
 223.964 224.958 225.951 226.945 228.933 231.914 232.908 235.889 237.877 240.858
 241.852 243.839 245.827 247.822  248.82 250.816 251.814 252.811 254.807 256.803
 258.798 261.792  262.79 263.788 264.785 265.783 266.781 267.779 269.775  271.77
 272.768 274.764 276.759 278.755 281.748 282.746 284.742 286.738 287.735 288.733
 289.731 290.729 291.727 293.722  294.72 295.718 298.712 299.709 300.707 301.705
 303.701 305.696 307.692  308.69 309.688 311.683 312.681 313.679 314.677 315.675
  316.66 317.646 318.632 319.617 320.603 321.589 322.574  323.56 324.545 325.531
 326.517 327.502 328.488 330.459 331.445 332.431 333.416 334.402 335.388 336.373
 337.359 338.345  339.33 340.316 341.301 342.287 343.273 344.258 345.244  346.23
 347.215 348.201 349.187 351.158 352.144 353.129 354.115   355.1 356.086 357.072
 359.043 360.029 361.014     362 362.986 363.971 364.957 365.943 366.928 367.901
 368.874 369.847 371.792 372.765 373.738 375.683 376.656 377.629 378.601 379.574
 380.547 382.492 383.465 384.438 386.384 387.356 388.329 389.302 390.275  392.22
 393.193 394.192  395.19 396.189 397.188 398.186 399.185 400.184 401.183 402.181
  403.18 404.179 405.178 406.176 407.175 408.174 409.172 410.171  411.16  412.15
 413.139 414.128 415.118 416.107 417.096 418.086 419.075 420.064 421.054 422.043
 423.032 424.021 425.011 426.989 427.979 428.968 429.957 431.936 432.925 434.904
 435.893 436.882 437.862 438.842 439.822 440.802 442.761 443.741 445.701 446.681
 447.661  448.64  449.62   450.6  451.58  452.56  453.54 454.519 455.499 456.479
 457.459 458.439 459.419 461.378 462.358 463.338 464.318 465.298 466.278 467.257
 468.237 469.217 470.197 471.177 475.096 477.056 478.036 479.016 479.995 481.974
 482.972  483.97 484.969 485.967 486.966 487.964 488.962 489.961 490.959 492.956
 493.954 495.951  496.95 500.943  502.94 503.939 504.937 505.935 506.934 508.931
 510.927 511.926 513.923 515.919 516.918 517.916 519.913 520.911  521.91 522.908
 523.907 525.903   527.9 528.899 529.897 532.892 533.891  534.89 535.889 537.888
 538.887 540.886 542.884 544.883 547.881  548.88 550.878 551.878 553.876 555.875
 556.874 557.873 559.872 560.871 561.871 564.868 566.867 567.866 568.865 569.865
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BR Coef=-1 , 0 , 0 ,, 0 ,,,0.8,-1,,0,
WSPro=,,,, 1 ,,,, 0 ,,,, 0 ,,,,-1 ,-1 ,-1 , 0 , 0 , 0 , 0 , 0
Culvert=1,1.8,,23.8,0.024,0,1,2,3,73.775,318.5,73.569,405,Culvert #1  , 0 ,1.5
   318.5     405
BC Culvert Barrel=1,Barrel 1,0
Culvert Bottom n=0.024
BC Design=,, 0 ,, 0 ,,,,,,
BC Use User HTab Curves=0
BC User HTab FreeFlow(D)= 0

Type RM Length L Ch R = 1 ,1.7808  ,4,4.12,4.1
BEGIN DESCRIPTION:
DS of Duggan Street 2 Culvert - CB40 (SEM 2019)
END DESCRIPTION:
XS GIS Cut Line= 6
  598127.2732036 5422181.8722831  597931.0840036 5422325.8893831
  597952.3565036 5422389.3101831  597987.7173036 5422431.2258831
  597991.0750036 5422474.2155831  598128.0669036 5422562.3438831
#Sta/Elev= 30
       0   77.24  272.33   74.99  300.28   74.89  384.96   75.56   396.8   75.25
  399.68   74.72  400.39   74.83  401.46   74.66  403.15   73.78  404.89   73.65
  406.42   73.71   407.6   74.68  408.55   74.78   434.2   75.04  442.12   74.28
  447.07   74.18  458.96   75.36  468.86    75.6  471.83   75.18  482.75   75.58
  490.73   75.52  498.72   76.12  509.69   76.11  518.68   76.72  535.64   76.81
  547.62   76.43   556.6    76.9  568.58    77.1  572.57   77.94  576.56   78.08
#Mann= 3 , 0 , 0
       0     .06       0  400.39     .04       0  408.55     .06       0
Bank Sta=400.39,408.55
XS Rating Curve= 0 ,0
Exp/Cntr=0.3,0.1

Type RM Length L Ch R = 1 ,1.7767  ,36.56,39.97,45.4
BEGIN DESCRIPTION:
CB39 (SEM 2019)
END DESCRIPTION:
XS GIS Cut Line= 6
  598120.9232036 5422182.9305831  597928.0678036 5422324.6193831
  597978.8380036 5422465.2858831  598108.6602036 5422559.2667831
  598177.8398036 5422648.3882831  598042.4330036 5422887.5253831
#Sta/Elev= 30
       0   77.16  270.11      75  375.72   75.59  390.14   75.25  394.97   74.54
  401.22   73.58  403.37   74.01  409.02   73.85  410.52   74.47  455.83   75.33
   481.5    75.2  511.38   75.97  519.34   76.63  567.14   77.05  573.39      78
  581.38   78.28  615.32   78.31  620.32   79.69  675.23   79.81  713.21   79.23
   718.2   79.61   727.2   79.39  733.19   78.35  859.11   77.42   867.1   77.97
  890.09   78.16  897.08   78.78  904.08   80.35  921.07   82.39  945.05   84.01
#Mann= 3 , 0 , 0
       0     .06       0  394.97     .04       0  410.52     .06       0
Bank Sta=394.97,410.52
XS Rating Curve= 0 ,0
Exp/Cntr=0.3,0.1

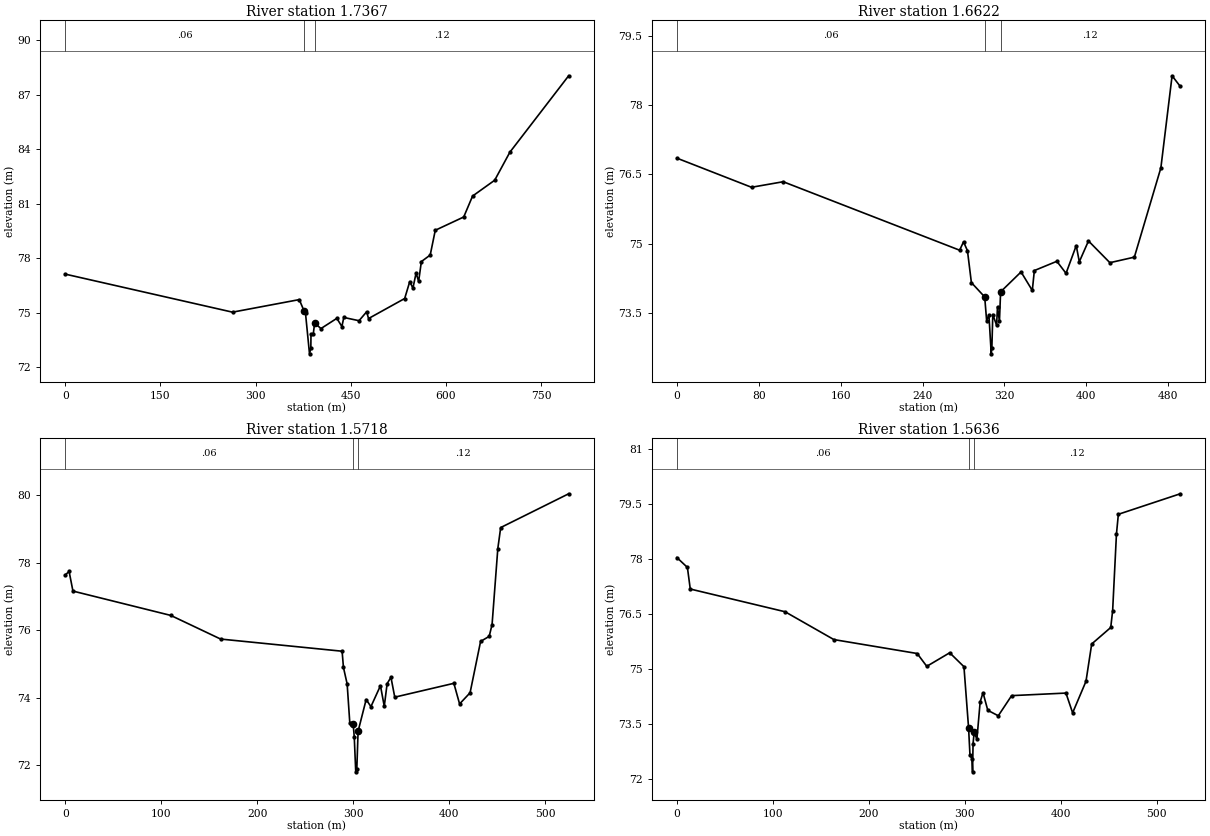
Type RM Length L Ch R = 1 ,1.7367  ,72.93,74.53,73.28
BEGIN DESCRIPTION:
CB38 (SEM 2019)
END DESCRIPTION:
XS GIS Cut Line= 6
  598113.5148036 5422184.5180831  597925.0515036 5422323.0318831
  597944.4190036 5422391.6913831  597977.5650036 5422434.0527831
  597854.0535036 5422588.4321831  597761.0024036 5422804.3840831
#Sta/Elev= 30
       0   77.13  263.61   75.04  368.82   75.73  376.62   75.09  378.68   74.97
  384.97   72.75  387.06   73.07   387.3   73.82  390.89   73.84  393.04   74.44
  403.04   74.14  428.03    74.7  436.02   74.25  439.02   74.75  463.01   74.57
  475.01   75.06  478.01   74.69  534.98   75.79  542.98   76.72  547.97   76.36
  552.97   77.19  556.97   76.73  561.28   77.82  575.23   78.18   583.2   79.54
  628.04   80.27  641.99   81.42  676.86   82.29  700.78   83.83  793.44   88.03
#Mann= 3 , 0 , 0
       0     .06       0  376.62     .04       0  393.04     .12       0
Bank Sta=376.62,393.04
XS Rating Curve= 0 ,0
Exp/Cntr=0.3,0.1

Type RM Length L Ch R = 1 ,1.6622  ,89.74,90.38,91.64
BEGIN DESCRIPTION:
CB37 (SEM 2019)
END DESCRIPTION:
XS GIS Cut Line= 6
  598094.1470036 5422195.4495831  597921.8765036 5422322.0793831
  597938.5288036 5422376.2708831  597926.8710036 5422388.9844831
  597905.0853036 5422407.4081831  597793.3683036 5422542.7646831
#Sta/Elev= 30
       0   76.85   72.93   76.22   103.9   76.34  276.25   74.86  280.08   75.04
  283.91   74.85  287.75   74.16  300.75   73.85  302.64   73.34  304.88   73.46
  307.14   72.62  307.76   72.75  308.67   73.47  312.37   73.24  313.27   73.64
  315.16   73.32   316.3   73.96  336.28   74.39  347.27   73.99  349.27   74.42
  371.24   74.62  380.23   74.36   390.2   74.96  393.19   74.61  402.15   75.06
  423.07   74.59  446.98   74.71  472.88   76.64  483.84   78.63  491.81    78.4
#Mann= 3 , 0 , 0
       0     .06       0  300.75     .04       0   316.3     .12       0
Bank Sta=300.75,316.3
XS Rating Curve= 0 ,0
Exp/Cntr=0.3,0.1

Type RM Length L Ch R = 1 ,1.5718  ,7.97,8.23,8.18
BEGIN DESCRIPTION:
CB36 (SEM 2019)
END DESCRIPTION:
XS GIS Cut Line= 6
598130.9774035985422153.82638309597912.7666035985422314.15108309
597892.1868035985422320.75698309597875.9811035985422326.37938309
597762.7183035985422352.44538309597695.4723035985422424.76028309
#Sta/Elev= 30
       0   77.64       4   77.74    7.99   77.16  109.91   76.44  161.87   75.74
  288.46   75.38  289.86    74.9  293.72   74.41  296.47   73.26  299.99   73.22
  301.11   72.85  302.67   71.81  303.77   71.88  305.11   73.01  313.52   73.95
  318.49   73.74  328.42   74.36  332.39   73.75  335.37   74.42  339.35   74.61
  343.32   74.02  404.91   74.43  410.87   73.82   421.8   74.15  432.75   75.67
  441.73   75.82  444.72   76.17  450.71   78.42   453.7   79.04  524.52   80.04
#Mann= 3 , 0 , 0
       0     .06       0  299.99     .04       0  305.11     .12       0
Bank Sta=299.99,305.11
XS Rating Curve= 0 ,0
Exp/Cntr=0.3,0.1

Type RM Length L Ch R = 1 ,1.5636  ,5.61,5.41,5.26
BEGIN DESCRIPTION:
US of Duggan Street 1 Bridge - CB35 (SEM 2019)
END DESCRIPTION:
XS GIS Cut Line= 6
598134.6815035995422146.41808309597907.2213035985422308.62528309
597888.2181035985422314.14238309597873.0045035985422318.77258309
597758.8748035985422345.49718309597694.4140035995422411.53108309
#Sta/Elev= 30
       0   78.04   10.98   77.77   13.97   77.18  112.75   76.56  163.63    75.8
  250.44   75.42  260.42   75.07  284.32   75.44  299.16   75.06  303.99   73.39
  305.42   72.66  307.51   72.54  308.13   72.19  308.66   72.96  309.82   73.27
  312.66   73.08  316.06    74.1  319.04   74.35     324   73.87  334.93   73.72
  348.84   74.27  405.46   74.34  412.41    73.8  426.32   74.66  432.28   75.68
  452.13   76.13  454.11   76.59  458.08   78.68  460.06   79.22  524.56   79.78
#Mann= 3 , 0 , 0
       0     .06       0  303.99     .04       0  309.82     .12       0
Bank Sta=303.99,309.82
XS Rating Curve= 0 ,0
Exp/Cntr=0.3,0.1