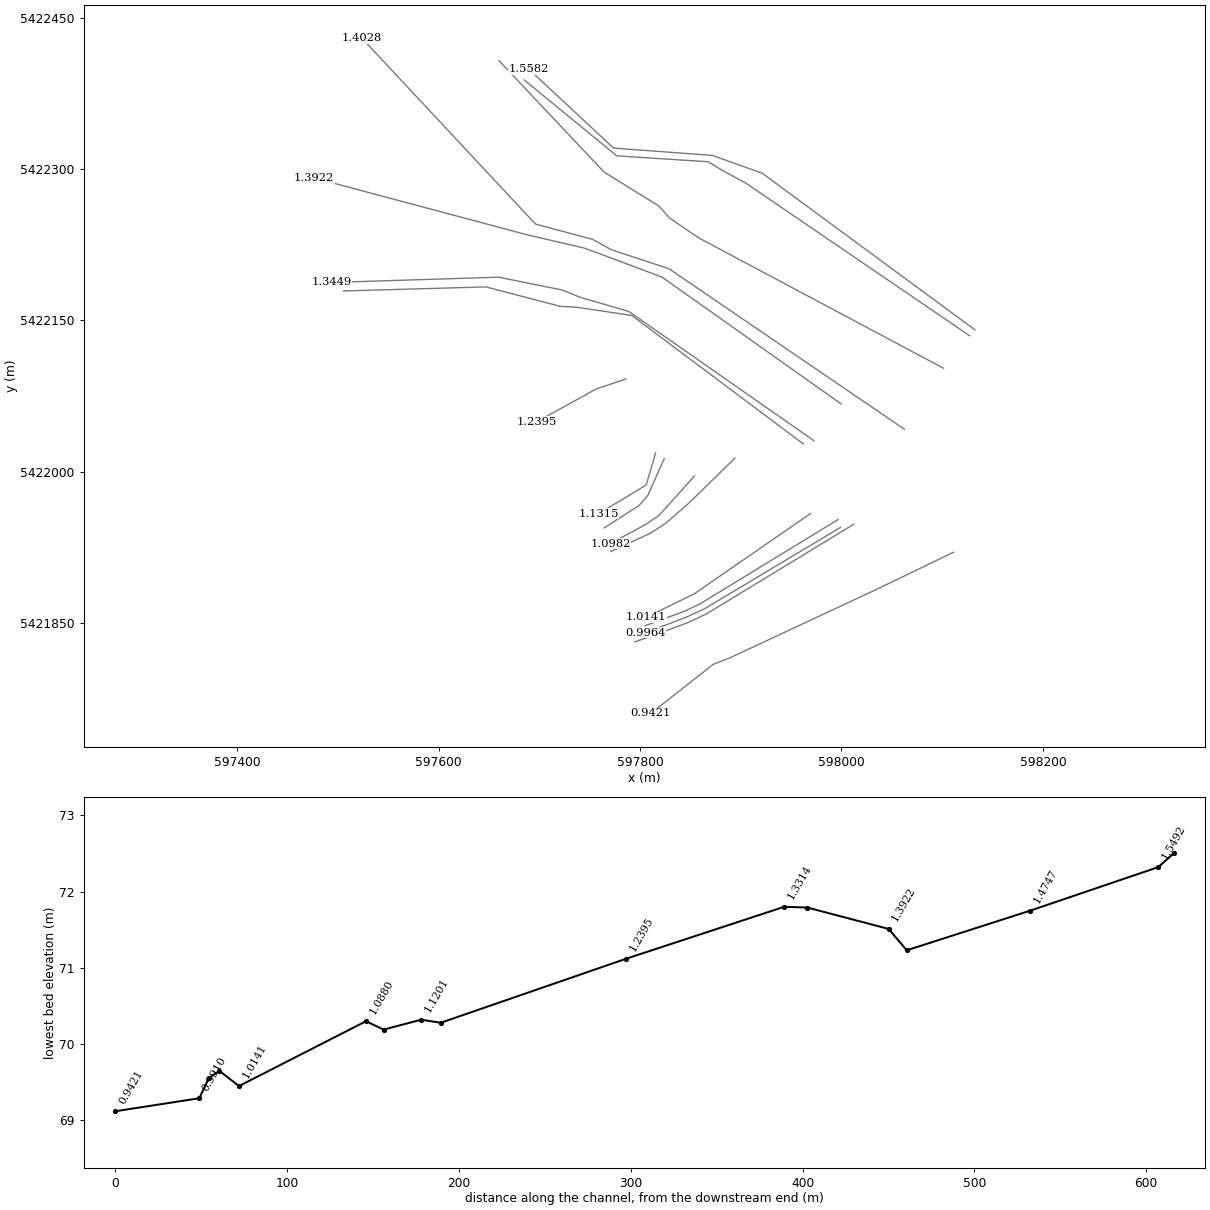
HEC-RAS study Exploits_FMM.prj: Exploits_FMM

--- Exploits_FMM.g01 (geometry) --- (continued)

Type RM Length L Ch R = 3 ,1.561   ,,,
Node Photo=.\Photos\CB-CR-9.JPG
BEGIN DESCRIPTION:
Duggan Street 1 Bridge
END DESCRIPTION:
Node Name=CB-CR-9
Bridge Culvert--1,0,-1,-1, 0
Deck Dist Width WeirC Skew NumUp NumDn MinLoCord MaxHiCord MaxSubmerge Is_Ogee
1.9,1.7,1.4,0, 400, 400, , , 0.98, 0, 3,3,,
       0.99706131.9941233.9882455.9823686.9794298.9735529.97061310.9676711.96474
 12.961813.9588614.9559215.95298 17.947120.9382921.9353522.9324124.9265326.92065
27.9177229.91184 30.908932.9030235.8942136.8912737.8883340.8795142.87363 43.8707
44.8677645.8648247.85894  48.85651.8471953.8413154.8383756.8324957.8295660.82074
 61.817862.8148663.8119264.8089867.8001768.7972371.7884173.7825375.7766676.77372
78.76784 79.764982.7560985.7472786.7443388.7384689.7355190.73257 92.726793.72376
95.7178897.7120198.70907100.7032101.7002102.6973103.6944104.6914106.6856109.6767
112.6679 113.665115.6591116.6562120.6444123.6356125.6297126.6268128.6209 130.615
133.6062134.6033135.6003136.5974137.5945138.5915139.5886141.5827142.5798143.5768
144.5739 146.568147.5651148.5621151.5533152.5504153.5474155.5416156.5386159.5298
161.5239163.5181165.5122169.5004171.4945172.4916173.4887175.4828176.4798 178.474
 179.471181.4651182.4622183.4593184.4563186.4505188.4446189.4417191.4358193.4299
 195.424197.4181198.4152199.4123203.4005204.3976205.3946207.3887208.3858209.3829
210.3799 211.377212.3741214.3682215.3652218.3564221.3476222.3447224.3388225.3358
  227.33229.3241230.3212231.3182232.3153236.3035237.3006238.2977240.2918 243.283
  244.28246.2741247.2712248.2683249.2653250.2624251.2594252.2565253.2536254.2506
256.2448257.2418258.2389259.2359 260.233  261.23262.2271264.1692265.1141266.0591
267.9491 268.894 269.839 271.729 272.674273.6189274.5639275.5089277.3988281.2821
283.2755284.2722285.2688287.2622288.2588289.2555290.2522293.2422294.2389296.2322
297.2289298.2255299.2222300.2189301.2155302.2122303.2089304.2056305.2022306.1989
307.1956308.1922309.1889310.1856311.1823312.1789313.1756314.1723315.1644316.1566
317.1487318.1408 319.133320.1252321.1173322.1094323.1016325.0859 326.078327.0702
329.0545330.0466332.0309334.0194335.0158336.0123337.0087338.0051339.0015339.9979
340.9943341.9907343.9835344.9799345.9763347.9691348.9655349.9619350.9583351.9547
 352.951353.9474354.9438355.9402356.9366 357.933358.9294359.9258360.9222361.9186
 362.915363.9114364.9078365.9042366.9006 367.897368.8935369.8899370.8863371.8827
372.8791373.8755374.8719375.8683376.8647378.8575379.8539380.8503 382.843383.8394
384.8358385.8322386.8286 387.825388.8214389.8178390.8142 392.807393.8034394.7998
395.7962396.7926 397.789398.7854399.7818400.7783402.7711403.7675404.7639405.7603
406.7567408.7495409.7458410.7422411.7386412.7151413.6916 414.668415.6445416.6209
417.5974418.5738419.5503420.5267421.5032422.4796423.4561424.4326 425.409426.3855
427.3619428.3384429.3148430.2913431.2678432.2442433.2207434.1971435.1736  436.15
437.1265438.1029439.0997440.0965441.0932  442.09443.0868444.0836445.0803446.0771
447.0739448.0706449.0674450.0642451.0609452.0577453.0545454.0512 455.048456.0448
457.0416458.0383459.0351460.0319461.0286462.0254463.0222 464.019465.0157467.0092
 468.006469.0028469.9995470.9963471.9931472.9899473.9866475.9802476.9769477.9737
478.9705479.9673 480.964481.9608482.9576483.9543484.9511485.9479486.9446487.9414
489.9349490.9317491.9285492.9253494.9188495.9156496.9123497.9091498.9059499.9026
500.8994501.8962503.8897504.8865  506.88507.8768509.8703511.8639512.8607514.8542
 515.851516.8477518.8412520.8348521.8315523.8251524.8219525.8187526.8154527.8122
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                                                  73.99473.8943373.79467  73.695
73.5953373.49567  73.39673.2963373.19666  73.097
       0.99706131.9941233.9882455.9823686.9794298.9735529.97061310.9676711.96474
 12.961813.9588614.9559215.95298 17.947120.9382921.9353522.9324124.9265326.92065
27.9177229.91184 30.908932.9030235.8942136.8912737.8883340.8795142.87363 43.8707
44.8677645.8648247.85894  48.85651.8471953.8413154.8383756.8324957.8295660.82074
 61.817862.8148663.8119264.8089867.8001768.7972371.7884173.7825375.7766676.77372
78.76784 79.764982.7560985.7472786.7443388.7384689.7355190.73257 92.726793.72376
95.7178897.7120198.70907100.7032101.7002102.6973103.6944104.6914106.6856109.6767
112.6679 113.665115.6591116.6562120.6444123.6356125.6297126.6268128.6209 130.615
133.6062134.6033135.6003136.5974137.5945138.5915139.5886141.5827142.5798143.5768
144.5739 146.568147.5651148.5621151.5533152.5504153.5474155.5416156.5386159.5298
161.5239163.5181165.5122169.5004171.4945172.4916173.4887175.4828176.4798 178.474
 179.471181.4651182.4622183.4593184.4563186.4505188.4446189.4417191.4358193.4299
 195.424197.4181198.4152199.4123203.4005204.3976205.3946207.3887208.3858209.3829
210.3799 211.377212.3741214.3682215.3652218.3564221.3476222.3447224.3388225.3358
  227.33229.3241230.3212231.3182232.3153236.3035237.3006238.2977240.2918 243.283
  244.28246.2741247.2712248.2683249.2653250.2624251.2594252.2565253.2536254.2506
256.2448257.2418258.2389259.2359 260.233  261.23262.2271264.1692265.1141266.0591
267.9491 268.894 269.839 271.729 272.674273.6189274.5639275.5089277.3988281.2821
283.2755284.2722285.2688287.2622288.2588289.2555290.2522293.2422294.2389296.2322
297.2289298.2255299.2222300.2189301.2155302.2122303.2089304.2056305.2022306.1989
307.1956308.1922309.1889310.1856311.1823312.1789313.1756314.1723315.1644316.1566
317.1487318.1408 319.133320.1252321.1173322.1094323.1016325.0859 326.078327.0702
329.0545330.0466332.0309334.0194335.0158336.0123337.0087338.0051339.0015339.9979
340.9943341.9907343.9835344.9799345.9763347.9691348.9655349.9619350.9583351.9547
 352.951353.9474354.9438355.9402356.9366 357.933358.9294359.9258360.9222361.9186
 362.915363.9114364.9078365.9042366.9006 367.897368.8935369.8899370.8863371.8827
372.8791373.8755374.8719375.8683376.8647378.8575379.8539380.8503 382.843383.8394
384.8358385.8322386.8286 387.825388.8214389.8178390.8142 392.807393.8034394.7998
395.7962396.7926 397.789398.7854399.7818400.7783402.7711403.7675404.7639405.7603
406.7567408.7495409.7458410.7422411.7386412.7151413.6916 414.668415.6445416.6209
417.5974418.5738419.5503420.5267421.5032422.4796423.4561424.4326 425.409426.3855
427.3619428.3384429.3148430.2913431.2678432.2442433.2207434.1971435.1736  436.15
437.1265438.1029439.0997440.0965441.0932  442.09443.0868444.0836445.0803446.0771
447.0739448.0706449.0674450.0642451.0609452.0577453.0545454.0512 455.048456.0448
457.0416458.0383459.0351460.0319461.0286462.0254463.0222 464.019465.0157467.0092
 468.006469.0028469.9995470.9963471.9931472.9899473.9866475.9802476.9769477.9737
478.9705479.9673 480.964481.9608482.9576483.9543484.9511485.9479486.9446487.9414
489.9349490.9317491.9285492.9253494.9188495.9156496.9123497.9091498.9059499.9026
500.8994501.8962503.8897504.8865  506.88507.8768509.8703511.8639512.8607514.8542
 515.851516.8477518.8412520.8348521.8315523.8251524.8219525.8187526.8154527.8122
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                                                  73.99373.8985573.8041273.70966
73.6152273.5207873.4263373.3318973.23743  73.143
BR Coef=-1 , 0 , 0 ,, 0 ,,,0.8,-1,,0,
WSPro=,,,, 1 ,,,, 0 ,,,, 0 ,,,,-1 ,-1 ,-1 , 0 , 0 , 0 , 0 , 0
BC Design=,, 0 ,, 0 ,,,,,,
BC Use User HTab Curves=0
BC User HTab FreeFlow(D)= 0

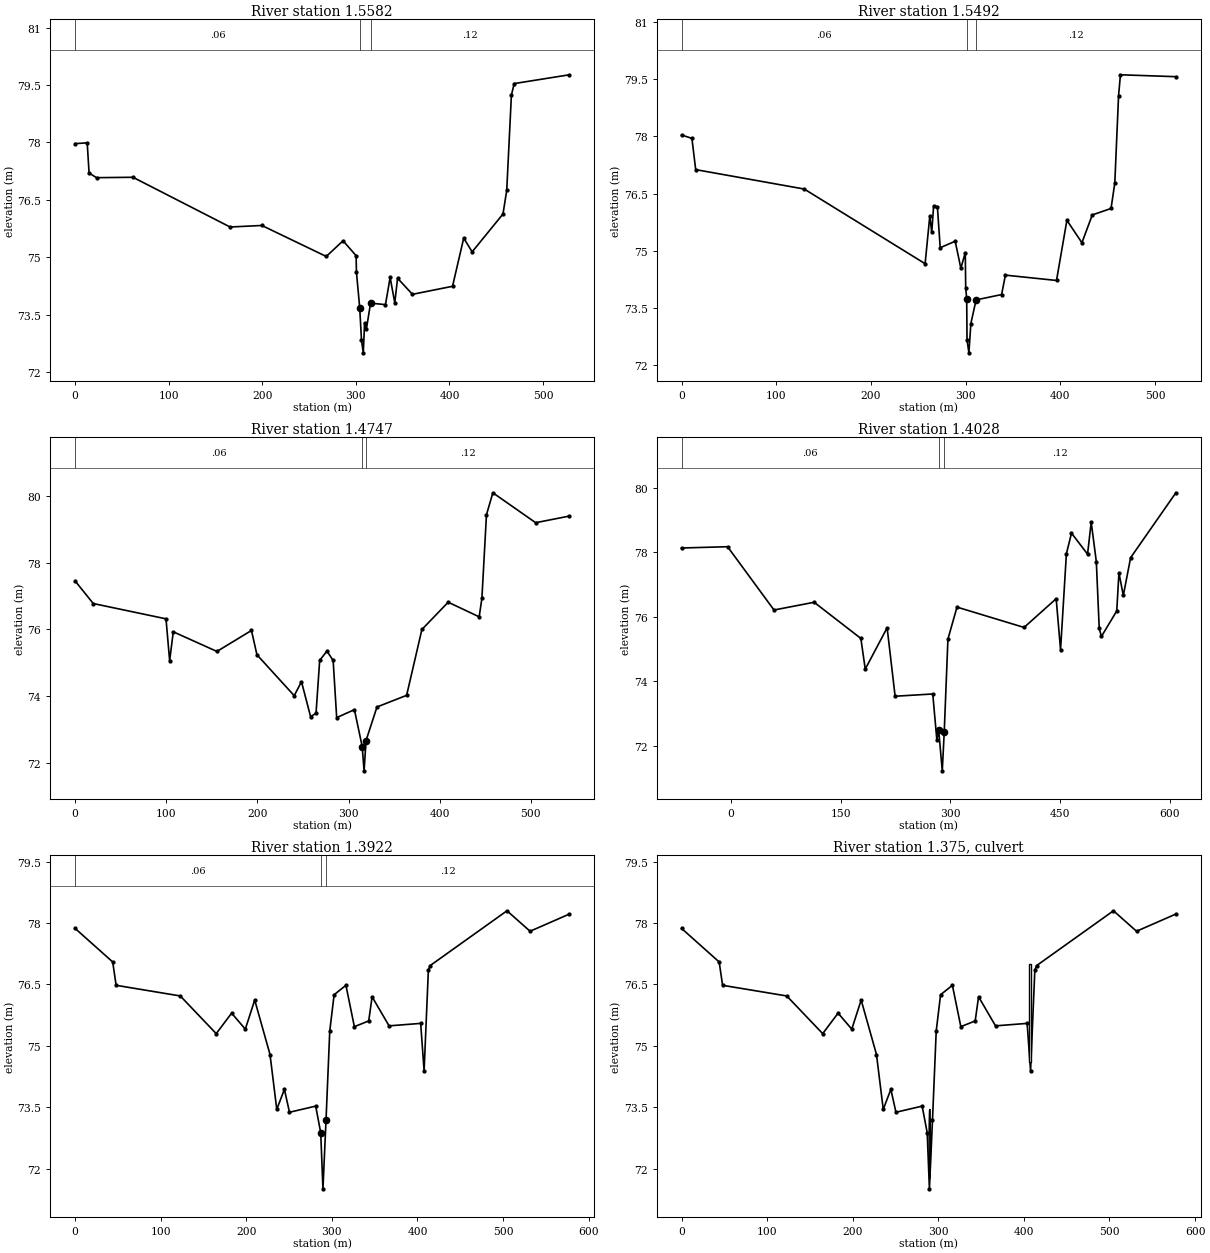
Type RM Length L Ch R = 1 ,1.5582  ,9.77,8.97,8.55
BEGIN DESCRIPTION:
DS of Duggan Street 1 Bridge - CB34 (SEM 2019)
END DESCRIPTION:
XS GIS Cut Line= 6
598132.5649035985422140.59718309597921.2741035995422296.17388309
597885.5722035985422308.85068309597872.0123035985422313.81158309
597773.7526035985422321.07838309597689.6515035985422399.36018309
#Sta/Elev= 30
       0   77.97   12.97   77.99   14.97    77.2   22.95   77.08   61.86   77.09
  165.61   75.79  199.54   75.83  268.37   75.02  286.32   75.43  300.27   75.04
  300.62   74.61  304.11   73.68  306.02   72.83  307.95    72.5   309.3   73.28
  311.31   73.13  315.71    73.8  331.63   73.76  336.61   74.47  341.58   73.81
  344.57   74.45  360.49   74.03  403.29   74.24  415.24    75.5  424.23   75.14
   457.2   76.13   461.2   76.75  466.19   79.24  469.19   79.54  528.14   79.77
#Mann= 3 , 0 , 0
       0     .06       0  304.11     .04       0  315.71     .12       0
Bank Sta=304.11,315.71
XS Rating Curve= 0 ,0
Exp/Cntr=0.3,0.1

Type RM Length L Ch R = 1 ,1.5492  ,74.43,74.48,72.29
BEGIN DESCRIPTION:
CB33 (SEM 2019)
END DESCRIPTION:
XS GIS Cut Line= 6
598127.2732035985422134.77638309597904.9276035995422286.39508309
597882.2649035985422298.59808309597867.7128035985422307.52778309
597776.9466035985422313.36268309597684.8890035985422388.77688309
#Sta/Elev= 30
       0   78.04   10.96   77.95   14.95   77.13  129.58   76.62  257.16   74.66
  262.14   75.92  264.14   75.48  266.13   76.17  270.11   76.16  273.08   75.08
  288.92   75.25   294.9   74.54  299.57   74.95  300.01   74.03  301.07   73.73
  301.41   72.66  303.39   72.32  305.47   73.09  310.98   73.71  337.92   73.85
  341.92   74.36  395.89   74.22  406.85    75.8  422.72   75.21  433.63   75.94
  453.46   76.11  457.43   76.78   461.4   79.07  463.38   79.62  521.89   79.57
#Mann= 3 , 0 , 0
       0     .06       0  301.07     .04       0  310.98     .12       0
Bank Sta=301.07,310.98
XS Rating Curve= 0 ,0
Exp/Cntr=0.3,0.1

Type RM Length L Ch R = 1 ,1.4747  ,70.15,71.93,74.91
BEGIN DESCRIPTION:
CB32 (SEM 2019)
END DESCRIPTION:
XS GIS Cut Line= 6
598101.3440035985422102.49708309597858.3039035985422231.91988309
597829.3482035995422251.63438309597818.7648035995422263.54068309
597764.3118035985422297.30768309597660.0181035995422407.82688309
#Sta/Elev= 30
       0   77.46   19.95   76.78   99.77   76.32  103.76   75.06  107.75   75.93
  155.63   75.34  193.54   75.97  199.53   75.24  240.43   74.01  248.42   74.43
  258.39   73.38  264.38   73.48  268.37   75.07  276.33   75.35  283.14   75.07
  287.03   73.35  306.49   73.59  315.03   72.48  317.09   71.75  319.23   72.66
  331.24   73.67  363.77   74.02  380.53      76  409.38   76.82  443.37   76.38
  446.37   76.94  451.37   79.45  458.37   80.11  505.36   79.21  542.35   79.41
#Mann= 3 , 0 , 0
       0     .06       0  315.03     .04       0  319.23     .12       0
Bank Sta=315.03,319.23
XS Rating Curve= 0 ,0
Exp/Cntr=0.3,0.1

Type RM Length L Ch R = 1 ,1.4028  ,10.14,10.54,10.96
BEGIN DESCRIPTION:
CB31 (SEM 2019)
END DESCRIPTION:
XS GIS Cut Line= 6
  598062.5414036 5422041.9152831  597828.7769036 5422201.3128831
  597771.4704036 5422220.2150831  597752.9496036 5422230.4676831
  597696.2196036 5422245.6576831  597524.0220036 5422430.0519831
#Sta/Elev= 30
   -67.5   78.13-4.59999   78.17   58.85   76.21  113.71   76.45  177.55   75.33
  183.54   74.38  213.46   75.66  224.36   73.54   275.8   73.61  281.38   72.19
  283.91   72.49   288.8   71.23  291.49   72.44  296.54   75.31  308.91    76.3
  400.57   75.67  444.45   76.56  450.43   74.98  458.41   77.95  465.39   78.59
  487.33   77.94  492.32   78.93   499.3   77.71  503.29   75.64  506.28   75.39
  527.22   76.18  530.21   77.36   536.2   76.66  546.17   77.83     608   79.84
#Mann= 3 , 0 , 0
   -67.5     .06       0  283.91     .04       0  291.49     .12       0
Bank Sta=283.91,291.49
XS Rating Curve= 0 ,0
Exp/Cntr=0.3,0.1

Type RM Length L Ch R = 1 ,1.3922  ,47.43,47.3,47.07
BEGIN DESCRIPTION:
US of Corduroy Brook TCH Culvert - CB30 (SEM 2019)
END DESCRIPTION:
XS GIS Cut Line= 6
597999.7438035985422067.04288309597821.9299035995422192.94898309
597760.8871035995422215.91558309597744.3506035985422221.86878309
597686.7203035985422235.30588309597476.3969035995422291.40998309
#Sta/Elev= 30
       0   77.87   43.97   77.05   47.97   76.48  122.93   76.22  164.91    75.3
   182.9    75.8  198.89   75.41  209.88   76.12  227.76   74.79  235.66   73.45
  244.56   73.94  250.49   73.38  281.12   73.53  287.01   72.88   289.6   71.51
  293.18   73.18  297.54   75.36  302.64   76.25  316.45   76.48  326.31   75.47
  343.08   75.61  347.03    76.2  366.84   75.49  403.78   75.55  407.78   74.39
  412.77   76.85  414.77   76.96  504.63    78.3  531.59    77.8  577.53   78.22
#Mann= 3 , 0 , 0
       0     .06       0  287.01     .04       0  293.18     .12       0
#XS Ineff= 2 , 0
       0                     304       0    75.9
Permanent Ineff=
       F       F
Bank Sta=287.01,293.18
XS Rating Curve= 0 ,0
Exp/Cntr=0.3,0.1

Type RM Length L Ch R = 2 ,1.375   ,,,
Node Photo=.\Photos\CB-CR-8.JPG
BEGIN DESCRIPTION:
Corduroy Brook TCH Culvert
END DESCRIPTION:
Node Name=CB-CR-8
Bridge Culvert--1,0,-1,-1, 0
Deck Dist Width WeirC Skew NumUp NumDn MinLoCord MaxHiCord MaxSubmerge Is_Ogee
9,18,1.4,0, 400, 400, , , 0.98, 0, 3,3,,
       01.9952425.9857266.98334710.9738312.9690714.9643221.94766 23.942925.93815
26.9357728.9310130.9262532.9214935.9143636.9119838.9072241.9000844.8929446.88819
47.8858148.8834350.8786753.8715454.8691657.8620258.85964 61.852562.8501265.84299
66.8406168.8358572.82633 75.819277.8144479.8096882.8025484.7977885.7768288.71391
89.6929593.6090795.56714 97.525298.5042399.48326101.4413103.3994105.3575108.2945
109.2736111.2316113.1897115.1478117.1058118.0849119.0639120.0429 122.001 123.964
124.9455127.8899130.8344134.7604135.7419137.7048139.6678140.6493142.6123143.5938
144.5753145.5568 146.547147.5372152.4882153.4784155.4589157.4393158.4295159.4197
161.4001162.3903163.3805165.3609167.3414168.3316  170.31172.2865173.2747175.2512
177.2276181.1806182.1688 183.157185.1335186.1217  187.11188.0982189.0865191.0629
192.0511193.0394194.0276195.0159196.9923197.9805199.9426200.9164201.8902 202.864
203.8378205.7854206.7592 207.733208.7068209.6806210.6544211.6282 212.602213.5757
215.5233216.4971217.4709219.4368220.4288223.4049224.3969225.3889 226.381 228.365
230.3491233.3252235.3092236.3013238.2853239.2774240.2694241.2614244.2375245.2295
246.2216 247.217248.2125249.2079250.2034251.1989252.1943253.1898254.1852255.1807
257.1716259.1625 260.158261.1535262.1489263.1444264.1399265.1353266.1308268.1217
269.0956270.0695271.0435272.0174272.9913273.9652274.9391275.9131 276.887277.8609
278.8348279.8087280.7827281.7566282.7305284.6784285.6523286.6262287.6001 288.574
 289.548290.5219291.4958292.4774293.4589294.4405296.4036297.3851299.3483301.3114
302.2929303.2745 304.256305.2376306.2191307.2007308.1823309.1638310.1454311.1269
312.1085  313.09314.0716315.0531317.0162317.9978318.9793319.9609320.9468321.9328
322.9187323.9046324.8906325.8765326.8624327.8483329.8202330.8061331.7921 332.778
333.7639335.7358336.7217337.7076338.6936339.6795340.6659341.6523342.6387343.6251
344.6115345.5978346.5842347.5706 348.557349.5434350.5298351.5162352.5026 353.489
354.4753355.4617356.4481357.4345359.4073360.3937361.3857362.3776363.3695364.3615
365.3535366.3454369.3213371.3052372.2971 374.281 375.273378.2488379.2408381.2247
382.2166383.2086385.1729386.1551388.1195389.1017390.0838 391.066393.0303394.0125
394.9947395.9844396.9741397.9638398.9535 400.933401.9227403.9021404.8918406.8712
407.8609410.8301411.8198413.7992414.7889415.7786417.7581419.7375420.7272422.7066
423.6963 424.686425.6758426.6655428.6449429.6346430.6243 431.614433.5723435.5094
437.4466439.3837442.2894444.2266445.1951446.1637448.1009449.0694451.0066452.9437
453.9123454.8808455.8494457.7865458.7551 460.748462.7409463.7374465.7303468.7197
470.7126472.7055 473.702476.6913477.6878479.6807480.6772481.6736482.6701 484.663
489.6453490.6418493.6311496.6205499.6099501.6028502.5993504.5922506.5851508.5769
512.5583513.5536515.5444516.5397519.5258522.5118523.5071524.5025525.4979526.4932
527.4886528.4839529.4792530.4746532.4653 534.456535.4514536.4467537.4421539.4327
540.4281543.4142545.4048546.4002548.3909549.3863550.3817 551.377552.3723 554.363
555.3584557.3491559.3398561.3305562.3258563.3212565.3094567.2975570.2798 571.274
572.2681573.2621574.2562575.2504577.2385579.2267 581.215 582.209585.1913587.1795
588.1736591.1559593.1441594.1382595.1323598.1146600.1028601.0969 602.091605.0733
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       01.9952425.9857266.98334710.9738312.9690714.9643221.94766 23.942925.93815
26.9357728.9310130.9262532.9214935.9143636.9119838.9072241.9000844.8929446.88819
47.8858148.8834350.8786753.8715454.8691657.8620258.85964 61.852562.8501265.84299
66.8406168.8358572.82633 75.819277.8144479.8096882.8025484.7977885.7768288.71391
89.6929593.6090795.56714 97.525298.5042399.48326101.4413103.3994105.3575108.2945
109.2736111.2316113.1897115.1478117.1058118.0849119.0639120.0429 122.001 123.964
124.9455127.8899130.8344134.7604135.7419137.7048139.6678140.6493142.6123143.5938
144.5753145.5568 146.547147.5372152.4882153.4784155.4589157.4393158.4295159.4197
161.4001162.3903163.3805165.3609167.3414168.3316  170.31172.2865173.2747175.2512
177.2276181.1806182.1688 183.157185.1335186.1217  187.11188.0982189.0865191.0629
192.0511193.0394194.0276195.0159196.9923197.9805199.9426200.9164201.8902 202.864
203.8378205.7854206.7592 207.733208.7068209.6806210.6544211.6282 212.602213.5757
215.5233216.4971217.4709219.4368220.4288223.4049224.3969225.3889 226.381 228.365
230.3491233.3252235.3092236.3013238.2853239.2774240.2694241.2614244.2375245.2295
246.2216 247.217248.2125249.2079250.2034251.1989252.1943253.1898254.1852255.1807
257.1716259.1625 260.158261.1535262.1489263.1444264.1399265.1353266.1308268.1217
269.0956270.0695271.0435272.0174272.9913273.9652274.9391275.9131 276.887277.8609
278.8348279.8087280.7827281.7566282.7305284.6784285.6523286.6262287.6001 288.574
 289.548290.5219291.4958292.4774293.4589294.4405296.4036297.3851299.3483301.3114
302.2929303.2745 304.256305.2376306.2191307.2007308.1823309.1638310.1454311.1269
312.1085  313.09314.0716315.0531317.0162317.9978318.9793319.9609320.9468321.9328
322.9187323.9046324.8906325.8765326.8624327.8483329.8202330.8061331.7921 332.778
333.7639335.7358336.7217337.7076338.6936339.6795340.6659341.6523342.6387343.6251
344.6115345.5978346.5842347.5706 348.557349.5434350.5298351.5162352.5026 353.489
354.4753355.4617356.4481357.4345359.4073360.3937361.3857362.3776363.3695364.3615
365.3535366.3454369.3213371.3052372.2971 374.281 375.273378.2488379.2408381.2247
382.2166383.2086385.1729386.1551388.1195389.1017390.0838 391.066393.0303394.0125
394.9947395.9844396.9741397.9638398.9535 400.933401.9227403.9021404.8918406.8712
407.8609410.8301411.8198413.7992414.7889415.7786417.7581419.7375420.7272422.7066
423.6963 424.686425.6758426.6655428.6449429.6346430.6243 431.614433.5723435.5094
437.4466439.3837442.2894444.2266445.1951446.1637448.1009449.0694451.0066452.9437
453.9123454.8808455.8494457.7865458.7551 460.748462.7409463.7374465.7303468.7197
470.7126472.7055 473.702476.6913477.6878479.6807480.6772481.6736482.6701 484.663
489.6453490.6418493.6311496.6205499.6099501.6028502.5993504.5922506.5851508.5769
512.5583513.5536515.5444516.5397519.5258522.5118523.5071524.5025525.4979526.4932
527.4886528.4839529.4792530.4746532.4653 534.456535.4514536.4467537.4421539.4327
540.4281543.4142545.4048546.4002548.3909549.3863550.3817 551.377552.3723 554.363
555.3584557.3491559.3398561.3305562.3258563.3212565.3094567.2975570.2798 571.274
572.2681573.2621574.2562575.2504577.2385579.2267 581.215 582.209585.1913587.1795
588.1736591.1559593.1441594.1382595.1323598.1146600.1028601.0969 602.091605.0733
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BR Coef=-1 , 0 , 0 ,, 0 ,,,0.8,-1,,0,
WSPro=,,,, 1 ,,,, 0 ,,,, 0 ,,,,-1 ,-1 ,-1 , 0 , 0 , 0 , 0 , 0
Culvert=1,1.7,,45.2,0.024,0.9,1,2,3,71.76,290,71.735,286,Culvert #1  , 0 ,1
     290     286
BC Culvert Barrel=1,Barrel 1,0
Culvert Bottom n=0.024
Culvert=2,2.4,2.4,37,0.012,0.5,1,10,1,74.6,407,72.7,342,Culvert #2  , 0 ,10
     407     342
BC Culvert Barrel=1,Underpass,0
Culvert Bottom n=0.012
BC Design=,, 0 ,, 0 ,,,,,,
BC Use User HTab Curves=0
BC User HTab FreeFlow(D)= 0

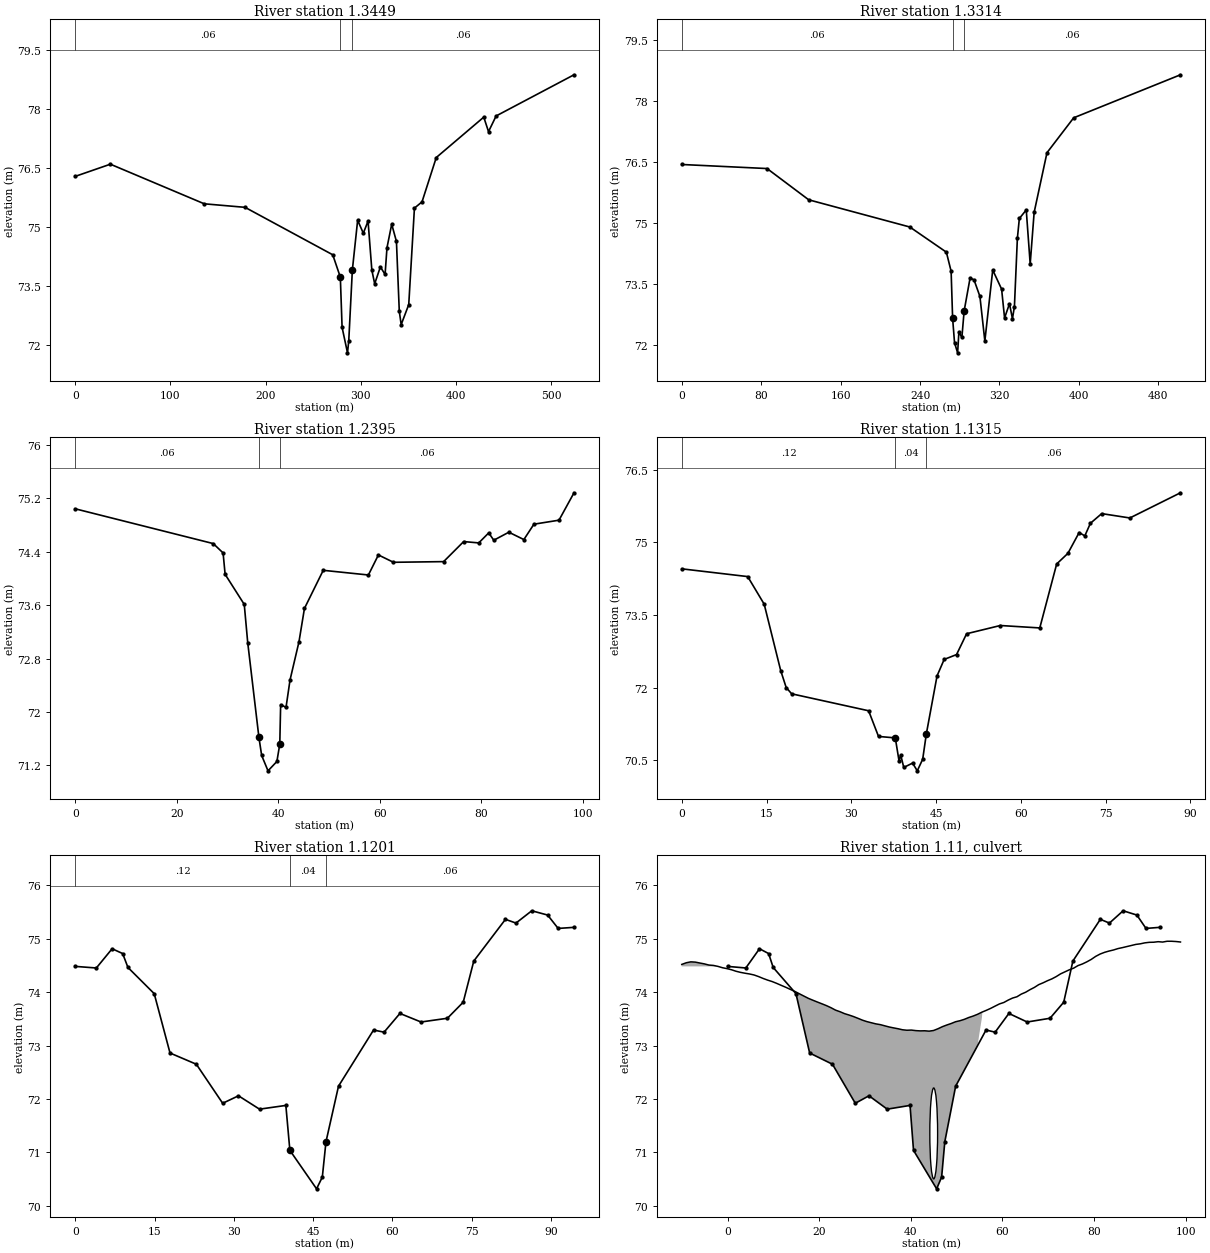
Type RM Length L Ch R = 1 ,1.3449  ,12.2,13.5,15.07
BEGIN DESCRIPTION:
DS of Corduroy Brook TCH Culvert - CB29 (SEM 2019)
END DESCRIPTION:
XS GIS Cut Line= 6
597972.7562035985422030.53028309597788.9141035985422158.89058309
597739.7204035995422173.25148309597722.8531035995422180.19678309
597659.4787035985422192.93378309597493.8594035985422187.69308309
#Sta/Elev= 30
       0   76.29   36.87    76.6  135.53   75.59  178.38    75.5  270.54   74.29
   278.5   73.72  280.35   72.44  286.03   71.79  287.37    72.1  291.13    73.9
  296.69   75.17  302.66   74.84  307.63   75.15  311.61    73.9  314.59   73.55
  320.56   73.98  325.53   73.79  327.52   74.47  332.49   75.07  337.46   74.63
  340.45   72.85  342.44   72.51  350.39   73.02  356.36   75.48  364.34   75.64
  379.31   76.77  429.22    77.8  434.21   77.43   442.2   77.83  524.05   78.88
#Mann= 3 , 0 , 0
       0     .06       0   278.5     .04       0  291.13     .06       0
Bank Sta=278.5,291.13
XS Rating Curve= 0 ,0
Exp/Cntr=0.3,0.1

Type RM Length L Ch R = 1 ,1.3314  ,89.94,91.92,93.38
BEGIN DESCRIPTION:
CB28 (SEM 2019)
END DESCRIPTION:
XS GIS Cut Line= 6
597962.1729035985422027.35528309597791.8657035995422154.92418309
597737.7360035985422162.99878309597720.8688035985422163.99098309
597646.8797035985422183.27878309597505.5011035995422179.22648309
#Sta/Elev= 30
       0   76.44   85.91   76.34  127.87   75.57   229.7    74.9  266.52   74.28
   271.3   73.81  272.81   72.65  274.74   72.05  277.84    71.8  279.13   72.31
  282.14   72.18  284.41   72.83  290.37   73.64  294.34    73.6   300.3   73.19
  305.27   72.09  313.21   73.84  322.15   73.37  325.13   72.66  330.09   73.01
  333.07   72.64  335.06   72.94  338.03   74.62  340.02   75.11  346.97   75.32
  350.94   73.99  354.92   75.26  367.85   76.73  394.74   77.59  502.31   78.65
#Mann= 3 , 0 , 0
       0     .06       0  272.81     .04       0  284.41     .06       0
Bank Sta=272.81,284.41
XS Rating Curve= 0 ,0
Exp/Cntr=0.3,0.1

Type RM Length L Ch R = 1 ,1.2395  ,107.9,107.99,107.99
BEGIN DESCRIPTION:
CB27 (SEM 2019)
END DESCRIPTION:
XS GIS Cut Line= 3
597786.0225035995422091.89188309597756.5876035985422081.96998309
597697.7177035995422049.55848309
#Sta/Elev= 30
       0   75.04   27.18   74.52   29.12   74.38   29.52   74.06   33.29   73.61
   33.97   73.04   36.18   71.62   36.72   71.35   37.97   71.12   39.72   71.26
   40.29   71.52   40.46   72.11   41.52   72.07   42.31   72.48   44.07   73.05
   45.15   73.55   48.85   74.12   57.75   74.05   59.72   74.35   62.69   74.24
   72.57   74.25   76.52   74.55   79.49   74.53   81.46   74.68   82.45   74.57
   85.42   74.69   88.38   74.58   90.36   74.81    95.3   74.87   98.26   75.28
#Mann= 3 , 0 , 0
       0     .06       0   36.18     .04       0   40.29     .06       0
Bank Sta=36.18,40.29
XS Rating Curve= 0 ,0
Exp/Cntr=0.3,0.1

Type RM Length L Ch R = 1 ,1.1315  ,10.36,11.41,12.53
BEGIN DESCRIPTION:
CB26 (SEM 2019)
END DESCRIPTION:
XS GIS Cut Line= 4
597815.4575035985422018.46988309597806.1971035985421986.71978309
597792.3064035985421978.12088309597758.9027035985421958.27708309
#Sta/Elev= 30
       0   74.45   11.67   74.29   14.59   73.72   17.51   72.35   18.48      72
   19.45   71.87   33.07   71.52   34.82   70.99   37.79   70.96   38.46   70.48
   38.74   70.61   39.29   70.35   40.85   70.44   41.68   70.28   42.64   70.52
   43.28   71.04   45.18   72.24   46.44   72.58   48.63   72.68   50.41   73.11
   56.38   73.28   63.36   73.23   66.35   74.55   68.34   74.77   70.33    75.2
   71.33   75.13   72.32   75.39   74.32   75.59    79.3    75.5   88.26   76.02
#Mann= 3 , 0 , 0
       0     .12       0   37.79     .04       0   43.28     .06       0
Bank Sta=37.79,43.28
XS Rating Curve= 0 ,0
Exp/Cntr=0.3,0.1

Type RM Length L Ch R = 1 ,1.1201  ,22.78,21.89,20.73
BEGIN DESCRIPTION:
US of Corduroy Brook Lane Culvert - CB25 (SEM 2019)
END DESCRIPTION:
XS GIS Cut Line= 4
597824.0565035995422012.84748309597807.8507035985421976.46718309
597798.9210035985421966.21458309597764.5251035985421944.05568309
#Sta/Elev= 30
       0   74.48    3.98   74.45    6.97   74.81    8.96   74.72    9.96   74.46
   14.93   73.97   17.92   72.86    22.9   72.65   27.88   71.92   30.87   72.06
   34.85   71.81   39.83   71.88   40.59   71.04   45.64   70.32   46.73   70.54
   47.42    71.2   49.79   72.24   56.42   73.29   58.41   73.25   61.41    73.6
    65.4   73.44   70.39   73.51   73.38   73.81   75.38   74.58   81.37   75.36
   83.36   75.29   86.35   75.52   89.35   75.44   91.34   75.19   94.34   75.21
#Mann= 3 , 0 , 0
       0     .12       0   40.59     .04       0   47.42     .06       0
Bank Sta=40.59,47.42
XS Rating Curve= 0 ,0
Exp/Cntr=0.3,0.1

Type RM Length L Ch R = 2 ,1.11    ,,,
Node Photo=.\Photos\CB-CR-7.JPG
BEGIN DESCRIPTION:
Corduroy Brook Lane Culvert
END DESCRIPTION:
Node Name=CB-CR-7
Bridge Culvert--1,0,-1,-1, 0
Deck Dist Width WeirC Skew NumUp NumDn MinLoCord MaxHiCord MaxSubmerge Is_Ogee
3,11,1.4,0, 113, 113, , , 0.98, 0, 3,3,,
     -10  -9.013  -8.025  -7.038   -6.05  -5.063  -4.076  -3.088  -2.101  -1.113
   -.126    .862   1.849   2.836   3.824   4.811   5.799   6.786   7.773   8.761
   9.748  10.736  11.723  12.711  13.698  14.685  15.673   16.66  17.648  18.635
  19.622   20.61  21.597  22.585  23.572   24.56  25.547  26.534  27.522  28.491
   29.46  30.429  31.398  32.367  33.336  34.305  35.274  36.243  37.212  38.181
   39.15  40.119  41.088  42.057  43.026  43.995  44.964  45.933  46.902  47.859
  48.817  49.774  50.732  51.689  52.647  53.605  54.562   55.52  56.477  57.435
  58.393   59.35  60.308  61.265  62.217   63.17  64.122  65.074  66.026  66.978
   67.93  68.882  69.834  70.786  71.738   72.69  73.642  74.594  75.546  76.499
  77.451  78.403  79.377  80.352  81.326  82.301  83.275   84.25  85.224  86.199
  87.173  88.148  89.122  90.097  91.071  92.046   93.02  93.995  94.969  95.944
  96.918  97.893  98.867
  74.517  74.548  74.565   74.56  74.543  74.527  74.505  74.498   74.48  74.455
  74.438  74.417  74.389  74.368  74.352  74.338  74.319  74.289  74.254  74.223
  74.196  74.162  74.125  74.089   74.05  74.012  73.968  73.925  73.882  73.847
  73.813   73.78  73.746  73.707  73.662  73.632  73.596   73.57  73.541  73.508
  73.474  73.447  73.426  73.405  73.391  73.369  73.347   73.33  73.314  73.295
  73.286  73.289  73.279  73.274  73.276  73.269  73.281  73.314  73.353  73.384
  73.412  73.445  73.464   73.49  73.524  73.551  73.584  73.624  73.658  73.695
  73.737  73.778  73.805   73.85  73.888  73.912  73.962  73.997  74.045  74.087
  74.139  74.173  74.212  74.246  74.289   74.34  74.378  74.416  74.447  74.495
  74.525  74.564   74.61  74.667  74.711  74.743  74.767  74.787  74.813  74.831
  74.851  74.871  74.891  74.902   74.92   74.93  74.932  74.942  74.935   74.95
   74.95  74.945  74.936
       88.987415 9.9748310.9622411.9496612.9370713.9244914.9119115.8993216.88674
17.8741518.8615619.84898 20.836421.8238122.8112323.7986424.7860525.7734726.76089
 27.748328.7357229.7231330.7105431.6979632.6853833.6727934.6602135.6476236.63504
37.6224538.6098639.5972840.5846941.5721142.5595243.5469444.5343645.5217746.49076
47.4597448.4287349.3977250.36671 51.335752.3046853.2736754.2426655.2116556.18063
57.1496258.11861 59.087660.0565861.0255761.9945662.9635563.9325364.9015265.85912
 66.8167 67.774368.7318969.6894870.6470771.6046772.5622673.5198574.4774475.43504
76.3926377.3502278.30782 79.265480.2174881.1695582.1216283.0736984.0257684.97784
85.9299186.8819887.8340588.78613 89.738290.6902791.6423492.5944193.5464994.49856
95.45063 96.4027 97.377298.3517299.32623100.3007101.2752102.2497103.2243104.1988
105.1733106.1478107.1223108.0968109.0713110.0458111.0203111.9948112.9693113.9438
114.9184115.8929116.8674
 74.5165 74.5477 74.5654 74.5601  74.543 74.5265 74.5052 74.4975 74.4804 74.4548
 74.4381 74.4166 74.3888  74.368 74.3522 74.3381 74.3188 74.2887 74.2542 74.2231
 74.1958 74.1624 74.1251 74.0889 74.0503 74.0116 73.9681 73.9246 73.8821 73.8465
 73.8132 73.7804 73.7462 73.7066 73.6622 73.6318 73.5955 73.5702 73.5406 73.5079
  73.474  73.447  73.426 73.4047 73.3912 73.3691 73.3471 73.3295 73.3136 73.2946
 73.2858 73.2886  73.279 73.2741 73.2755 73.2687 73.2813 73.3143 73.3531 73.3844
 73.4124 73.4454  73.464 73.4896 73.5237 73.5505 73.5837 73.6241 73.6577 73.6952
  73.737 73.7775 73.8048 73.8503 73.8879 73.9122 73.9617 73.9965 74.0448 74.0869
 74.1392 74.1731  74.212 74.2462 74.2886 74.3397 74.3779 74.4159 74.4465 74.4948
 74.5247 74.5637 74.6099 74.6672 74.7109 74.7429 74.7673 74.7873 74.8129 74.8306
 74.8513 74.8707 74.8913 74.9023 74.9203 74.9298 74.9316 74.9421 74.9349 74.9503
 74.9498 74.9447 74.9355
BR Coef=-1 , 0 , 0 ,, 0 ,,,0.8,-1,,0,
WSPro=,,,, 1 ,,,, 0 ,,,, 0 ,,,,-1 ,-1 ,-1 , 0 , 0 , 0 , 0 , 0
Culvert=1,1.7,,13,0.024,0.9,1,2,3,70.506,45,70.655,61,Culvert #1  , 0 ,2
      45      61
BC Culvert Barrel=1,Barrel 1,0
Culvert Bottom n=0.024
BC Design=,, 0 ,, 0 ,,,,,,
BC Use User HTab Curves=0
BC User HTab FreeFlow(D)= 0

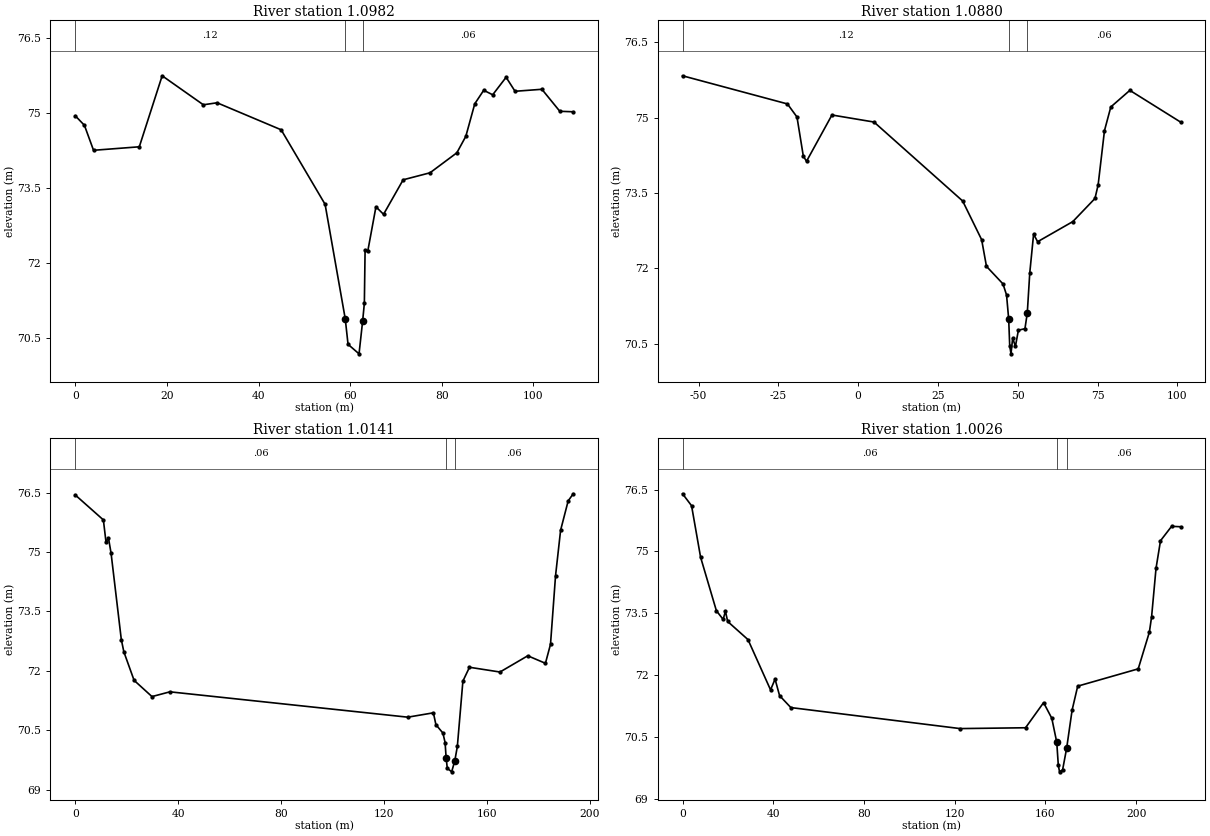
Type RM Length L Ch R = 1 ,1.0982  ,10.19,10.23,10.23
BEGIN DESCRIPTION:
DS of Corduroy Brook Lane Culvert - CB24 (SEM 2019)
END DESCRIPTION:
XS GIS Cut Line= 4
597854.1529035985421995.64958309597818.7648035995421956.29268309
597804.8741035985421947.03228309597770.4782035985421928.51138309
#Sta/Elev= 30
       0   74.95       2   74.76    3.99   74.26   13.98   74.33   18.97   75.75
   27.96   75.17   30.96   75.21   44.94   74.67   54.53   73.18   58.93   70.89
   59.54   70.38   61.94   70.19   62.73   70.85    63.1    71.2   63.26   72.26
   63.84   72.24   65.63   73.13   67.29   72.98   71.57   73.67   77.43   73.81
   83.29   74.21   85.25   74.54    87.2   75.19   89.15   75.46   91.11   75.37
   94.04   75.72   95.99   75.44  101.85   75.48  105.76   75.04  108.69   75.03
#Mann= 3 , 0 , 0
       0     .12       0   58.93     .04       0   62.73     .06       0
Bank Sta=58.93,62.73
XS Rating Curve= 0 ,0
Exp/Cntr=0.3,0.1

Type RM Length L Ch R = 1 ,1.0880  ,74.59,73.94,73.56
BEGIN DESCRIPTION:
CB23 (SEM 2019)
END DESCRIPTION:
XS GIS Cut Line= 5
  597894.2660036 5422013.3402831  597849.4302036 5421969.4822831
  597826.0409036 5421949.0165831  597810.4966036 5421938.7639831
  597770.8090036 5421920.5738831
#Sta/Elev= 30
     -55   75.83  -22.15   75.27  -19.16   75.01  -17.17   74.23  -16.17   74.13
-8.20999   75.05    4.96   74.91   32.72   73.34   38.67   72.57   40.18   72.04
   45.36   71.69   46.47   71.47   47.14   70.99   47.46   70.46   47.86    70.3
   48.38   70.61   49.25   70.45   50.18   70.77   52.23    70.8   52.96   71.11
   53.74   71.91   54.94   72.68    56.2   72.53   67.22   72.93   74.16   73.39
   75.15   73.66   77.14   74.74   79.12   75.21   85.08   75.54  100.95   74.91
#Mann= 3 , 0 , 0
     -55     .12       0   47.14     .04       0   52.96     .06       0
Bank Sta=47.14,52.96
XS Rating Curve= 0 ,0
Exp/Cntr=0.3,0.1

Type RM Length L Ch R = 1 ,1.0141  ,11.5,11.43,11.37
BEGIN DESCRIPTION:
CB22 (SEM 2019)
END DESCRIPTION:
XS GIS Cut Line= 4
597969.2469035985421958.27708309597853.8222035985421878.57118309
597840.2622035985421871.95658309597805.8663035995421855.08938309
#Sta/Elev= 30
       0   76.44   10.94   75.81   11.94   75.26   12.93   75.35   13.93   74.97
   17.91   72.79    18.9   72.48   22.88   71.76   29.84   71.35   36.81   71.47
  129.33   70.83  139.28   70.94  140.27   70.64  142.98   70.43  143.84   70.19
  144.23   69.81  144.69   69.54  146.39   69.45  147.61   69.73   148.6   70.09
  150.76   71.74  153.32   72.09  165.18   71.97  175.99   72.38  182.86   72.19
  184.83   72.67  186.79    74.4  188.76   75.55   191.7   76.29  193.67   76.47
#Mann= 3 , 0 , 0
       0     .06       0  144.23     .04       0  147.61     .06       0
Bank Sta=144.23,147.61
XS Rating Curve= 0 ,0
Exp/Cntr=0.3,0.1

Type RM Length L Ch R = 1 ,1.0026  ,6.2,6.2,6.21
BEGIN DESCRIPTION:
US of Squires Lane 2 Bridge - CB21 (SEM 2019)
END DESCRIPTION:
XS GIS Cut Line= 4
597996.6974035995421952.32388309597859.1138035985421868.31858309
597843.5695035985421861.04248309597804.8741035985421846.82108309
#Sta/Elev= 30
       0    76.4    3.98   76.11    7.96   74.86   14.93   73.56   17.91   73.35
   18.91   73.55    19.9    73.3   28.86   72.86   38.81   71.64    40.8    71.9
   42.79    71.5   47.76   71.21  122.39    70.7  151.25   70.72  159.21   71.33
  162.83   70.95  165.01   70.37   165.7   69.81  166.25   69.65   167.6    69.7
  169.37   70.22  171.79   71.15  174.25   71.73  200.94   72.15  205.85   73.04
  206.83   73.41  208.79   74.59  210.76   75.26  215.66   75.61  219.59    75.6
#Mann= 3 , 0 , 0
       0     .06       0  165.01     .04       0  169.37     .06       0
Bank Sta=165.01,169.37
XS Rating Curve= 0 ,0
Exp/Cntr=0.3,0.1

Type RM Length L Ch R = 3 ,1.0     ,,,
Node Photo=.\Photos\CB-CR-6.JPG
BEGIN DESCRIPTION:
Squires Lane 2 Bridge
END DESCRIPTION:
Node Name=CB-CR-6
Bridge Culvert--1,0,-1,-1, 0
Deck Dist Width WeirC Skew NumUp NumDn MinLoCord MaxHiCord MaxSubmerge Is_Ogee
1,4.3,1.4,0, 226, 226, , , 0.98, 0, 3,3,,
      -1   -.001    .999   1.998   2.998   3.997   4.997   5.996   6.996   7.995
   8.995   9.994  10.994  11.993  12.992  13.992  14.991  15.991   16.99   17.99
  18.989  19.989  20.988  21.988  22.987  23.987  24.986  25.985  26.985  27.984
  28.984  29.983  30.983  31.982  32.982  33.981  34.981   35.98   36.98  37.979
  38.978  39.978  40.977  41.977  42.976  43.976  44.975  45.975  46.974  47.974
  48.973  49.973  50.972  51.971  52.971   53.97   54.97  55.969  56.969  57.968
  58.968  59.967  60.967  61.966  62.966  63.965  64.964  65.964  66.963  67.963
  68.962  69.962  70.961  71.961   72.96   73.96  74.959  75.959  76.958  77.957
  78.957  79.956  80.956  81.955  82.955  83.954  84.954  85.953  86.953  87.952
  88.951  89.951   90.95   91.95  92.949  93.949  94.948  95.948  96.947  97.947
  98.946  99.946 100.945 101.945 102.944 103.943 104.943 105.942 106.942 107.941
 108.941  109.94  110.94 111.939 112.939 113.938 114.938 115.937 116.936 117.936
 118.935 119.935 120.934 121.934 122.933 123.933 124.932 125.932 126.931 127.931
  128.93 129.929 130.929 131.928 132.928 133.927 134.927 135.926 136.926 137.925
 138.925 139.924 140.924 141.923 142.922 143.922 144.921 145.921  146.92  147.92
 148.919 149.919 150.918 151.918 152.917 153.917 154.916 155.915 156.915 157.914
 158.914 159.913 160.913 161.912 162.912 163.896 164.881 165.866 166.851 167.836
  168.82 169.805  170.79 171.775 172.759 173.744 174.729 175.714 176.699 177.696
 178.694 179.691 180.689 181.686 182.684 183.681 184.679 185.676 186.674 187.672
 188.669 189.667 190.664 191.662 192.659 193.657 194.654 195.652 196.649 197.647
 198.644 199.642  200.64 201.637 202.635 203.632  204.63 205.627 206.625 207.622
  208.62 209.617 210.615 211.613  212.61 213.608 214.605 215.603   216.6 217.598
 218.595 219.593  220.59 221.588 222.585 223.583
  75.863  75.509  75.283  75.141   74.97   74.56  74.484  74.396  74.337   74.11
  73.881  73.757  73.647  73.583  73.538  73.457  73.382  73.316  73.225  73.202
  73.142  73.115  73.088  73.069  73.059  73.003  72.946  72.897  72.849  72.749
  72.667  72.611  72.512   72.42  72.303  72.203  72.118  72.045  71.921  71.731
  71.692  71.645  71.515  71.493  71.336  71.261  71.177  71.179  71.139   71.12
  71.102  71.098  71.087  71.083  71.091  71.102  71.209  71.266  71.266  71.134
  71.165  71.138  71.128  71.126  71.118  71.106  71.118  71.112  71.111  71.103
  71.097   71.09  71.085  71.074   71.08  71.084   71.08  71.076  71.076  71.073
  71.065  71.069  71.055  71.046  71.042   71.04  71.036  71.033  71.023  71.019
  71.004  71.001  71.001  70.997  70.991  70.983  70.965  70.961  70.956  70.938
  70.943  70.927   70.92  70.905  70.906  70.898  70.876  70.864  70.838  70.799
  70.798  70.765  70.771  70.775  70.795  70.892  70.756  70.741  70.761  70.755
   70.74  70.717  70.695  70.698  70.716  70.749  70.749  70.741  70.727  70.745
  70.749  70.744  70.757  70.759  70.751  70.734  70.727   70.73  70.736   70.74
  70.746   70.74  70.716  70.724  70.748  70.756  70.754  70.755  70.767  70.747
   70.73  70.714  70.714   70.72  70.748  70.799   70.86  70.971  71.041  71.131
  71.224  71.319  71.413  71.527  71.504  71.527  71.551  71.574  71.598  71.621
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                                  70.904  70.927  70.951  70.974  70.998  71.021
  71.045  71.068  71.092  71.115  71.139  71.162
      -4  -3.001  -2.001  -1.002   -.002    .997   1.997   2.996   3.996   4.995
   5.995   6.994   7.994   8.993   9.992  10.992  11.991  12.991   13.99   14.99
  15.989  16.989  17.988  18.988  19.987  20.987  21.986  22.985  23.985  24.984
  25.984  26.983  27.983  28.982  29.982  30.981  31.981   32.98   33.98  34.979
  35.978  36.978  37.977  38.977  39.976  40.976  41.975  42.975  43.974  44.974
  45.973  46.973  47.972  48.971  49.971   50.97   51.97  52.969  53.969  54.968
  55.968  56.967  57.967  58.966  59.966  60.965  61.964  62.964  63.963  64.963
  65.962  66.962  67.961  68.961   69.96   70.96  71.959  72.959  73.958  74.957
  75.957  76.956  77.956  78.955  79.955  80.954  81.954  82.953  83.953  84.952
  85.951  86.951   87.95   88.95  89.949  90.949  91.948  92.948  93.947  94.947
  95.946  96.946  97.945  98.944  99.944 100.943 101.943 102.942 103.942 104.941
 105.941  106.94  107.94 108.939 109.939 110.938 111.938 112.937 113.936 114.936
 115.935 116.935 117.934 118.934 119.933 120.933 121.932 122.932 123.931 124.931
  125.93 126.929 127.929 128.928 129.928 130.927 131.927 132.926 133.926 134.925
 135.925 136.924 137.924 138.923 139.922 140.922 141.921 142.921  143.92  144.92
 145.919 146.919 147.918 148.918 149.917 150.917 151.916 152.915 153.915 154.914
 155.914 156.913 157.913 158.912 159.912 160.896 161.881 162.866 163.851 164.836
  165.82 166.805  167.79 168.775 169.759 170.744 171.729 172.714 173.699 174.696
 175.694 176.691 177.689 178.686 179.684 180.681 181.679 182.676 183.674 184.672
 185.669 186.667 187.664 188.662 189.659 190.657 191.654 192.652 193.649 194.647
 195.644 196.642  197.64 198.637 199.635 200.632  201.63 202.627 203.625 204.622
  205.62 206.617 207.615 208.613  209.61 210.608 211.605 212.603   213.6 214.598
 215.595 216.593  217.59 218.588 219.585 220.583
  75.863  75.509  75.283  75.141   74.97   74.56  74.484  74.396  74.337   74.11
  73.881  73.757  73.647  73.583  73.538  73.457  73.382  73.316  73.225  73.202
  73.142  73.115  73.088  73.069  73.059  73.003  72.946  72.897  72.849  72.749
  72.667  72.611  72.512   72.42  72.303  72.203  72.118  72.045  71.921  71.731
  71.692  71.645  71.515  71.493  71.336  71.261  71.177  71.179  71.139   71.12
  71.102  71.098  71.087  71.083  71.091  71.102  71.209  71.266  71.266  71.134
  71.165  71.138  71.128  71.126  71.118  71.106  71.118  71.112  71.111  71.103
  71.097   71.09  71.085  71.074   71.08  71.084   71.08  71.076  71.076  71.073
  71.065  71.069  71.055  71.046  71.042   71.04  71.036  71.033  71.023  71.019
  71.004  71.001  71.001  70.997  70.991  70.983  70.965  70.961  70.956  70.938
  70.943  70.927   70.92  70.905  70.906  70.898  70.876  70.864  70.838  70.799
  70.798  70.765  70.771  70.775  70.795  70.892  70.756  70.741  70.761  70.755
   70.74  70.717  70.695  70.698  70.716  70.749  70.749  70.741  70.727  70.745
  70.749  70.744  70.757  70.759  70.751  70.734  70.727   70.73  70.736   70.74
  70.746   70.74  70.716  70.724  70.748  70.756  70.754  70.755  70.767  70.747
   70.73  70.714  70.714   70.72  70.748  70.799   70.86  70.971  71.041  71.131
  71.224  71.319  71.413  71.527  71.509  71.531  71.552  71.574  71.595  71.617
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                                  70.909  70.931  70.952  70.974  70.995  71.017
  71.038   71.06  71.081  71.103  71.124  71.146
BR Coef=-1 , 0 , 0 ,, 0 ,,,0.8,-1,,0,
WSPro=,,,, 1 ,,,, 0 ,,,, 0 ,,,,-1 ,-1 ,-1 , 0 , 0 , 0 , 0 , 0
BC Design=,, 0 ,, 0 ,,,,,,
BC Use User HTab Curves=0
BC User HTab FreeFlow(D)= 0

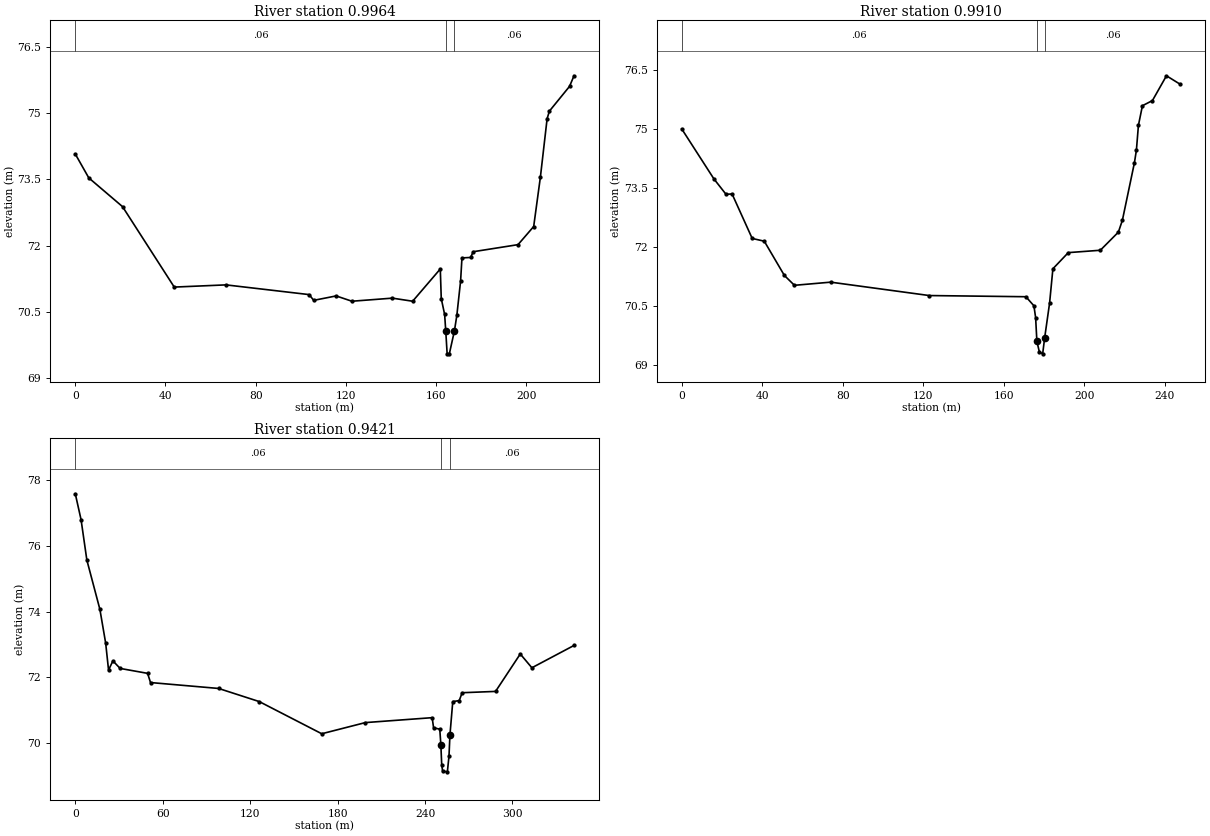
Type RM Length L Ch R = 1 ,0.9964  ,5.48,5.48,5.49
BEGIN DESCRIPTION:
DS of Squires Lane 2 Bridge - CB20 (SEM 2019)
END DESCRIPTION:
XS GIS Cut Line= 4
597999.1193035985421944.55578309597864.7107035985421864.12238309
597846.7190035985421855.65568309597804.9148035985421839.78058309
#Sta/Elev= 30
       0   74.07    5.99   73.53   20.95   72.88    43.9   71.06   66.85   71.11
  103.76   70.89  105.75   70.76  115.73   70.86  122.72   70.74  140.67   70.81
  149.65   70.74  161.92   71.47  162.35    70.8  163.85   70.44  164.35   70.06
  164.96   69.55  165.93   69.55  168.19   70.07  169.26   70.42  170.93    71.2
  171.53   71.72  175.37   71.73  176.52   71.86   196.4   72.02  203.35   72.43
  206.33   73.55  209.31   74.87  210.31   75.04  219.25    75.6  221.24   75.84
#Mann= 3 , 0 , 0
       0     .06       0  164.35     .04       0  168.19     .06       0
Bank Sta=164.35,168.19
XS Rating Curve= 0 ,0
Exp/Cntr=0.3,0.1

Type RM Length L Ch R = 1 ,0.9910  ,49.09,48.82,48.6
BEGIN DESCRIPTION:
CB19 (SEM 2019)
END DESCRIPTION:
XS GIS Cut Line= 4
598012.3485035985421947.73088309597866.2982035985421858.83068309
597847.2482035985421849.83478309597794.8606035985421830.78478309
#Sta/Elev= 30
       0      75      16   73.73      22   73.34      25   73.35      35   72.22
      41   72.15   50.99   71.28   55.99   71.03   73.99   71.11  122.99   70.77
  170.98   70.74  174.97   70.51  175.82   70.21  176.44   69.61  177.66   69.34
  179.32   69.29  180.29   69.69  182.76   70.58   184.4   71.45  192.05   71.86
  207.97   71.92  216.93   72.38  218.92   72.68   224.9   74.14  225.89   74.46
  226.89   75.09  228.88   75.59  233.85   75.72  240.82   76.35  247.79   76.13
#Mann= 3 , 0 , 0
       0     .06       0  176.44     .04       0  180.29     .06       0
Bank Sta=176.44,180.29
XS Rating Curve= 0 ,0
Exp/Cntr=0.3,0.1

Type RM Length L Ch R = 1 ,0.9421  ,13.29,13.76,14.14
BEGIN DESCRIPTION:
US of Squires Lane 1 Bridge - CB18B (SEM 2019)
END DESCRIPTION:
XS GIS Cut Line= 5
598111.3982035985421919.93428309598038.1005035985421884.53428309
597889.0524035985421814.90978309597872.6482035985421808.55968309
597810.7356035985421759.87628309
#Sta/Elev= 30
       0   77.59    3.97    76.8    7.94   75.57   16.88   74.07   20.85   73.04
   22.83   72.22   25.81    72.5   30.77   72.27   49.63   72.12   51.62   71.84
   98.35   71.66  126.26   71.26  169.14   70.28  199.05   70.62  244.91   70.77
  245.89   70.46  250.14   70.42  250.87   69.95  251.46   69.34  252.09   69.14
  255.35   69.12  256.46    69.6  257.11   70.24  259.05   71.26  263.48   71.29
  265.49   71.53  288.42   71.57  305.37   72.71  313.35   72.29  342.26   72.97
#Mann= 3 , 0 , 0
       0     .06       0  250.87     .04       0  257.11     .06       0
Bank Sta=250.87,257.11
XS Rating Curve= 0 ,0
Exp/Cntr=0.3,0.1