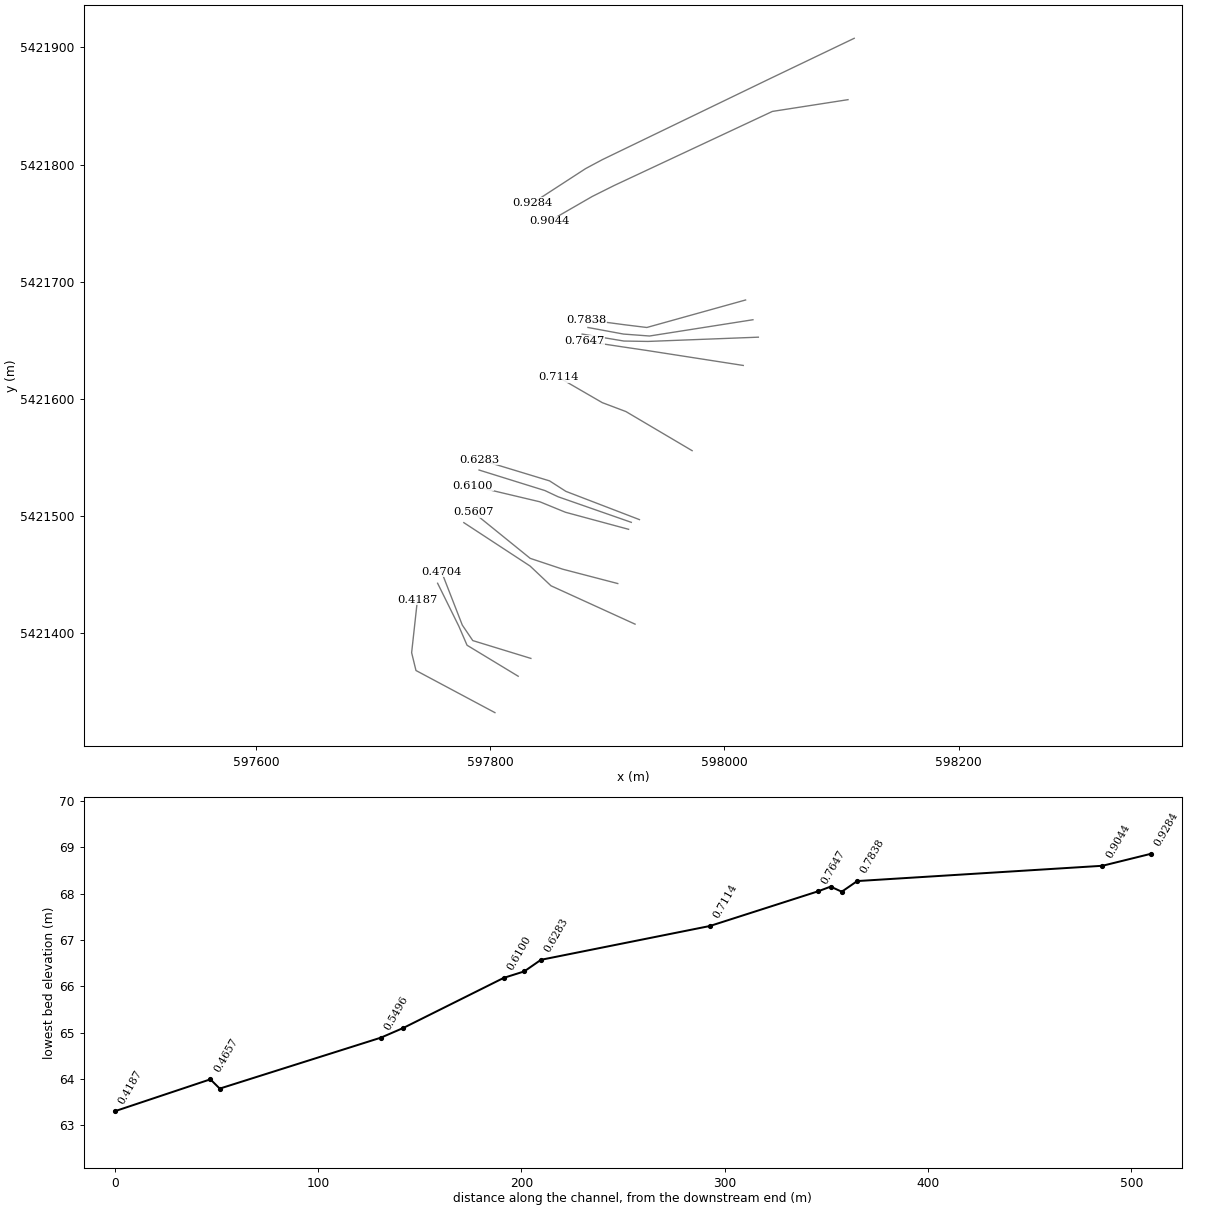
HEC-RAS study Exploits_FMM.prj: Exploits_FMM

--- Exploits_FMM.g01 (geometry) --- (continued)

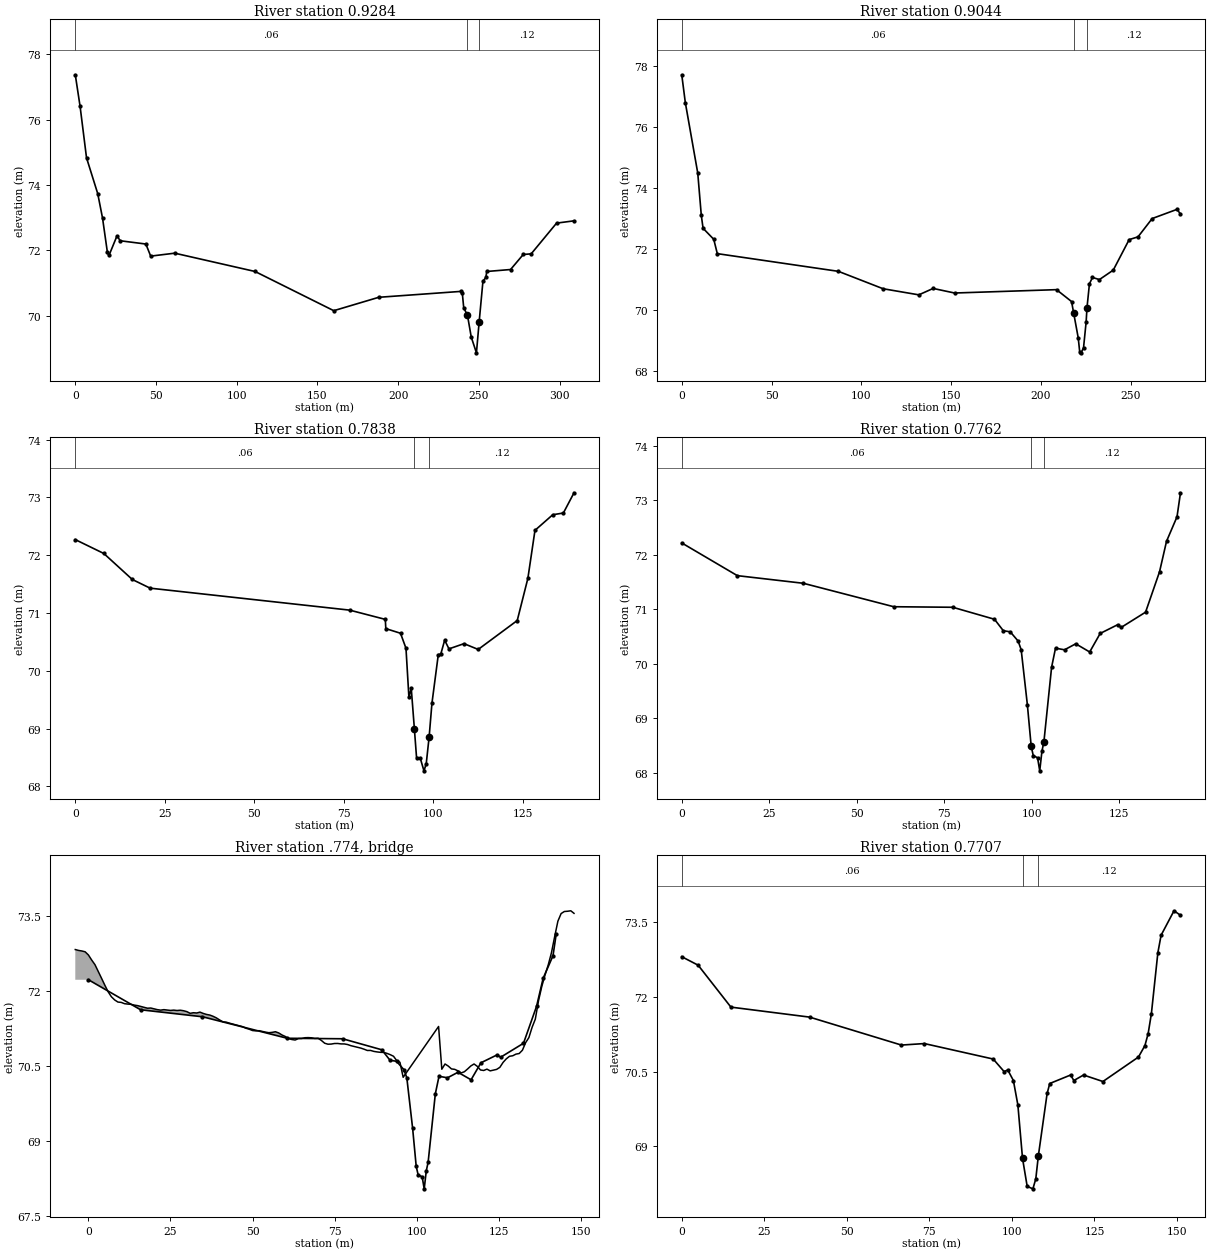
Type RM Length L Ch R = 1 ,0.9284  ,24.09,23.98,23.9
BEGIN DESCRIPTION:
DS of Squires Lane 1 Bridge - CB18A (SEM 2019)
END DESCRIPTION:
XS GIS Cut Line= 5
598110.8690035995421907.76338309598038.2943035985421873.00118309
597895.8248035985421804.15698309597881.6035035985421796.55018309
597836.2935035985421767.11518309
#Sta/Elev= 30
       0   77.37    2.98    76.4    6.95   74.83   13.91   73.73   16.89   72.98
   19.87   71.94   20.86   71.84   25.83   72.44   27.82   72.29   43.71   72.19
   46.69   71.82   61.59   71.91  111.32   71.35  160.08   70.15  187.95   70.56
   238.7   70.74  239.65    70.7  240.56   70.24  242.87   70.01  245.23   69.34
  248.43   68.86  250.12   69.81  252.46   71.05  254.27   71.17  254.83   71.35
  269.57   71.41  277.42   71.87  282.34   71.89  298.06   72.83  308.86    72.9
#Mann= 3 , 0 , 0
       0     .06       0  242.87     .04       0  250.12     .12       0
Bank Sta=242.87,250.12
XS Rating Curve= 0 ,0
Exp/Cntr=0.3,0.1

Type RM Length L Ch R = 1 ,0.9044  ,123.13,120.58,118.52
BEGIN DESCRIPTION:
CB18 (SEM 2019)
END DESCRIPTION:
XS GIS Cut Line= 5
598105.5773035995421855.37578309598041.0128035985421845.33438309
597905.7467035995421781.99808309597887.2259035995421772.73768309
597850.5149035985421751.57088309
#Sta/Elev= 30
       0   77.71    1.98    76.8    8.91   74.49   10.89    73.1   11.88   72.68
   17.82   72.32    19.8   71.85   87.25   71.27  112.14    70.7  132.05    70.5
  140.02   70.71  151.97   70.56  208.73   70.67  217.12   70.28  218.27   69.91
  220.83   69.09  221.67   68.62  222.46    68.6  223.79   68.77  225.23   69.61
  225.71   70.08  227.07   70.86  228.75   71.07  232.62      71  240.34   71.31
   249.2   72.31  254.13    72.4  262.02      73  275.81    73.3  277.78   73.15
#Mann= 3 , 0 , 0
       0     .06       0  218.27     .04       0  225.71     .12       0
Bank Sta=218.27,225.71
XS Rating Curve= 0 ,0
Exp/Cntr=0.3,0.1

Type RM Length L Ch R = 1 ,0.7838  ,7.42,7.6,7.75
BEGIN DESCRIPTION:
CB17 (SEM 2019)
END DESCRIPTION:
XS GIS Cut Line= 4
598018.1287035985421684.34458309597933.7926035985421660.86278309
597914.9410035985421663.17788309597882.5295035985421667.47738309
#Sta/Elev= 30
       0   72.27    7.96   72.03   15.92   71.58   20.89   71.43    76.6   71.05
   86.55   70.89   86.69   70.73   90.79   70.65   92.32   70.39   93.14   69.54
   93.79    69.7   94.66      69   95.27    68.5    96.3   68.49   97.34   68.27
   97.97   68.39   98.79   68.86   99.57   69.44  101.34   70.28  102.04   70.29
  103.12   70.53  104.32   70.38  108.52   70.47  112.48   70.37  123.38   70.87
  126.35    71.6  128.33   72.43  133.29    72.7  136.26   72.73  139.23   73.08
#Mann= 3 , 0 , 0
       0     .06       0   94.66     .04       0   98.79     .12       0
Bank Sta=94.66,98.79
XS Rating Curve= 0 ,0
Exp/Cntr=0.3,0.1

Type RM Length L Ch R = 1 ,0.7762  ,5.26,5.47,5.63
BEGIN DESCRIPTION:
US of Corduroy Brook Nature Trail 2 Bridge - CB16 (SEM 2019)
END DESCRIPTION:
XS GIS Cut Line= 4
598024.4126035985421667.47738309597936.1077035985421653.58668309
597913.9488035985421655.24038309597883.5217035985421660.86278309
#Sta/Elev= 30
       0   72.22   15.89   71.62   34.76   71.48   60.59   71.05   77.47   71.04
   89.39   70.82   91.91   70.61   93.89   70.59   96.15   70.42   97.02   70.26
   98.79   69.25   99.88   68.49  100.47   68.32   101.7   68.28  102.32   68.04
  102.95    68.4  103.51   68.57  105.71   69.94  106.83   70.29  109.41   70.26
  112.61   70.37   116.6   70.22   119.6   70.56  124.59   70.72  125.59   70.67
  132.57   70.95  136.56   71.69  138.56   72.25  141.56    72.7  142.55   73.14
#Mann= 3 , 0 , 0
       0     .06       0   99.88     .04       0  103.51     .12       0
Bank Sta=99.88,103.51
XS Rating Curve= 0 ,0
Exp/Cntr=0.3,0.1

Type RM Length L Ch R = 3 ,.774    ,,,
Node Photo=.\Photos\CB-CR-4.JPG
BEGIN DESCRIPTION:
Corduroy Brook Nature Trail 2 Bridge
END DESCRIPTION:
Node Name=CB-CR-4
Bridge Culvert--1,0,-1,-1, 0
Deck Dist Width WeirC Skew NumUp NumDn MinLoCord MaxHiCord MaxSubmerge Is_Ogee
2,1.6,1.4,0, 154, 154, , , 0.98, 0, 3,3,,
      -4-3.00018-2.00036-1.00054 -.00072.99908761.9989052.998723 3.998544.998358
5.9981756.997993 7.997818.9976279.99744510.9972611.99708 12.996913.9967214.99653
15.9963516.9961717.99599 18.995819.9956220.9954421.9952522.9950723.9948924.99471
25.9945326.9943427.9941628.99398 29.993830.9936131.9934332.9932533.9930634.99288
 35.992736.9925237.9923438.9921539.9919740.99179 41.991642.9914243.9912444.99106
45.9908846.9906947.9905148.9903349.9901550.9899651.98978 52.989653.9894154.98923
55.9890556.9888757.98869 58.988559.9883260.9881461.9879662.9877763.9875964.98741
65.9872366.9870567.9868668.98668 69.986570.9863171.9861372.9859573.9857674.98558
 75.985476.9852277.9850478.9848679.9846780.9844981.9843182.9841283.9839484.98376
85.9835786.9833987.9832188.9830389.9828590.9826791.9824892.9636893.9448794.92606
95.9072596.8884497.8696498.8508399.83202100.8132101.7944102.7756103.7568 104.738
105.7192106.7004107.6816108.6628 109.644110.6266111.6092112.5918113.5744 114.557
115.5396116.5222117.5048118.4875119.4701120.4527121.4353122.4179123.4005124.3831
125.3657126.3484 127.331128.3136129.2962130.2788131.2614 132.244133.2266134.2092
135.1919136.1745137.1571138.1397139.1223140.1049141.0875142.0701143.0528144.0354
 145.018146.0006146.9832147.9658
 72.8239 72.8061 72.7952 72.7787 72.7151 72.6137 72.5211 72.3869 72.2497 72.1118
 71.9805   71.88 71.8163 71.7739 71.7672 71.7414 71.7334 71.7284  71.713 71.7026
 71.6857 71.6679 71.6509 71.6548  71.638 71.6225 71.6125 71.6224 71.6152 71.6068
 71.6129 71.6054 71.6109 71.6005 71.5827 71.5488 71.5607 71.5553 71.5728 71.5465
 71.5267  71.514 71.4893 71.4573 71.4156 71.3789 71.3722 71.3518 71.3344 71.3173
 71.3003 71.2816 71.2509 71.2316 71.2049 71.1981 71.2014 71.1859 71.1726 71.1613
 71.1681 71.1809 71.1561 71.1157  71.086 71.0426  71.025 71.0151 71.0437 71.0456
  71.061 71.0632 71.0594 71.0471 71.0507 71.0065 70.9511 70.9316 70.9341 70.9455
  70.946 70.9372 70.9368 70.9246  70.902  70.886 70.8683 70.8539 70.8318 70.8062
 70.8069 70.7874 70.7769 70.7691 70.7679 70.7477  70.722 70.6905 70.6033 70.5702
   70.2770.3623770.4547370.5470970.6394670.7318270.8241870.9165471.0089171.10127
71.19363  71.286 70.4313 70.5361 70.4942 70.4373 70.4289 70.3989  70.357  70.381
 70.4362 70.4964 70.5361 70.4889 70.4162 70.4061 70.4331 70.3985  70.413 70.4278
 70.4689 70.5675  70.639 70.6903 70.7004 70.7332 70.7454 70.8111 70.9629 71.0627
 71.2689 71.4328 71.8024 72.0847 72.3126 72.5154 72.7589 73.0828 73.3906 73.5432
 73.5842 73.5894 73.5988 73.5476
   69.8769.9623670.0547370.1470970.2394670.3318270.4241870.5165570.6089170.70127
70.79364  70.886
       0.99981751.9996352.999453 3.999274.9990885.9989056.998723 7.998548.998358
9.99817610.9979911.9978112.9976313.9974514.9972615.99708 16.996917.9967218.99653
19.9963520.9961721.99599 22.995823.9956224.9954425.9952526.9950727.9948928.99471
29.9945330.9943431.9941632.99398 33.993834.9936135.9934336.9932537.9930638.99288
 39.992740.9925241.9923442.9921543.9919744.99179 45.991646.9914247.9912448.99106
49.9908850.9906951.9905152.9903353.9901554.9899655.98978 56.989657.9894158.98923
59.9890560.9888761.98869 62.988563.9883264.9881465.9879566.9877767.9875968.98741
69.9872370.9870571.9868672.98668 73.986574.9863175.9861376.9859577.9857678.98558
 79.985480.9852281.9850482.9848683.9846784.9844985.9843186.9841287.9839488.98376
89.9835790.9833991.9832192.9830393.9828594.9826795.9824896.9636897.9448798.92606
99.90725100.8884101.8696102.8508 103.832104.8132105.7944106.7756107.7568 108.738
109.7192110.7004111.6816112.6628 113.644114.6266115.6092116.5918117.5744 118.557
119.5396120.5222121.5048122.4875123.4701124.4527125.4353126.4179127.4005128.3831
129.3657130.3484 131.331132.3136133.2962134.2788135.2614 136.244137.2266138.2092
139.1919140.1745141.1571142.1397143.1223144.1049145.0875146.0701147.0528148.0354
 149.018150.0006150.9832151.9658
 72.8239 72.8061 72.7952 72.7787 72.7151 72.6137 72.5211 72.3869 72.2497 72.1118
 71.9805   71.88 71.8163 71.7739 71.7672 71.7414 71.7334 71.7284  71.713 71.7026
 71.6857 71.6679 71.6509 71.6548  71.638 71.6225 71.6125 71.6224 71.6152 71.6068
 71.6129 71.6054 71.6109 71.6005 71.5827 71.5488 71.5607 71.5553 71.5728 71.5465
 71.5267  71.514 71.4893 71.4573 71.4156 71.3789 71.3722 71.3518 71.3344 71.3173
 71.3003 71.2816 71.2509 71.2316 71.2049 71.1981 71.2014 71.1859 71.1726 71.1613
 71.1681 71.1809 71.1561 71.1157  71.086 71.0426  71.025 71.0151 71.0437 71.0456
  71.061 71.0632 71.0594 71.0471 71.0507 71.0065 70.9511 70.9316 70.9341 70.9455
  70.946 70.9372 70.9368 70.9246  70.902  70.886 70.8683 70.8539 70.8318 70.8062
 70.8069 70.7874 70.7769 70.7691 70.7679 70.7477  70.722 70.6905 70.6033 70.5702
  70.20670.2953670.3847370.4740970.5634570.6528270.7421870.8315470.9209171.01027
71.09964  71.189 70.4313 70.5361 70.4942 70.4373 70.4289 70.3989  70.357  70.381
 70.4362 70.4964 70.5361 70.4889 70.4162 70.4061 70.4331 70.3985  70.413 70.4278
 70.4689 70.5675  70.639 70.6903 70.7004 70.7332 70.7454 70.8111 70.9629 71.0627
 71.2689 71.4328 71.8024 72.0847 72.3126 72.5154 72.7589 73.0828 73.3906 73.5432
 73.5842 73.5894 73.5988 73.5476
  69.80669.8953669.9847370.0740970.1634570.2528270.3421870.4315570.5209170.61028
70.69964  70.789
BR Coef=-1 , 0 , 0 ,, 0 ,,,0.8,-1,,0,
WSPro=,,,, 1 ,,,, 0 ,,,, 0 ,,,,-1 ,-1 ,-1 , 0 , 0 , 0 , 0 , 0
BC Design=,, 0 ,, 0 ,,,,,,
BC Use User HTab Curves=0
BC User HTab FreeFlow(D)= 0

Type RM Length L Ch R = 1 ,0.7707  ,6.57,6.09,5.76
BEGIN DESCRIPTION:
DS of Corduroy Brook Nature Trail 2 Bridge - CB15 (SEM 2019)
END DESCRIPTION:
XS GIS Cut Line= 4
598029.0428035995421652.59448309597934.7848035985421648.95648309
597914.2796035995421649.28718309597878.5608035985421655.24038309
#Sta/Elev= 30
       0    72.8    4.96   72.63   14.89   71.79   38.72   71.59   66.53   71.03
   73.48   71.06   94.33   70.75   97.62    70.5   98.75   70.53  100.44   70.32
   101.8   69.83  103.21   68.76  104.62    68.2  106.35   68.15  107.23   68.35
     108   68.81  110.66   70.06  111.46   70.26  117.77   70.43  118.75   70.32
  121.69   70.43  127.56    70.3  138.32   70.79  140.28   71.02  141.26   71.26
  142.24   71.66   144.2   72.88  145.18   73.23  149.09   73.72  151.05   73.63
#Mann= 3 , 0 , 0
       0     .06       0  103.21     .04       0     108     .12       0
Bank Sta=103.21,108
XS Rating Curve= 0 ,0
Exp/Cntr=0.3,0.1

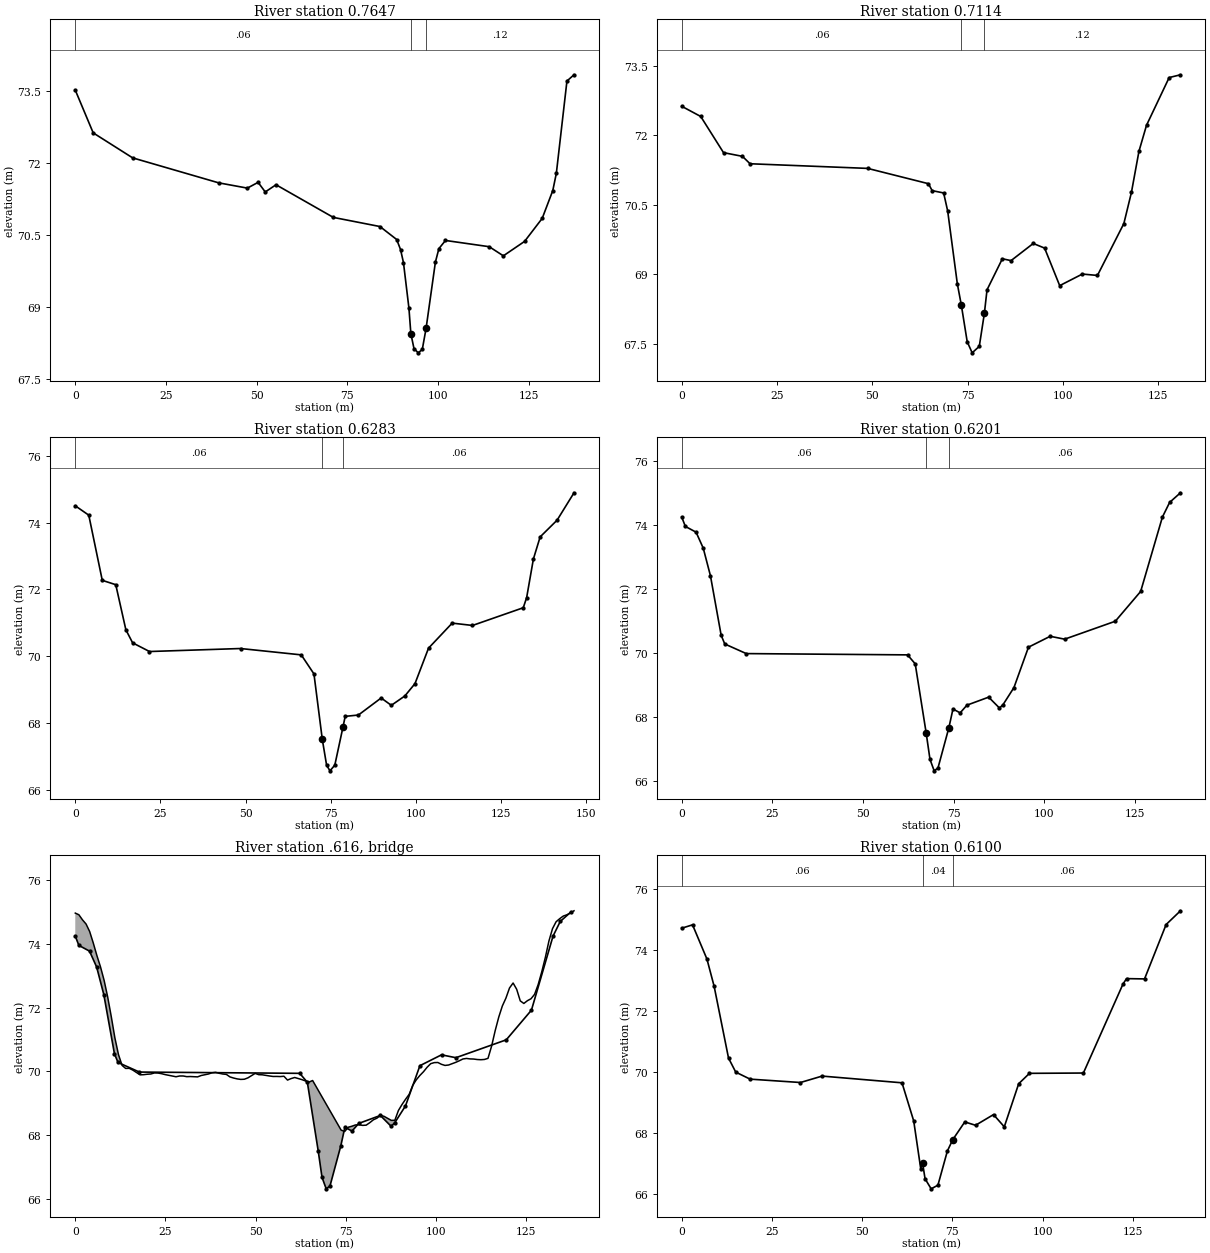
Type RM Length L Ch R = 1 ,0.7647  ,54.03,53.28,52.38
BEGIN DESCRIPTION:
CB14 (SEM 2019)
END DESCRIPTION:
XS GIS Cut Line= 4
598016.1444035985421628.45128309597933.1312035985421641.34968309
597912.9567035995421644.32628309597880.2144035995421649.28718309
#Sta/Elev= 30
       0   73.52    4.94   72.63   15.81   72.11   39.53   71.59   47.44   71.48
   50.41    71.6   52.38    71.4   55.35   71.55   71.16   70.87   84.01   70.68
   88.62   70.41   89.69    70.2   90.49   69.93      92   68.98   92.53   68.45
   93.39   68.14   94.56   68.05   95.68   68.12   96.73   68.56    99.3   69.94
  100.26   70.22  102.08   70.39  114.14   70.26  118.04   70.07  123.88   70.37
  128.75   70.85  131.67   71.43  132.65   71.79  135.57   73.71  137.52   73.84
#Mann= 3 , 0 , 0
       0     .06       0   92.53     .04       0   96.73     .12       0
Bank Sta=92.53,96.73
XS Rating Curve= 0 ,0
Exp/Cntr=0.3,0.1

Type RM Length L Ch R = 1 ,0.7114  ,84,83.08,82.43
BEGIN DESCRIPTION:
CB13 (SEM 2019)
END DESCRIPTION:
XS GIS Cut Line= 4
597972.4880035995421555.69068309597915.9332035985421589.09438309
597895.7587035985421596.70118309597858.0555035985421618.52938309
#Sta/Elev= 30
       0   72.62    4.98    72.4   10.95   71.62   15.92   71.54   17.91   71.38
   48.76   71.28   64.69   70.95   65.68    70.8   68.69   70.75   69.75   70.36
   72.28   68.79   73.33   68.33   74.87   67.54   76.17    67.3   78.04   67.44
   79.37   68.15   80.07   68.66   84.09   69.33   86.37   69.29   92.19   69.66
   95.17   69.56   99.13   68.75  105.07      69  109.03   68.97  115.96   70.09
  117.94   70.76  119.92   71.65   121.9   72.21  127.84   73.24  130.81    73.3
#Mann= 3 , 0 , 0
       0     .06       0   73.33     .04       0   79.37     .12       0
Bank Sta=73.33,79.37
XS Rating Curve= 0 ,0
Exp/Cntr=0.3,0.1

Type RM Length L Ch R = 1 ,0.6283  ,7.69,8.2,8.49
BEGIN DESCRIPTION:
CB12 (SEM 2019)
END DESCRIPTION:
XS GIS Cut Line= 4
597927.5088035995421496.82078309597864.6701035985421520.96408309
597850.7794035985421529.89378309597790.9173035985421548.08388309
#Sta/Elev= 30
       0    74.5    3.96   74.22    7.92   72.27   11.88   72.14   14.85   70.79
   16.83    70.4   21.78   70.14   48.51   70.23   66.33   70.04   70.06   69.47
   72.51   67.51   73.77   66.74   74.76   66.57   76.18   66.74    78.6   67.89
   79.23    68.2   83.11   68.24   89.79   68.75   92.77   68.53   96.74   68.81
   99.72   69.18  103.69   70.24  110.64   70.99   116.6   70.92   131.5   71.45
  132.49   71.75  134.48   72.91  136.46   73.57  141.43   74.07   146.4   74.89
#Mann= 3 , 0 , 0
       0     .06       0   72.51     .04       0    78.6     .06       0
Bank Sta=72.51,78.6
XS Rating Curve= 0 ,0
Exp/Cntr=0.3,0.1

Type RM Length L Ch R = 1 ,0.6201  ,9.99,10.1,10.3
BEGIN DESCRIPTION:
US of Corduroy Brook Nature Trail 1 Bridge - CB11 (SEM 2019)
END DESCRIPTION:
XS GIS Cut Line= 4
597920.5634035985421494.50568309597858.0555035985421516.33378309
597846.8107035985421521.62548309597790.5866035995421539.15418309
#Sta/Elev= 30
       0   74.24     .99   73.95    3.95   73.77    5.93   73.27    7.91   72.41
   10.87   70.55   11.86   70.28   17.79   69.98   62.26   69.94   64.38   69.66
   67.39   67.51   68.45   66.68   69.61   66.32   70.66   66.41   73.67   67.67
   74.79   68.25   76.77   68.13   78.64   68.37   84.63   68.62   87.62   68.28
   88.62   68.39   91.61   68.92   95.61   70.18   101.6   70.52  105.59   70.43
  119.56   70.99  126.55   71.92  132.54   74.24  134.54    74.7  137.53      75
#Mann= 3 , 0 , 0
       0     .06       0   67.39     .04       0   73.67     .06       0
Bank Sta=67.39,73.67
XS Rating Curve= 0 ,0
Exp/Cntr=0.3,0.1

Type RM Length L Ch R = 3 ,.616    ,,,
Node Photo=.\Photos\CB-CR-3.JPG
BEGIN DESCRIPTION:
Corduroy Brook Nature Trail 1 Bridge
END DESCRIPTION:
Node Name=CB-CR-3
Bridge Culvert--1,0,-1,-1, 0
Deck Dist Width WeirC Skew NumUp NumDn MinLoCord MaxHiCord MaxSubmerge Is_Ogee
3,1.7,1.4,0, 140, 140, , , 0.98, 0, 3,3,,
       0    .998   1.996   2.994   3.992    4.99   5.988   6.985   7.983   8.981
   9.979  10.977  11.975  12.973  13.971  14.969  15.967  16.965  17.963  18.961
  19.958  20.956  21.954  22.952   23.95  24.948  25.946  26.944  27.942   28.94
  29.938  30.936  31.933  32.931  33.929  34.927  35.925  36.923  37.921  38.919
  39.917  40.915  41.913  42.911  43.909  44.906  45.904  46.902    47.9  48.898
  49.896  50.894  51.892   52.89  53.888  54.886  55.884  56.882  57.879  58.877
  59.875  60.873  61.871  62.869  63.867  64.856  65.844  66.833  67.821   68.81
  69.798  70.787  71.775  72.764  73.752  74.741  75.729  76.723  77.718  78.712
  79.706    80.7  81.694  82.688  83.683  84.677  85.671  86.665  87.659  88.653
  89.647  90.642  91.636   92.63  93.624  94.618  95.612  96.607  97.601  98.595
  99.589 100.583 101.577 102.572 103.566  104.56 105.554 106.548 107.542 108.536
 109.531 110.525 111.519 112.513 113.507 114.501 115.496  116.49 117.484 118.478
 119.472 120.466 121.461 122.455 123.449 124.443 125.437 126.431 127.425  128.42
 129.414 130.408 131.402 132.396  133.39 134.385 135.379 136.373 137.367 138.361
  74.962   74.91  74.751  74.619  74.383  74.025  73.633   73.28  72.861  72.336
  71.721  71.056  70.531   70.19  70.094  70.097  70.041  69.966  69.893  69.898
  69.912   69.92  69.952  69.949  69.929    69.9  69.877  69.852  69.833  69.857
  69.857  69.836   69.84  69.836  69.829  69.872  69.894  69.919  69.957  69.972
  69.942  69.919  69.907  69.828  69.793  69.766   69.75  69.755  69.799   69.87
  69.938  69.898  69.894  69.874  69.857  69.842  69.843  69.839  69.849  69.729
  69.776   69.81  69.778  69.743  69.701  69.667  69.715  69.521  69.326  69.132
  68.938  68.743  68.549  68.354   68.16  68.118  68.251  68.282  68.322   68.33
  68.309  68.316  68.393  68.483  68.535  68.624  68.592  68.528  68.466  68.469
  68.776  68.963  69.129  69.282  69.564   69.74  69.875  69.991   70.13  70.243
  70.276   70.28  70.223  70.188  70.201  70.243  70.285  70.335   70.39  70.407
  70.392  70.388  70.373  70.367  70.375   70.41  70.793  71.277  71.703  72.051
  72.298  72.615  72.771  72.574  72.211   72.13  72.217  72.278  72.417  72.723
  73.122  73.573  74.088  74.475  74.691  74.787  74.869  74.909  74.966  75.035
                                                  69.315  69.121  68.926  68.732
  68.538  68.343  68.149  67.954   67.76
      -1   -.002 .9958431.9937652.9916863.9896084.9875295.9854516.9833727.981294
8.9792159.97713710.9750611.97298 12.970913.9688214.9667415.9646716.9625917.96051
18.9584319.9563520.9542721.9521922.9501223.9480424.9459625.94388 26.941827.93972
28.9376429.9355730.9334931.9314132.9293333.9272534.92517 35.923136.9210237.91894
38.9168639.91478 40.912741.9106342.9085543.9064744.9043945.9023146.9002347.89816
48.89608  49.89450.8919251.8898452.8877653.8856854.8836155.8815356.8794557.87737
58.8752959.8732160.8711361.8690662.86698 63.855564.8440265.8325566.8210767.80959
68.7981269.7866470.7751671.7636972.7522173.7407374.7292675.7234176.7175777.71172
78.7058979.70004 80.694281.6883582.6825183.6766784.6708285.6649886.65914 87.6533
88.6474589.6416190.6357791.6299292.6240893.61823 94.612495.6065596.6007197.59486
98.5890299.58318100.5773101.5715102.5657103.5598 104.554105.5481106.5423107.5364
108.5306109.5247110.5189111.5131112.5072113.5014114.4955115.4897116.4838 117.478
118.4722119.4663120.4605121.4546122.4488123.4429124.4371125.4313126.4254127.4196
128.4137129.4079 130.402131.3962132.3904133.3845134.3787135.3728 136.367137.3611
 74.9624 74.9103  74.751 74.6194 74.3834 74.0251 73.6326 73.2798 72.8606 72.3364
 71.7212  71.056 70.5306 70.1896 70.0941 70.0969 70.0412 69.9662 69.8928 69.8984
 69.9121 69.9204 69.9523 69.9491 69.9285 69.8998  69.877 69.8517  69.833  69.857
 69.8565 69.8359 69.8403 69.8356 69.8292  69.872 69.8943 69.9194 69.9566 69.9716
 69.9415 69.9191 69.9071 69.8284  69.793 69.7659 69.7496 69.7549 69.7987 69.8695
  69.938 69.8982 69.8939 69.8735 69.8567 69.8415 69.8432  69.839 69.8491 69.7292
 69.7758   69.81 69.7781 69.7428 69.7006 69.6669  69.71369.5238769.3347569.14562
 68.956568.7673768.5782568.38912    68.2 68.1184 68.2508 68.2815 68.3215 68.3295
 68.3089 68.3163 68.3927 68.4832 68.5348 68.6237 68.5916 68.5281  68.466 68.4686
 68.7764 68.9626 69.1294 69.2819 69.5644 69.7398 69.8749 69.9913   70.13 70.2426
 70.2757 70.2798 70.2232 70.1878 70.2006 70.2433 70.2847 70.3345 70.3898 70.4066
 70.3919 70.3881 70.3731 70.3671 70.3753 70.4101 70.7933 71.2765 71.7026 72.0506
 72.2978 72.6154  72.771 72.5738 72.2108 72.1302 72.2171 72.2777 72.4165 72.7228
 73.1222 73.5733 74.0876 74.4747  74.691 74.7869 74.8687 74.9085 74.9664 75.0345
                                                  69.31369.1238868.9347568.74563
 68.556568.3673868.1782567.98913    67.8
BR Coef=-1 , 0 , 0 ,, 0 ,,,0.8,-1,,0,
WSPro=,,,, 1 ,,,, 0 ,,,, 0 ,,,,-1 ,-1 ,-1 , 0 , 0 , 0 , 0 , 0
BC Design=,, 0 ,, 0 ,,,,,,
BC Use User HTab Curves=0
BC User HTab FreeFlow(D)= 0

Type RM Length L Ch R = 1 ,0.6100  ,48.71,49.33,49.77
BEGIN DESCRIPTION:
DS of Corduroy Brook Nature Trail 1 Bridge - CB10 (SEM 2019)
END DESCRIPTION:
XS GIS Cut Line= 4
597918.2483035985421488.55248309597864.3394035995421503.10458309
597842.5112035985421512.03438309597785.2949035985421525.59428309
#Sta/Elev= 30
       0   74.71    2.99   74.82    6.98    73.7    8.97   72.81   12.96   70.46
   14.96      70   18.95   69.77    32.9   69.66   38.89   69.87   61.04   69.65
   64.29    68.4   66.23   66.84   66.75   67.02   67.43   66.51   69.12   66.18
      71    66.3   73.62   67.42   75.11   67.79   78.44   68.37   81.42   68.26
    86.4   68.61   89.39   68.21   93.38   69.62   96.37   69.96  111.31   69.97
  122.28   72.88  123.27   73.06  128.26   73.05  134.24   74.83  138.22   75.28
#Mann= 3 , 0 , 0
       0     .06       0   66.75     .04       0   75.11     .06       0
Bank Sta=66.75,75.11
XS Rating Curve= 0 ,0
Exp/Cntr=0.3,0.1

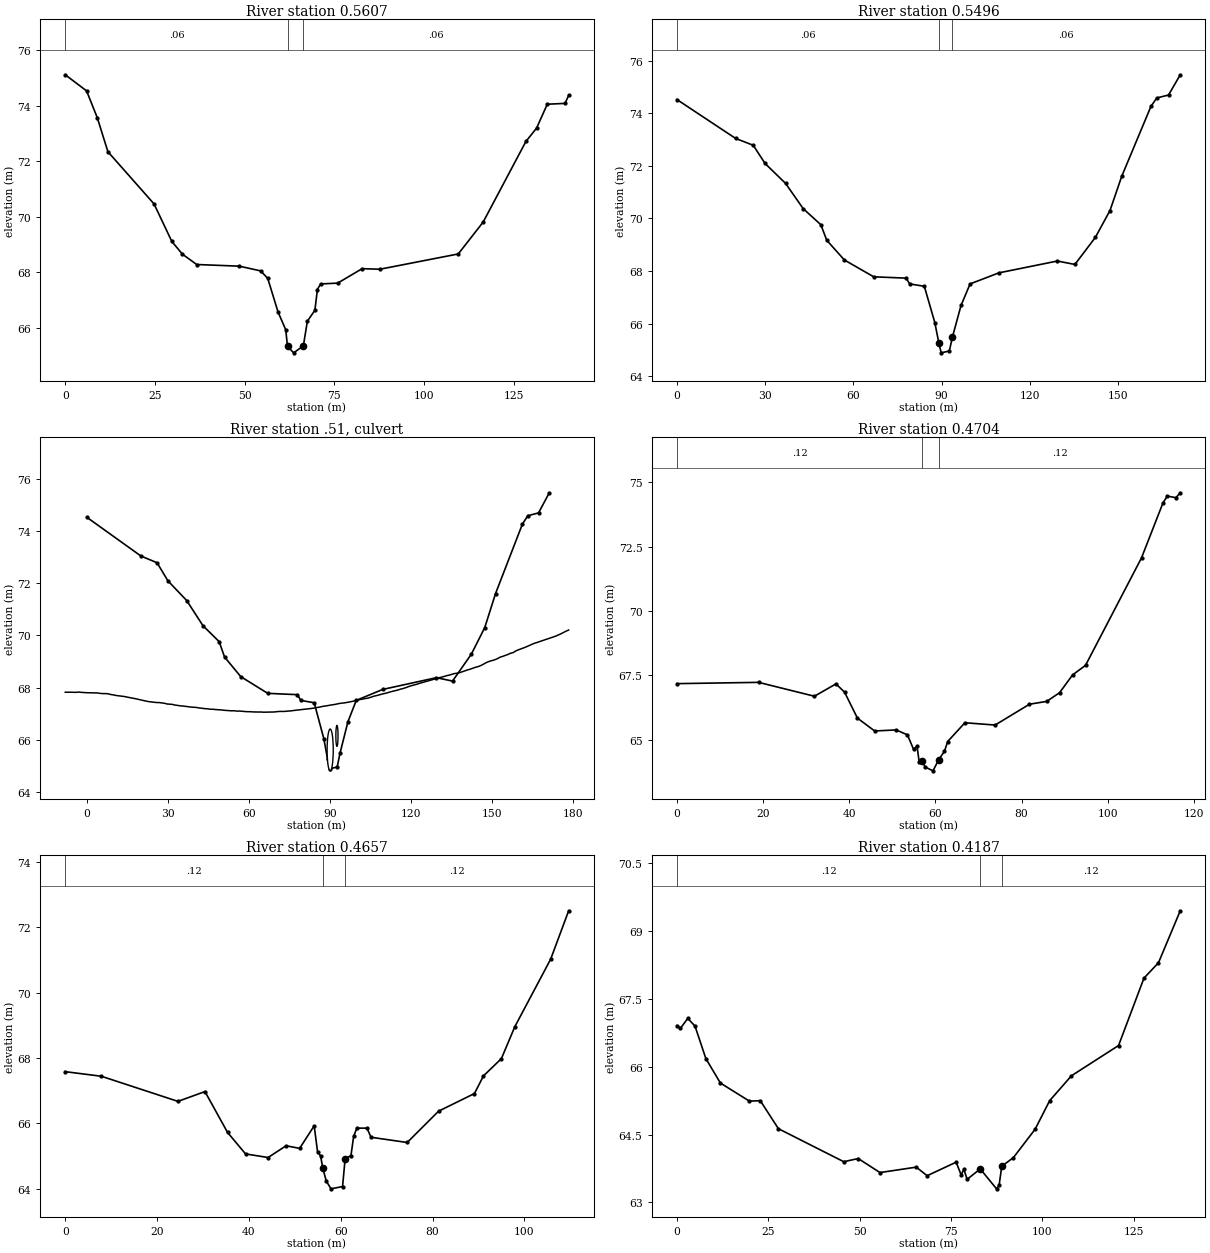
Type RM Length L Ch R = 1 ,0.5607  ,12.44,11.04,9.57
BEGIN DESCRIPTION:
CB09 (SEM 2019)
END DESCRIPTION:
XS GIS Cut Line= 4
597908.9879035985421442.25038309597862.0243035985421454.48738309
597834.2430035985421463.74778309597785.6257035985421503.10458309
#Sta/Elev= 30
       0   75.11    5.94   74.53    8.91   73.57   11.89   72.34   24.76   70.46
   29.71   69.11   32.68   68.65   36.65   68.28   48.53   68.22   54.49   68.05
   56.46   67.78   59.33   66.57   61.48   65.93   61.97   65.33   63.69    65.1
   66.39   65.35   67.51   66.24    69.6   66.63   70.31   67.38   71.19   67.58
   75.96   67.61   82.78   68.13   87.74   68.11  109.59   68.66  116.54   69.81
  128.45   72.71  131.43   73.19  134.41   74.05  139.37   74.08  140.37   74.37
#Mann= 3 , 0 , 0
       0     .06       0   61.97     .04       0   66.39     .06       0
Bank Sta=61.97,66.39
XS Rating Curve= 0 ,0
Exp/Cntr=0.3,0.1

Type RM Length L Ch R = 1 ,0.5496  ,80.24,79.27,78.62
BEGIN DESCRIPTION:
US of Lincoln Road Culvert - CB08 (SEM 2019)
END DESCRIPTION:
XS GIS Cut Line= 4
597923.7570035985421407.58288309597851.9886035985421440.32518309
597834.1292035985421457.19238309597777.5744035985421494.23408309
#Sta/Elev= 30
       0   74.52   19.97   73.04   25.96   72.78   29.96   72.09   36.95   71.33
   42.94   70.37   48.93   69.76   50.93   69.17   56.92   68.42    66.9   67.78
   77.89   67.73   79.12   67.51   84.09   67.42   87.66   66.04   89.05   65.25
   89.83   64.89   92.59   64.96   93.62   65.48   96.56   66.69   99.64   67.51
  109.42   67.93   129.3   68.38  135.26   68.25  142.22   69.28  147.19    70.3
  151.17    71.6  161.11   74.26   163.1   74.58  167.08   74.69  171.06   75.46
#Mann= 3 , 0 , 0
       0     .06       0   89.05     .04       0   93.62     .06       0
Bank Sta=89.05,93.62
XS Rating Curve= 0 ,0
Exp/Cntr=0.3,0.1

Type RM Length L Ch R = 2 ,.51     ,,,
Node Photo=.\Photos\CB-CR-2.JPG
BEGIN DESCRIPTION:
Lincoln Road Culvert
END DESCRIPTION:
Node Name=CB-CR-2
Bridge Culvert--1,0,-1,-1, 0
Deck Dist Width WeirC Skew NumUp NumDn MinLoCord MaxHiCord MaxSubmerge Is_Ogee
16,24,1.4,0, 189, 189, , , 0.98, 0, 3,3,,
      -8 -7.0084 -6.0168-5.02521-4.03361-3.04201-2.05042-1.05882   -.067 .924368
1.9159642.9075613.8991574.890754 5.882356.8739477.865543 8.857149.84873610.84033
11.8319312.8235313.8151214.8067215.7983116.7899117.78151 18.7731 19.7647 20.7563
21.7478922.7394923.7310924.7226825.7142826.7058827.6974728.6890729.6806630.67226
31.6638632.6554533.6470534.6386535.6302536.6218437.6134438.6050339.5966340.58823
41.5798242.5714243.5630144.5546145.54621 46.5378 47.5294  48.52149.5125950.50419
51.4957852.4873853.4789854.4705855.4621756.4537757.4453758.4369659.4285660.42015
61.4117562.4033563.3949464.3865465.3781466.3697467.3613368.3529369.3445270.33612
71.3277172.3193173.3109174.30251 75.2941 76.285777.2772978.2688979.2604980.25208
81.2436882.2352883.2268884.2184785.2100786.2016687.1932688.1848589.1764590.16805
91.1596592.1512493.1428494.1344395.1260396.1176297.1092298.1008299.09241 100.084
101.0756102.0672103.0625104.0579105.0532106.0486107.0439108.0393109.0346110.0299
111.0253112.0206 113.016114.0113115.0066 116.002116.9973117.9927 118.988119.9834
120.9787 121.974122.9694123.9647124.9601125.9554126.9508127.9461128.9414129.9368
130.9321131.9275132.9228133.9181134.9135135.9088136.9042137.8995138.8949139.8902
140.8855141.8809142.8762143.8716144.8669145.8622146.8576147.8529148.8483149.8436
 150.839151.8343152.8115153.7888 154.766155.7433156.7205157.6978 158.675159.6522
160.6295161.6067 162.584163.5612164.5384165.5157166.4929167.4702168.4474169.4247
170.4019171.3791172.3564173.3336174.3109175.2881176.2653177.2426178.2198
 67.8232 67.8231 67.8232 67.8185  67.818 67.8296 67.8179 67.8108 67.8042 67.8024
 67.7998 67.7979 67.7953  67.779 67.7707  67.771 67.7624 67.7356 67.7198 67.6979
  67.686 67.6701 67.6595 67.6375 67.6165 67.5971 67.5795 67.5575 67.5331 67.5095
 67.4862 67.4651 67.4521 67.4424 67.4288 67.4274 67.4147 67.3998 67.3728 67.3664
 67.3566 67.3298 67.3173 67.3004 67.2931 67.2781 67.2667 67.2538 67.2462 67.2393
 67.2196 67.2104  67.194 67.1908 67.1722 67.1709 67.1604 67.1525  67.147 67.1342
 67.1284 67.1187 67.1105 67.1143 67.0996 67.1026  67.092 67.0844 67.0776 67.0779
 67.0689 67.0651 67.0649  67.066 67.0584 67.0595 67.0623 67.0635 67.0669 67.0799
 67.0871 67.0883 67.0886 67.1012 67.1069 67.1218 67.1335 67.1448 67.1572 67.1706
 67.1776 67.1915 67.2032 67.2227 67.2382 67.2559 67.2799 67.2958 67.3118 67.3322
 67.3457 67.3643 67.3873 67.4038 67.4134 67.4298 67.4478 67.4693 67.4922 67.5162
 67.5433 67.5643 67.5815 67.5997 67.6311  67.667 67.6905 67.7179 67.7486  67.771
 67.7965 67.8295 67.8568 67.8795 67.9059 67.9399 67.9664 67.9978 68.0385 68.0719
  68.099 68.1262 68.1615 68.1891 68.2191 68.2484 68.2771 68.3085  68.337 68.3688
 68.3948 68.4192 68.4529 68.4749 68.5077 68.5364 68.5521 68.5728 68.6092 68.6475
 68.6793 68.7091  68.745 68.7821 68.8088 68.8513 68.9087 68.9627 69.0039 69.0321
 69.0645  69.107 69.1634 69.1953 69.2333 69.2686 69.3165 69.3403 69.4059 69.4474
 69.4838 69.5228 69.5625 69.6094 69.6531 69.6953 69.7269 69.7639 69.7964 69.8311
 69.8658 69.9015 69.9365 69.9672 70.0118 70.0561 70.1086 70.1607 70.2059
      -3 -2.0084 -1.0168   -.025.96638581.9579822.9495793.9411754.9327725.924368
6.9159657.9075618.8991589.89075410.8823511.8739512.8655413.8571414.8487415.84033
16.8319317.8235218.8151219.8067220.7983221.7899122.78151 23.7731 24.7647 25.7563
26.7478927.7394928.7310929.7226830.7142831.7058832.6974733.6890734.6806635.67226
36.6638637.6554538.6470539.6386540.6302541.6218442.6134443.6050344.5966345.58823
46.5798247.5714248.5630149.5546150.54621 51.5378 52.5294  53.52154.5125955.50419
56.4957857.4873858.4789859.4705860.4621761.4537762.4453763.4369664.4285665.42015
66.4117567.4033568.3949469.3865470.3781471.3697472.3613373.3529374.3445275.33612
76.3277177.3193178.3109179.30251 80.2941 81.285782.2772983.2688984.2604985.25208
86.2436887.2352888.2268889.2184790.2100791.2016692.1932693.1848594.1764595.16805
96.1596597.1512498.1428499.13443 100.126101.1176102.1092103.1008104.0924 105.084
106.0756107.0672108.0625109.0579110.0532111.0486112.0439113.0393114.0346115.0299
116.0253117.0206 118.016119.0113120.0066 121.002121.9973122.9927 123.988124.9834
125.9787 126.974127.9694128.9647129.9601130.9554131.9507132.9461133.9414134.9368
135.9321136.9275137.9228138.9181139.9135140.9088141.9042142.8995143.8949144.8902
145.8855146.8809147.8762148.8716149.8669150.8622151.8576152.8529153.8483154.8436
 155.839156.8343157.8115158.7888 159.766160.7433161.7205162.6978 163.675164.6522
165.6295166.6067 167.584168.5612169.5384170.5157171.4929172.4702173.4474174.4247
175.4019176.3791177.3564178.3336179.3109180.2881181.2653182.2426183.2198
 67.8232 67.8231 67.8232 67.8185  67.818 67.8296 67.8179 67.8108 67.8042 67.8024
 67.7998 67.7979 67.7953  67.779 67.7707  67.771 67.7624 67.7356 67.7198 67.6979
  67.686 67.6701 67.6595 67.6375 67.6165 67.5971 67.5795 67.5575 67.5331 67.5095
 67.4862 67.4651 67.4521 67.4424 67.4288 67.4274 67.4147 67.3998 67.3728 67.3664
 67.3566 67.3298 67.3173 67.3004 67.2931 67.2781 67.2667 67.2538 67.2462 67.2393
 67.2196 67.2104  67.194 67.1908 67.1722 67.1709 67.1604 67.1525  67.147 67.1342
 67.1284 67.1187 67.1105 67.1143 67.0996 67.1026  67.092 67.0844 67.0776 67.0779
 67.0689 67.0651 67.0649  67.066 67.0584 67.0595 67.0623 67.0635 67.0669 67.0799
 67.0871 67.0883 67.0886 67.1012 67.1069 67.1218 67.1335 67.1448 67.1572 67.1706
 67.1776 67.1915 67.2032 67.2227 67.2382 67.2559 67.2799 67.2958 67.3118 67.3322
 67.3457 67.3643 67.3873 67.4038 67.4134 67.4298 67.4478 67.4693 67.4922 67.5162
 67.5433 67.5643 67.5815 67.5997 67.6311  67.667 67.6905 67.7179 67.7486  67.771
 67.7965 67.8295 67.8568 67.8795 67.9059 67.9399 67.9664 67.9978 68.0385 68.0719
  68.099 68.1262 68.1615 68.1891 68.2191 68.2484 68.2771 68.3085  68.337 68.3688
 68.3948 68.4192 68.4529 68.4749 68.5077 68.5364 68.5521 68.5728 68.6092 68.6475
 68.6793 68.7091  68.745 68.7821 68.8088 68.8513 68.9087 68.9627 69.0039 69.0321
 69.0645  69.107 69.1634 69.1953 69.2333 69.2686 69.3165 69.3403 69.4059 69.4474
 69.4838 69.5228 69.5625 69.6094 69.6531 69.6953 69.7269 69.7639 69.7964 69.8311
 69.8658 69.9015 69.9365 69.9672 70.0118 70.0561 70.1086 70.1607 70.2059
BR Coef=-1 , 0 , 0 ,, 0 ,,,0.8,-1,,0,
WSPro=,,,, 1 ,,,, 0 ,,,, 0 ,,,,-1 ,-1 ,-1 , 0 , 0 , 0 , 0 , 0
Culvert=3,1.6,2.27,75,0.024,0.9,1,36,1,64.813,90,64.488,58,Culvert #1  , 0 ,1.9
      90      58
BC Culvert Barrel=1,Barrel 1,0
Culvert Bottom n=0.024
Culvert=1,0.8,,75,0.024,0.9,1,2,3,65.752,92.5,65.39,60.5,Culvert #2  , 0 ,1.9
    92.5    60.5
BC Culvert Barrel=1,Barrel 1,0
Culvert Bottom n=0.024
BC Design=,, 0 ,, 0 ,,,,,,
BC Use User HTab Curves=0
BC User HTab FreeFlow(D)= 0

Type RM Length L Ch R = 1 ,0.4704  ,5.18,4.61,3.98
BEGIN DESCRIPTION:
DS of Lincoln Road Culvert - CB07 (SEM 2019)
END DESCRIPTION:
XS GIS Cut Line= 4
597834.8272035985421378.32578309597785.2178035985421393.53938309
597776.2660035985421406.76298309597758.4948035985421452.40928309
#Sta/Elev= 30
       0   67.18   18.96   67.23   31.93   66.69   36.92   67.17   38.92   66.85
   41.91   65.84    45.9   65.34   50.89   65.38   53.51   65.19   54.96   64.62
   55.75   64.75   56.23   64.15   56.96   64.18    57.6   63.94   59.45   63.79
   60.76   64.22   62.11   64.55   62.86   64.93   66.86   65.66   73.86   65.57
   81.85   66.38   85.85   66.49   88.85   66.83   91.85   67.52   94.85   67.89
  107.85   72.07  112.84   74.21  113.84   74.47  115.84   74.41  116.84    74.6
#Mann= 3 , 0 , 0
       0     .12       0   56.96     .04       0   60.76     .12       0
Bank Sta=56.96,60.76
XS Rating Curve= 0 ,0
Exp/Cntr=0.3,0.1

Type RM Length L Ch R = 1 ,0.4657  ,47.56,47.07,46.8
BEGIN DESCRIPTION:
CB06 (SEM 2019)
END DESCRIPTION:
XS GIS Cut Line= 4
597823.9793035985421363.11218309597780.3230035985421389.57058309
597773.3556035985421405.70468309597755.1875035995421442.48738309
#Sta/Elev= 30
       0   67.58    7.85   67.44   24.54   66.67   30.43   66.97   35.34   65.72
   39.27   65.06   44.18   64.95    48.1   65.31   51.05   65.23   54.22   65.92
   54.96   65.12   55.61      65    56.1   64.62   56.85   64.23   57.88   63.99
    60.4   64.06   60.96   64.91   62.23   65.01   62.82    65.6   63.51   65.85
   65.71   65.85   66.61   65.57   74.48   65.41   81.32   66.37   89.13   66.91
   91.09   67.45      95   67.98   97.93   68.96  105.74   71.03  109.65   72.51
#Mann= 3 , 0 , 0
       0     .12       0    56.1     .04       0   60.96     .12       0
Bank Sta=56.1,60.96
XS Rating Curve= 0 ,0
Exp/Cntr=0.3,0.1

Type RM Length L Ch R = 1 ,0.4187  ,85.39,87.4,86
BEGIN DESCRIPTION:
CB05 (SEM 2019)
END DESCRIPTION:
XS GIS Cut Line= 4
597804.1355035985421332.02358309597736.7107035985421368.00148309
597733.0066035995421383.21508309597737.9896035995421428.59668309
#Sta/Elev= 30
       0   66.91     .99   66.85    2.98   67.07    4.96    66.9    7.94   66.18
   11.91   65.64   19.85   65.24   22.83   65.25   27.79   64.63   45.66    63.9
   49.63   63.97   55.58   63.66   65.51   63.78   68.48   63.59   76.42   63.89
   77.78   63.61   78.55   63.73   79.42   63.51   83.01   63.74   87.48    63.3
   88.18   63.38    88.9    63.8   92.08   63.99   98.04   64.62  102.01   65.25
  107.96    65.8  120.86   66.47  127.81   67.96  131.78    68.3  137.74   69.45
#Mann= 3 , 0 , 0
       0     .12       0   83.01     .04       0    88.9     .12       0
Bank Sta=83.01,88.9
XS Rating Curve= 0 ,0
Exp/Cntr=0.3,0.1