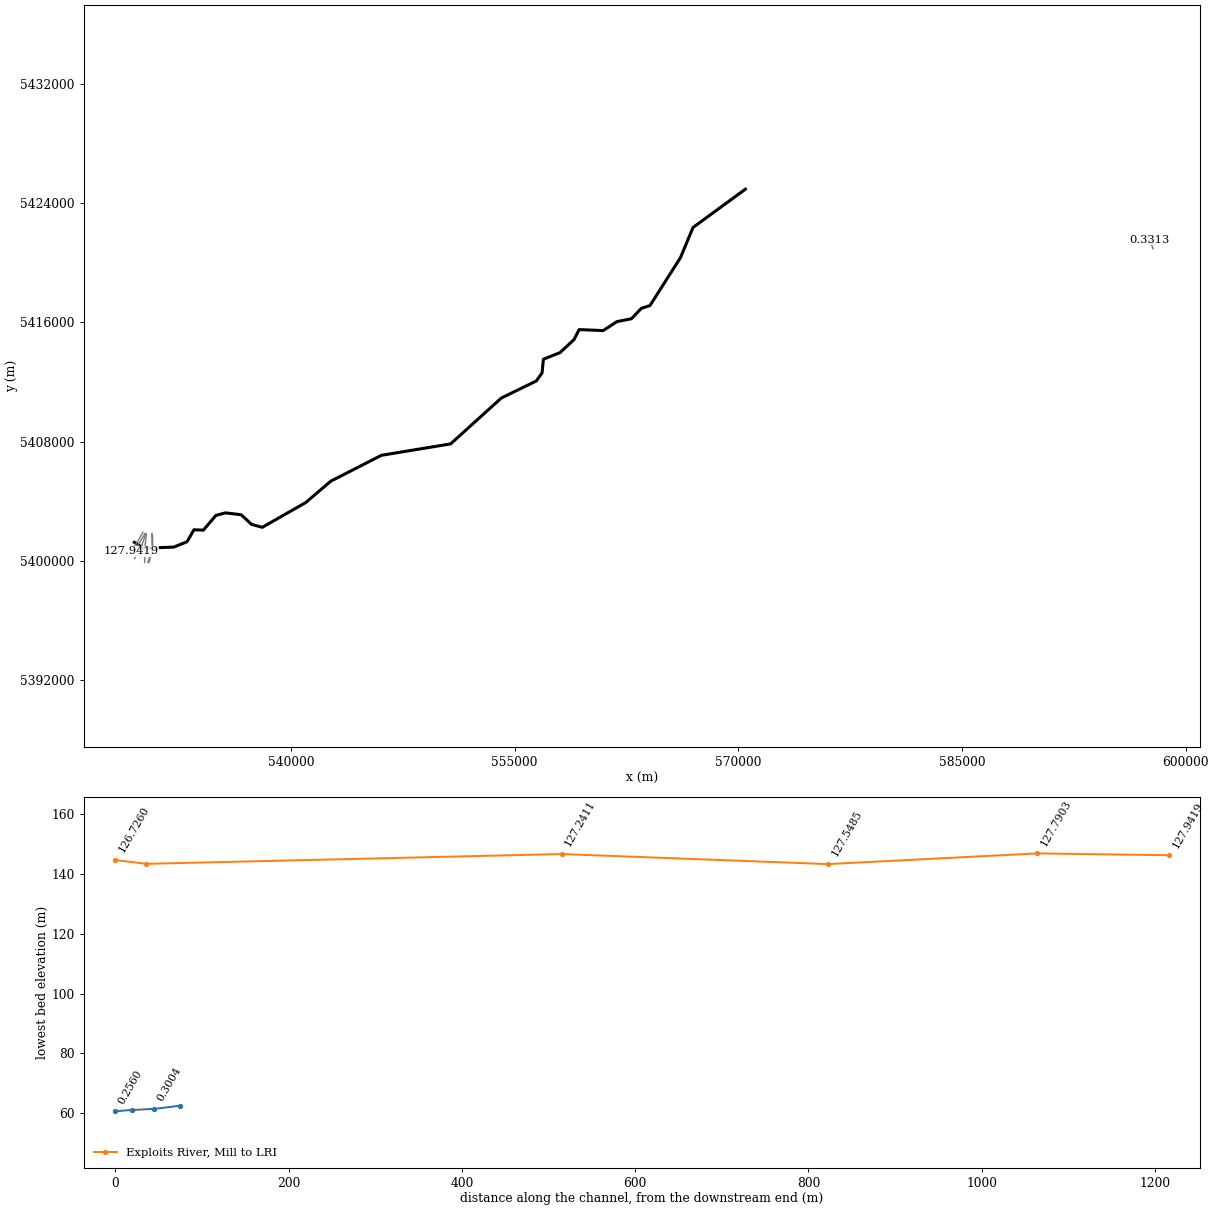
HEC-RAS study Exploits_FMM.prj: Exploits_FMM

--- Exploits_FMM.g01 (geometry) --- (continued)

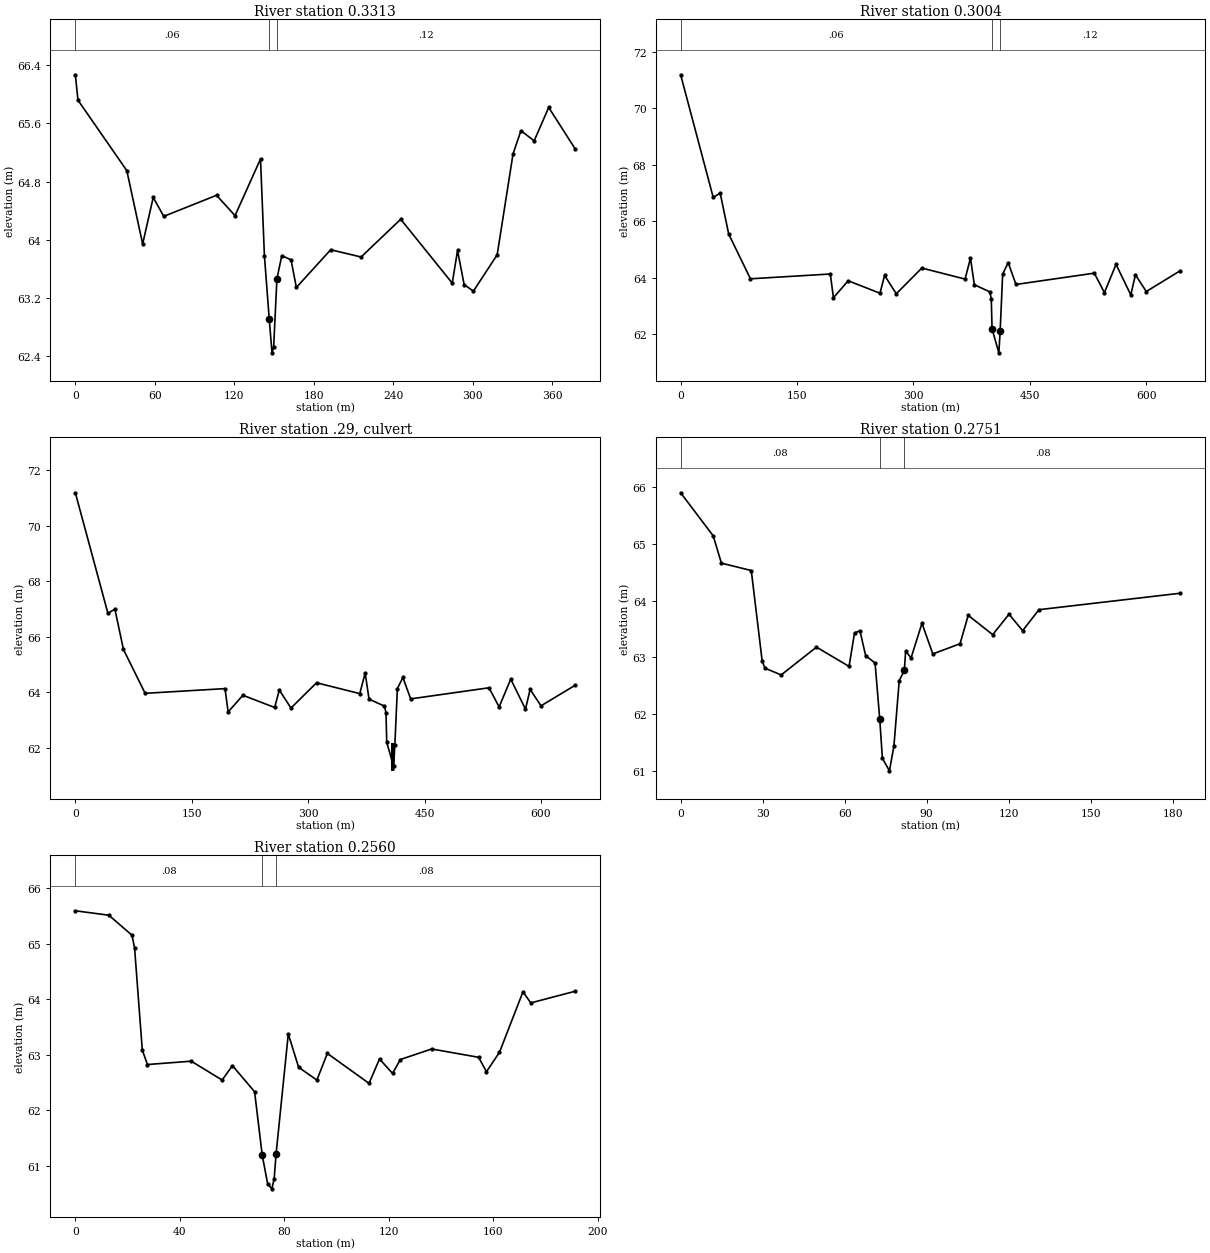
Type RM Length L Ch R = 1 ,0.3313  ,31.16,30.87,30.32
BEGIN DESCRIPTION:
CB04 (SEM 2019)
END DESCRIPTION:
XS GIS Cut Line= 4
  597808.7657036 5421245.3723831  597685.7342036 5421306.8881831
  597676.4738036 5421322.7631831  597580.9057036 5421522.6267831
#Sta/Elev= 30
       0   66.27    1.99   65.92   38.87   64.95   50.83   63.94   58.81   64.58
   66.78   64.32  106.65   64.61  120.61   64.33  139.85   65.11  142.79   63.78
  146.41   62.91  148.55   62.44  149.78   62.52  152.24   63.46  155.93   63.78
  162.92   63.72  166.91   63.34  192.86   63.86  215.81   63.76  245.74   64.28
  284.66    63.4  288.66   63.85  293.64   63.38  300.63   63.29  318.59   63.79
  330.57   65.18  336.55    65.5  346.53   65.36  357.51   65.82  377.47   65.25
#Mann= 3 , 0 , 0
       0     .06       0  146.41     .04       0  152.24     .12       0
#XS Ineff= 2 , 0
           59.07   64.57
Permanent Ineff=
       F       F
Bank Sta=146.41,152.24
XS Rating Curve= 0 ,0
Exp/Cntr=0.3,0.1

Type RM Length L Ch R = 1 ,0.3004  ,25.74,25.32,24.69
BEGIN DESCRIPTION:
US of Corduroy Brook Unnamed Road Culvert - CB03 (SEM 2019)
END DESCRIPTION:
XS GIS Cut Line= 5
  597809.7725036 5420929.1999831  597683.7031036 5421225.2477831
  597653.9842036 5421298.9505831  597647.3696036 5421315.4870831
  597566.5917036 5421525.3784831
#Sta/Elev= 30
       0   71.19   41.97   66.85   50.96      67   61.96   65.55   89.94   63.97
  192.86   64.14  196.86    63.3  215.85    63.9  256.82   63.46  262.81   64.09
   277.8   63.44  310.78   64.35  366.47   63.96  373.43    64.7   378.4   63.76
  398.26   63.51  400.25   63.27  401.24    62.2  410.01   61.35  411.68   62.12
  414.91   64.14  422.05   64.54  432.05   63.77     533   64.17     546   63.48
  560.99   64.48  579.98    63.4  585.98   64.11  599.97   63.52  643.95   64.26
#Mann= 3 , 0 , 0
       0     .06       0  401.24     .04       0  411.68     .12       0
Bank Sta=401.24,411.68
XS Rating Curve= 0 ,0
Exp/Cntr=0.3,0.1

Type RM Length L Ch R = 2 ,.29     ,,,
Node Photo=.\Photos\CB-CR-1.JPG
BEGIN DESCRIPTION:
Corduroy Brook Unnamed Road Culvert
END DESCRIPTION:
Node Name=CB-CR-1
Bridge Culvert--1,0,-1,-1, 0
Deck Dist Width WeirC Skew NumUp NumDn MinLoCord MaxHiCord MaxSubmerge Is_Ogee
8,7,1.4,0, 500, 500, , , 0.98, 0, 3,3,,
     -20-19.0024-18.0048-17.0072-16.0097-15.0121-14.0145 -13.017-12.0194-11.0218
-10.0243-9.02674-8.02917 -7.0316-6.03403-5.03646-4.03889-3.04133-2.04376-1.04619
   -.048 .9489451.9465142.9440833.941652 4.939225.9367896.9343587.9319278.929496
9.92706410.92463 11.922212.9197713.9173414.9149115.9124816.9100517.9076218.90518
19.9027520.9003221.8978922.8954623.89303 24.890625.8881626.88573 27.883328.88087
29.8784430.8760131.8534832.8309633.80843 34.785935.7633836.7408537.71833 38.6958
39.6732740.6507541.62822 42.605743.5831744.5606445.5381246.5155947.4930648.47054
49.4480150.4254951.4029652.3804453.3579154.3353855.3128556.29033 57.267858.24528
59.2227560.20023 61.177762.1551763.1326564.1101265.0875966.0650767.0425468.02002
68.9974969.9749670.9524471.9299172.9073973.8963674.8853475.87432 76.863377.85227
78.8412579.8302380.8192181.8081882.7971683.7861484.7751285.7640986.7530787.74205
88.73103   89.7290.7089891.6979692.6869493.6759194.6648995.6538796.6428597.63182
 98.620899.60978100.5988101.5877102.5767103.5657104.5547105.5436106.5326107.5216
108.5106109.4996110.4885111.4775112.4665113.4555114.4444115.4334116.4224117.4114
118.4004119.3893120.3783121.3673122.3563123.3452124.3342125.3232126.3122127.3011
128.2901129.2791130.2681131.2571 132.246 133.235 134.224 135.213 136.202137.1909
138.1799139.1689140.1579141.1468142.1358143.1248144.1138145.1028146.0917147.0807
 148.067149.0534150.0398151.0261152.0125152.9988153.9852154.9715155.9579156.9442
157.9306158.9169159.9033160.8896 161.876162.8624163.8487164.8351165.8214166.8078
167.7941168.7805169.7668170.7532171.7395172.7259173.7122174.6986 175.685176.6713
177.6577 178.644179.6304180.6167181.6031182.5894183.5889184.5885 185.588186.5875
 187.587188.5865 189.586190.5855 191.585192.5845 193.584194.5835 195.583196.5825
 197.582198.5815 199.581200.5805  201.58202.5795203.5791204.5786205.5781206.5776
207.5771208.5766209.5761210.5756211.5751212.5746213.5741214.5736215.5731216.5726
217.5721218.5716219.5711220.5706221.5701222.5696223.5692224.5686225.5682226.5677
227.5672228.5667229.5662230.5657231.5652232.5647233.5642234.5637235.5632236.5627
237.5622238.5617239.5612240.5607241.5602242.5598243.5592244.5588245.5583246.5578
247.5573248.5568249.5563250.5558251.5553252.5548253.5543254.5538255.5533256.5528
257.5523258.5518259.5513260.5508261.5504262.5498263.5493264.5489265.5484266.5479
267.5474268.5469269.5464270.5459271.5454272.5449273.5444274.5439275.5434276.5429
277.5424278.5419279.5414 280.541281.5404282.5399283.5395 284.539285.5385 286.538
287.5375 288.537289.5365 290.536291.5355 292.535293.5345294.5284295.5224296.5164
297.5103298.5042299.4982300.4921301.4861  302.48 303.474304.4679305.4619306.4558
307.4498308.4437309.4377310.4316311.4256312.4195313.4135314.4074315.4014316.3953
317.3893318.3832319.3771320.3711321.3651 322.359323.3529324.3469325.3408326.3348
327.3287328.3227329.3166330.3106331.3045332.2985333.2924334.2864335.2803336.2743
337.2682338.2621339.2561340.2501 341.244342.2379343.2319344.2258345.2198346.2137
347.2077348.2016349.1956350.1895351.1835352.1774353.1714354.1653355.1593356.1532
357.1472358.1411 359.135 360.129 361.123362.1169363.1108364.1048365.0988366.0927
367.0866368.0806369.0745370.0685371.0624372.0564373.0503374.0443375.0382376.0322
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    -355-354.002-353.004-352.007-351.009-350.012-349.014-348.017-347.019-346.021
-345.024-344.026-343.029-342.031-341.034-340.036-339.038-338.041-337.043-336.046
-335.048-334.051-333.053-332.055-331.058 -330.06-329.063-328.065-327.068 -326.07
-325.072-324.075-323.077 -322.08-321.082-320.085-319.087 -318.09-317.092-316.094
-315.097-314.099-313.102-312.104-311.107-310.109-309.111-308.114-307.116-306.119
-305.121-304.124-303.146-302.169-301.191-300.214-299.236-298.259-297.281-296.304
-295.326-294.349-293.371-292.394-291.416-290.439-289.461-288.484-287.506-286.529
-285.552-284.574-283.597-282.619-281.642-280.664-279.687-278.709-277.732-276.754
-275.777-274.799-273.822-272.844-271.867-270.889-269.912-268.934-267.957 -266.98
-266.002-265.025-264.047 -263.07-262.092-261.103-260.114-259.125-258.136-257.147
-256.158-255.169 -254.18-253.191-252.202-251.213-250.224-249.235-248.246-247.257
-246.269 -245.28-244.291-243.302-242.313-241.324-240.335-239.346-238.357-237.368
-236.379 -235.39-234.401-233.412-232.423-231.434-230.445-229.456-228.467-227.478
-226.489  -225.5-224.511-223.522-222.533-221.544-220.555-219.566-218.577-217.588
-216.599 -215.61-214.621-213.632-212.643-211.654-210.665-209.676-208.687-207.698
-206.709 -205.72-204.731-203.742-202.754-201.765-200.776-199.787-198.798-197.809
 -196.82-195.831-194.842-193.853-192.864-191.875-190.886-189.897-188.908-187.919
-186.933-185.946 -184.96-183.973-182.987-182.001-181.014-180.028-179.042-178.055
-177.069-176.083-175.096 -174.11-173.124-172.137-171.151-170.164-169.178-168.192
-167.205-166.219-165.233-164.246 -163.26-162.274-161.287-160.301-159.315-158.328
-157.342-156.356-155.369-154.383-153.396 -152.41-151.411-150.411-149.412-148.412
-147.413-146.413-145.414-144.414-143.415-142.415-141.416-140.416-139.417-138.417
-137.418-136.418-135.419-134.419 -133.42 -132.42 -131.42-130.421-129.421-128.422
-127.422-126.423-125.423-124.424-123.424-122.425-121.425-120.426-119.426-118.427
-117.427-116.428-115.428-114.429-113.429 -112.43 -111.43-110.431-109.431-108.432
-107.432-106.433-105.433-104.434-103.434-102.435-101.435-100.436-99.4367-98.4372
-97.4377-96.4382-95.4387-94.4392-93.4397-92.4402-91.4407-90.4412-89.4417-88.4422
-87.4427-86.4432-85.4437-84.4442-83.4447-82.4452-81.4456-80.4461-79.4466-78.4471
-77.4476-76.4481-75.4486-74.4491-73.4496-72.4501-71.4506-70.4511-69.4516-68.4521
-67.4526-66.4531-65.4536-64.4541-63.4546-62.4551-61.4556 -60.456-59.4565 -58.457
-57.4575 -56.458-55.4585 -54.459-53.4595  -52.46-51.4605 -50.461-49.4615 -48.462
-47.4625 -46.463-45.4635 -44.464-43.4645 -42.465-41.4654-40.4715-39.4776-38.4836
-37.4897-36.4957-35.5018-34.5078-33.5139-32.5199 -31.526 -30.532-29.5381-28.5441
-27.5502-26.5562-25.5623-24.5683-23.5744-22.5804-21.5865-20.5925-19.5986-18.6047
-17.6107-16.6168-15.6228-14.6289-13.6349 -12.641 -11.647-10.6531-9.65916-8.66521
-7.67127-6.67732-5.68337-4.68942-3.69548-2.70153-1.70758-.713638.28030951.274257
2.2682053.262153  4.25615.2500486.2439967.2379438.2318919.22583910.2197911.21373
12.2076813.2016314.1955815.1895216.1834717.1774218.1713719.1653220.1592621.15321
22.1471623.1411124.13505  25.12926.12295 27.116928.1108529.1047930.0987431.09269
32.0866433.0805834.0745335.0684836.0624337.0563738.0503239.0442740.0382241.03217
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BR Coef=-1 , 0 , 0 ,, 0 ,,,0.8,-1,,0,
WSPro=,,,, 1 ,,,, 0 ,,,, 0 ,,,,-1 ,-1 ,-1 , 0 , 0 , 0 , 0 , 0
Multiple Barrel Culv=1,1,,15.1,0.024,0.9,1,2,3,61.1795,61.044, 2,Culvert #1  , 0 ,1.9
     408      75     410      77
BC Culvert Barrel=1,Barrel 1,0
BC Culvert Barrel=2,Barrel 2,0
Culvert Bottom n=0.024
BC Design=,, 0 ,, 0 ,,,,,,
BC Use User HTab Curves=0
BC User HTab FreeFlow(D)= 0

Type RM Length L Ch R = 1 ,0.2751  ,19.19,19.04,18.95
BEGIN DESCRIPTION:
DS of Corduroy Brook Unnamed Road Culvert - CB02 (SEM 2019)
END DESCRIPTION:
XS GIS Cut Line= 4
  597653.9842036 5421230.8202831  597628.0845036 5421292.1581831
  597624.8800036 5421307.5495831  597603.3027036 5421405.7187831
#Sta/Elev= 30
       0    65.9   11.93   65.14   14.91   64.66   25.84   64.53   29.81   62.94
   30.81   62.81   36.77   62.69   49.69   63.18   61.61   62.84    63.6   63.43
   65.59   63.47   67.67   63.03   71.12    62.9   72.82   61.92    73.8   61.22
   76.38      61   78.02   61.44   79.96   62.59   81.84   62.77    82.3   63.11
   84.29   62.99   88.27    63.6   92.25   63.06  102.21   63.24  105.19   63.74
  114.15    63.4  120.12   63.76   125.1   63.47  131.07   63.84  182.82   64.13
#Mann= 3 , 0 , 0
       0     .08       0   72.82     .04       0   81.84     .08       0
Bank Sta=72.82,81.84
XS Rating Curve= 0 ,0
Exp/Cntr=0.3,0.1

Type RM Length L Ch R = 1 ,0.2560  ,2.64,256.05,3.76
BEGIN DESCRIPTION:
CB01 (SEM 2019)
END DESCRIPTION:
XS GIS Cut Line= 4
  597643.4008036 5421231.4817831  597609.0049036 5421289.0286831
  597606.3591036 5421304.2422831  597599.3340036 5421412.8624831
#Sta/Elev= 30
       0   65.59   12.82   65.51   21.69   65.15   22.68   64.92   25.63   63.08
   27.61   62.82   44.37   62.88    56.2   62.54   60.14    62.8   68.62   62.33
   71.53   61.19   73.62   60.67   75.21   60.58   76.11   60.76   76.85   61.21
   81.52   63.37   85.48   62.77   92.47   62.54   96.47   63.02  112.44   62.48
  116.44   62.92  121.43   62.66  124.43   62.91  136.41    63.1  154.38   62.95
  157.38   62.69  162.37   63.04  171.36   64.13  174.36   63.93  191.33   64.14
#Mann= 3 , 0 , 0
       0     .08       0   71.53     .04       0   76.85     .08       0
Bank Sta=71.53,76.85
XS Rating Curve= 0 ,0
Exp/Cntr=0.3,0.1

River Reach=Exploits River  ,Mill to LRI
Reach XY= 30
     529505.8193    5401248.4164     530125.0998    5400855.3156
     532155.0009    5400929.5075     533038.3953    5401286.7458
     533501.0345    5402090.2031     534131.1524    5402064.6121
     534973.0846     5403053.452     535614.2245    5403222.6048
     536664.6494    5403098.4255     537363.8841    5402451.5754
     538084.2779     5402255.336      540993.903    5403913.7179
     542673.1556    5405346.8805     546066.8446    5407081.0669
     550710.0121    5407848.0469     554104.3327    5410918.9777
     556454.0355    5412066.3609     556838.0825    5412602.1751
     556928.8157    5413523.9647     558045.4887    5413966.5614
      558977.503    5414835.9172     559324.1648      5415510.92
     560936.4088     5415443.238     561861.7757    5416045.8583
     562831.9203    5416237.6579     563493.3974    5416933.4445
     564072.3281    5417119.9702     566118.8344    5420335.3585
      566960.304    5422356.5228     570472.2323    5424925.2875

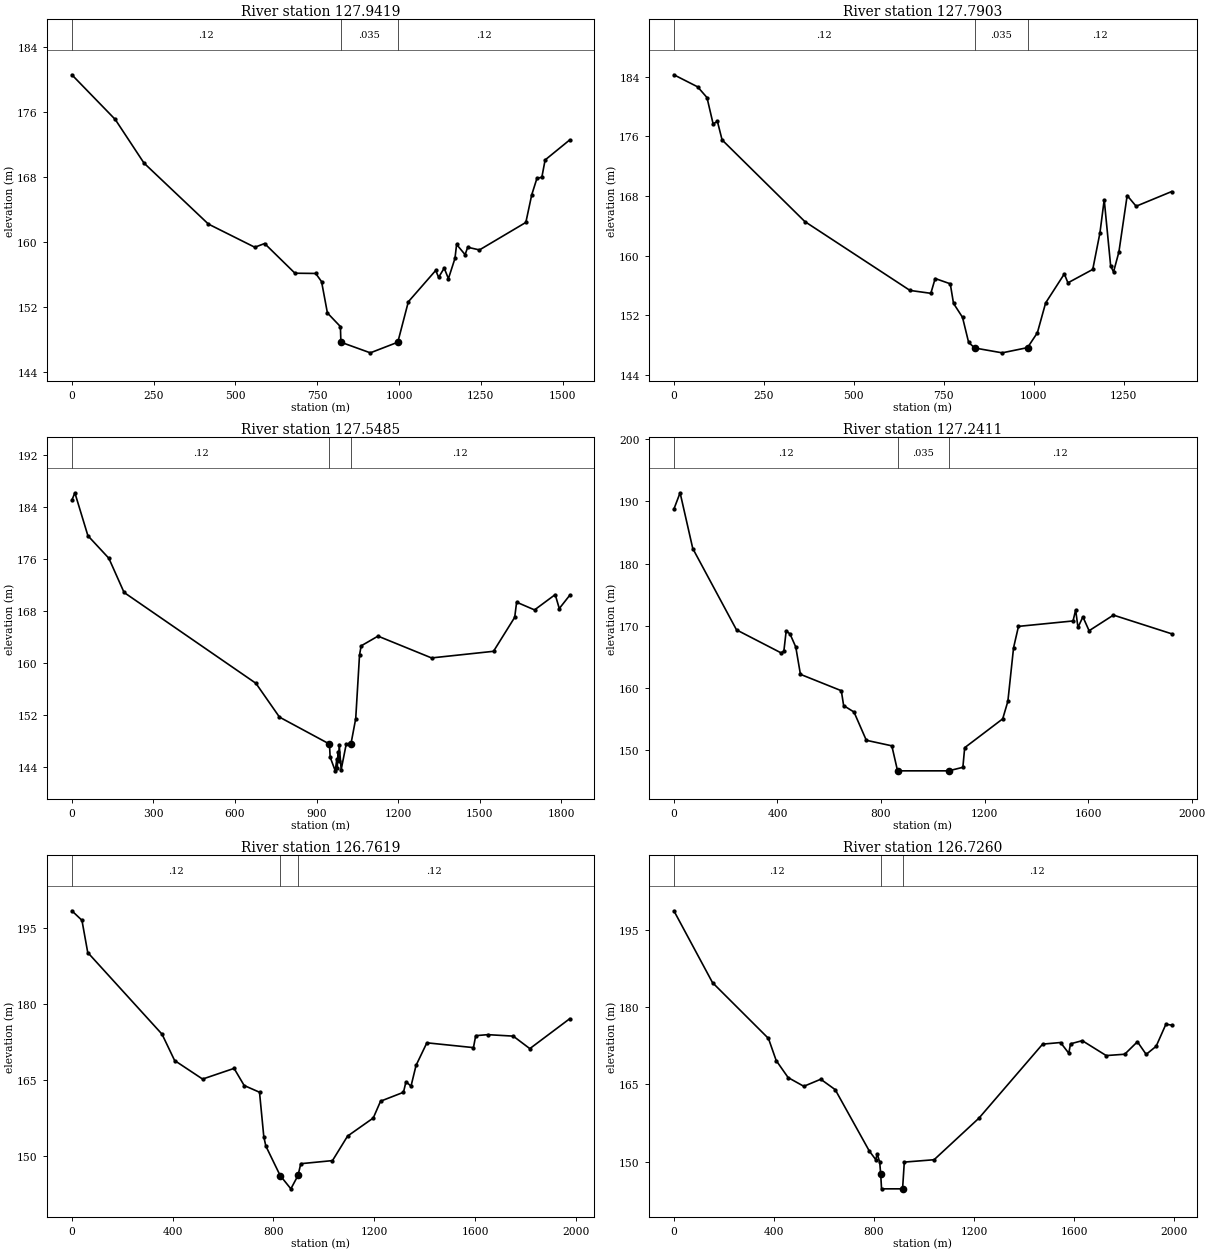
Type RM Length L Ch R = 1 ,127.9419,146.4,151.58,160.5
BEGIN DESCRIPTION:
DS of Millertown Dam
END DESCRIPTION:
XS GIS Cut Line= 6
     530083.9192    5401927.0055     529964.4462    5401719.5519
     529733.1242    5401306.5913     529706.9202    5401259.8116
     529528.2847    5401004.0531      529269.444    5400644.1052
#Sta/Elev= 30
       0   180.6  132.67  175.09  220.44  169.72  417.32   162.2  559.26  159.34
  589.25   159.8  682.03  156.14   745.5  156.11  763.37   155.1  781.25  151.24
  820.97  149.56  822.46 147.635  912.38 146.325  996.42 147.635 1028.63  152.62
 1112.27  156.48 1121.26  155.63 1138.23  156.77 1151.21  155.47 1171.18  157.97
 1176.17  159.69 1202.14  158.43 1210.12  159.34 1246.07  159.01 1387.86   162.4
 1405.84   165.8 1421.81  167.84 1436.79  167.97 1446.78   170.1 1521.67  172.56
#Mann= 3 , 0 , 0
       0     .12       0  822.46    .035       0  996.42     .12       0
Bank Sta=822.46,996.42
XS Rating Curve= 0 ,0
Exp/Cntr=0.3,0.1

Type RM Length L Ch R = 1 ,127.7903,256.39,241.84,238.63
XS GIS Cut Line= 6
     530228.0713    5401848.7729     530034.6293    5401527.7407
     529880.3172    5401271.6479     529756.9799    5401066.9604
     529631.6947    5400859.0405     529508.8178    5400668.0615
#Sta/Elev= 30
       0  184.29   65.97  182.67   91.95  181.23  108.94   177.7  120.94  178.02
  133.93  175.54  363.81  164.57   655.8  155.32  713.78  154.93  725.77  156.92
  767.74  156.21  776.74  153.58  801.72  151.71  818.71  148.34  835.69 147.585
  911.96 146.935  982.34 147.635 1009.67  149.63 1032.64  153.64 1084.58  157.54
 1094.57  156.34  1163.5  158.14 1183.42  163.03 1195.37   167.5  1213.3   158.6
 1221.27   157.8 1236.21   160.5 1259.11  168.07 1284.02  166.63 1382.62   168.6
#Mann= 3 , 0 , 0
       0     .12       0  835.69    .035       0  982.34     .12       0
Bank Sta=835.69,982.34
XS Rating Curve= 0 ,0
Exp/Cntr=0.3,0.1

Type RM Length L Ch R = 1 ,127.5485,263.94,307.43,365.77
BEGIN DESCRIPTION:
E39 (SEM 2016)
END DESCRIPTION:
XS GIS Cut Line= 6
     530276.9255    5401820.6485     530049.3458    5401178.9689
       529985.11    5400997.8514     529982.7909    5400978.3253
     529899.8657    5400847.0912     529527.6417    5400158.6539
#Sta/Elev= 30
       0  185.06      11  186.21   58.99  179.59  135.97  176.12  191.96  170.85
  676.84  156.85  763.49  151.64  947.44 147.485 949.826 145.483 968.587 143.359
 974.566 145.219 976.012 143.763 978.903 146.321 980.841 144.905  983.24 147.412
 990.385 143.5241008.937 147.467 1026.26 147.473 1043.94  151.41 1057.92   161.2
 1063.91  162.62 1125.88  164.12 1322.79  160.76 1550.69  161.78 1628.65  167.02
 1635.65  169.35 1701.62  168.16 1777.59  170.52 1792.58  168.37 1830.56  170.39
#Mann= 3 , 0 , 0
       0     .12       0  947.44    .035       0 1026.26     .12       0
Bank Sta=947.44,1026.26
XS Rating Curve= 0 ,0
Exp/Cntr=0.3,0.1

Type RM Length L Ch R = 1 ,127.2411,476.99,479.14,496.55
XS GIS Cut Line= 6
     530313.2251    5401810.2122     530225.2234    5401041.2049
     530236.9499    5400868.2961     530246.2156    5400731.6698
     530242.3029    5400674.0284      530189.454    5399895.4783
#Sta/Elev= 30
       0  188.74   23.99  191.37   72.96  182.42  241.86  169.36  413.77  165.67
  424.76  165.94  433.76  169.21  448.75  168.68  470.74  166.61  488.73  162.22
  646.64  159.59  655.63   157.2  695.61  156.17  743.25  151.63  841.75  150.74
  863.89 146.724 1061.11 146.724 1116.15  147.29 1123.12  150.44 1269.94  155.07
 1289.92  157.89  1311.9  166.49 1330.89  169.92  1541.7  170.79  1551.7  172.57
 1560.69  169.74 1579.67  171.45 1603.65  169.22 1697.57  171.73 1922.38  168.73
#Mann= 3 , 0 , 0
       0     .12       0  863.89    .035       0 1061.11     .12       0
Bank Sta=863.89,1061.11
XS Rating Curve= 0 ,0
Exp/Cntr=0.3,0.1

Type RM Length L Ch R = 1 ,126.7619,35.68,35.9,35.51
BEGIN DESCRIPTION:
02YO016 ER near Millertown - E38 (SEM 2016)
END DESCRIPTION:
XS GIS Cut Line= 4
     530674.7249    5401828.4028      530694.829    5401125.0389
     530709.7089    5400721.9466     530403.8395    5399909.5966
#Sta/Elev= 30
       0  198.35   39.98  196.47   62.97  190.11  357.82  173.98   407.8  168.78
  518.74  165.12  643.68  167.23  683.66  163.85  744.59  162.52  761.56  153.76
  769.55  151.91  826.46 146.075  868.99 143.445  897.35 146.085  908.33  148.41
 1034.13  149.02 1094.04  153.86 1195.92  157.43 1224.89  160.75 1315.79  162.51
 1325.78  164.59 1345.76  163.72 1365.74  167.82 1408.69  172.28 1593.49  171.33
 1602.48  173.69 1650.43  173.89 1751.32   173.6 1817.24  171.13 1975.07  177.02
#Mann= 3 , 0 , 0
       0     .12       0  826.46    .035       0  897.35     .12       0
Bank Sta=826.46,897.35
XS Rating Curve= 0 ,0
Exp/Cntr=0.3,0.1

Type RM Length L Ch R = 1 ,126.7260,17.2,15.76,16.12
BEGIN DESCRIPTION:
US of Exploits Bridge
END DESCRIPTION:
XS GIS Cut Line= 6
     530693.4413    5401833.9417      530729.852    5401624.7316
     530721.5725    5401296.8047     530747.1622    5400723.8137
     530604.6773    5400348.1683     530483.0029    5399892.1187
#Sta/Elev= 30
       0  198.65  154.53  184.71  378.07  173.89  408.94  169.61  456.74   166.3
  519.47  164.61  587.16  165.98  644.89  163.96  781.19  152.06  806.95  150.39
  812.88  151.49  822.77   149.9  826.73  147.56 830.144 144.725 914.189 144.725
  921.09  149.91 1040.19  150.37  1219.6  158.44 1474.06  172.79 1545.64   173.1
 1578.57  171.02 1585.56  172.85 1632.46  173.46 1728.25  170.57  1802.1  170.83
 1852.99  173.25 1887.92   170.8 1927.83  172.37 1966.75  176.64  1989.7  176.48
#Mann= 3 , 0 , 0
       0     .12       0  826.73    .035       0 914.189     .12       0
Bank Sta=826.73,914.189
XS Rating Curve= 0 ,0
Exp/Cntr=0.3,0.1