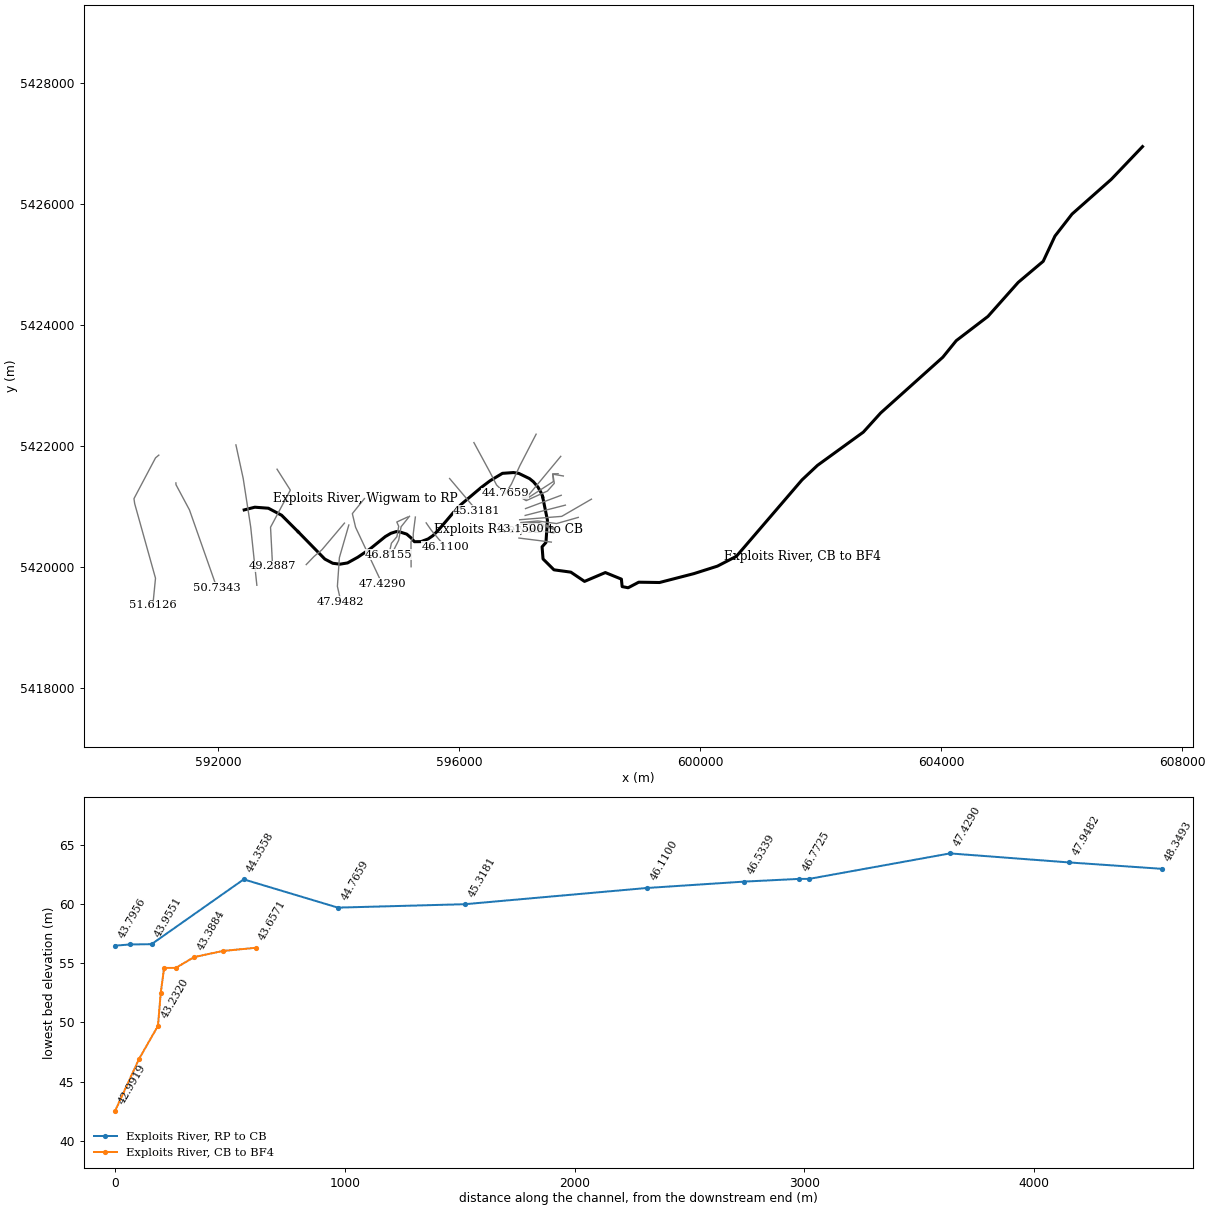
HEC-RAS study Exploits_FMM.prj: Exploits_FMM

--- Exploits_FMM.g01 (geometry) --- (continued)

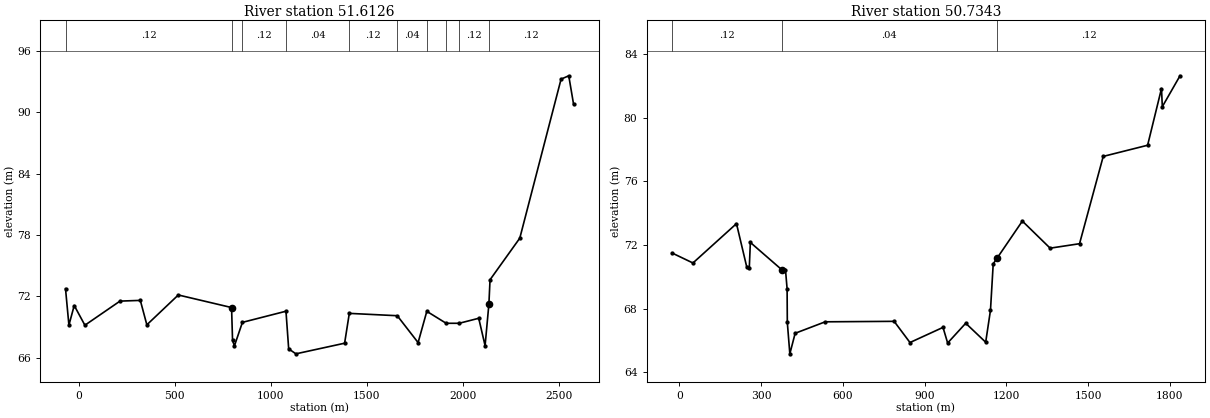
Type RM Length L Ch R = 1 ,51.6126 ,1028.2,878.28,1098.98
BEGIN DESCRIPTION:
Sandy Brook - R01A (SEM 2019)
END DESCRIPTION:
XS GIS Cut Line= 6
  591015.8073036 5421847.6606831  590961.2592036 5421802.1725831
  590603.6302036 5421128.4707831  590615.2180036 5421046.1969831
  590961.0350036 5419812.3059831  590916.9701036 5419367.6498831
#Sta/Elev= 30
     -68   72.76  -50.24   69.19  -22.62   71.11   32.96   69.18  215.73   71.54
   321.6   71.61  355.56   69.22  519.35   72.14   796.7   70.91  801.82   67.69
  811.66   67.16  853.13   69.46 1079.99   70.55 1094.08   66.87 1131.62   66.38
 1385.35   67.42 1409.79   70.34 1659.55   70.11 1768.01   67.48 1813.39   70.54
 1914.14   69.37 1981.97   69.37 2083.72   69.86  2116.8   67.18 2136.61   71.24
 2142.61   73.63 2297.55    77.7 2512.48   93.26 2552.46   93.59 2577.45   90.82
#Mann= 10 ,-1 , 0
     -68     .12       0   796.7     .04       0  853.13     .12       0
 1079.99     .04       0 1409.79     .12       0 1659.55     .04       0
 1813.39     .12       0 1914.14     .04       0 1981.97     .12       0
 2136.61     .12       0
Bank Sta=796.7,2136.61
XS Rating Curve= 0 ,0
Exp/Cntr=0.3,0.1

Type RM Length L Ch R = 1 ,50.7343 ,828.8,921.88,912.98
BEGIN DESCRIPTION:
R02 (RIS 2013)
END DESCRIPTION:
XS GIS Cut Line= 4
  591299.4412036 5421388.9714831  591301.4423036 5421358.0241831
  591524.8619036 5420941.5243831  591978.0932036 5419658.0781831
#Sta/Elev= 30
     -27    71.5   49.94   70.87  209.75   73.34  247.71    70.6   256.7   70.54
  260.69   72.16  375.13   70.46  389.54   70.46  395.53   69.25  396.33   67.14
  405.56  65.168  425.06  66.458  535.38  67.178  788.35  67.208  846.47  65.878
  967.73  66.828  984.76  65.848 1051.08  67.088 1124.36  65.898 1141.96  67.908
    1152   70.82 1166.08   71.17 1258.93    73.5 1360.87    71.8  1468.8   72.08
 1555.74   77.56 1718.64   78.26  1769.6   81.82  1772.6   80.68 1837.56   82.62
#Mann= 3 , 0 , 0
     -27     .12       0  375.13     .04       0 1166.08     .12       0
Bank Sta=375.13,1166.08
XS Rating Curve= 0 ,0
Exp/Cntr=0.3,0.1

River Reach=Exploits River  ,Wigwam to RP
Reach XY= 30
     592433.2195      5420942.03      592470.065    5420951.3545
     592482.2928    5420954.4551     592517.7109    5420963.4103
     592550.0097    5420971.5845     592554.2749    5420972.6705
     592609.5446    5420986.6564     592675.4122     5420981.714
     592704.3074    5420979.5546     592753.5405     5420975.863
     592754.7815    5420975.7694     592755.2421    5420975.7254
     592758.2646    5420975.5052     592772.2769    5420974.4498
     592807.9881    5420971.7801     592809.8398    5420971.6345
     592812.8423    5420971.4141     592834.6414    5420969.7812
     592922.0496    5420923.5869     592967.1283    5420899.7529
      592985.806    5420889.8898     592992.7134    5420886.2312
     592993.5893    5420885.7728     593054.4258    5420853.6171
     593215.7868     5420692.619     593228.2796    5420680.1448
     593234.1458    5420674.3026     593251.6742    5420656.8053
     593300.4695     5420608.123593328.5783616975420580.42338077

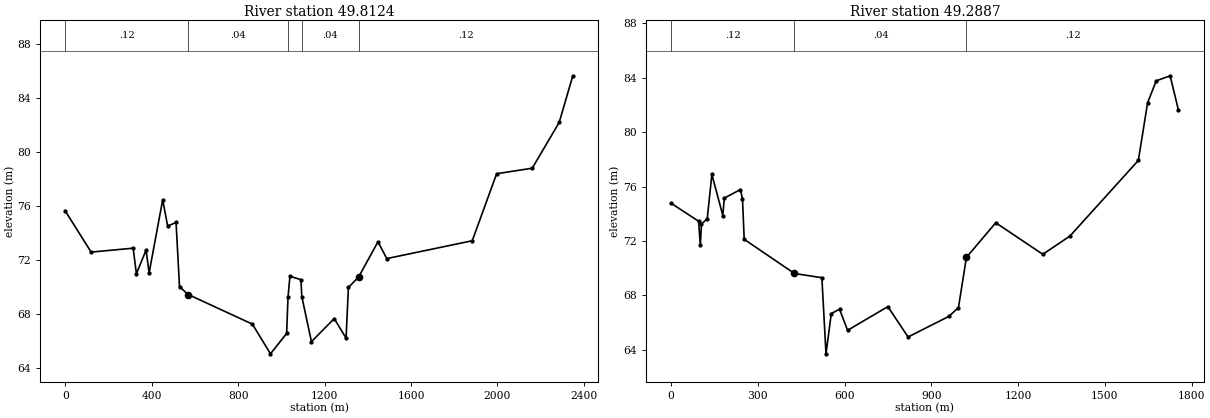
Type RM Length L Ch R = 1 ,49.8124 ,803.52,523.74,378.79
BEGIN DESCRIPTION:
R02A (SEM 2019)
END DESCRIPTION:
XS GIS Cut Line= 4
592295.5420035985422017.53628309592416.5131035985421462.56678309
592540.6005035985420663.98338309592643.2720035995419696.13978309
#Sta/Elev= 30
       0   75.59  118.79   72.57  313.45   72.86  328.42   70.97  373.34   72.72
  387.32   71.03  450.21   76.44  473.17   74.49   512.1   74.77  528.07   70.01
  568.53   69.43  865.61   67.24  949.41   65.04 1024.24   66.55 1030.53   69.23
 1039.52   70.78 1090.46   70.53 1094.46   69.28  1139.1   65.94 1244.66   67.65
 1299.48    66.2 1310.23   69.95 1357.62   70.73  1447.1   73.33 1488.07   72.09
 1883.77   73.41 1996.69   78.37 2161.56   78.78 2286.47   82.17 2349.43   85.62
#Mann= 5 ,-1 , 0
       0     .12       0  568.53     .04       0 1030.53     .12       0
 1094.46     .04       0 1357.62     .12       0
Bank Sta=568.53,1357.62
XS Rating Curve= 0 ,0
Exp/Cntr=0.3,0.1

Type RM Length L Ch R = 1 ,49.2887 ,782.52,939.38,745.21
BEGIN DESCRIPTION:
Camp Island - R02A (SEM 2019)
END DESCRIPTION:
XS GIS Cut Line= 4
592978.1684035985421615.36878309593198.8770035985421269.38198309
592870.4438035985420655.51768309592904.3578035985420008.33668309
#Sta/Elev= 30
       0   74.77   94.86   73.45  100.85   71.71  104.84   73.24  124.81   73.64
  140.79   76.89  178.73   73.87  183.73   75.15  239.64   75.78  246.63   75.11
  252.62   72.12  426.39   69.61  521.26    69.3 535.519  63.705  553.78  66.665
 582.291  66.985 610.158  65.435 749.501  67.175 819.419  64.945 961.121  66.465
  993.69   67.11 1021.16   70.79 1122.57   73.34 1285.33   71.02 1379.19   72.36
 1615.84   77.92  1647.8   82.16 1677.75   83.77 1725.68   84.14 1754.64    81.6
#Mann= 3 , 0 , 0
       0     .12       0  426.39     .04       0 1021.16     .12       0
Bank Sta=426.39,1021.16
XS Rating Curve= 0 ,0
Exp/Cntr=0.3,0.1

River Reach=Exploits River  ,RP to CB
Reach XY= 30
593328.5783616975420580.42338077     593771.6442    5420128.9175
     593902.7783     5420059.881     594021.5076    5420044.5053
      594148.221    5420065.2206     594320.5165    5420160.6177
     594521.8948    5420296.6032      594775.297    5420500.9961
     594867.7145    5420555.1266      594958.337    5420583.8262
     595021.9304     5420576.204     595130.3235    5420541.6444
     595200.9614    5420481.2007     595258.9587     5420416.351
     595368.9978    5420417.7991      595484.828    5420461.6589
     595564.5394    5420515.6122     595660.6287    5420612.1266
     595910.7423    5420905.3672      596040.209    5421038.2871
     596364.6602    5421311.3488       596513.46    5421423.3657
     596719.2446    5421546.7115     596903.2042    5421559.7117
     596990.1651    5421546.0378     597169.0854    5421459.5021
      597233.264    5421407.4423     597308.4932    5421319.5417
     597369.1672    5421212.4015597386.2387024965421161.31664681

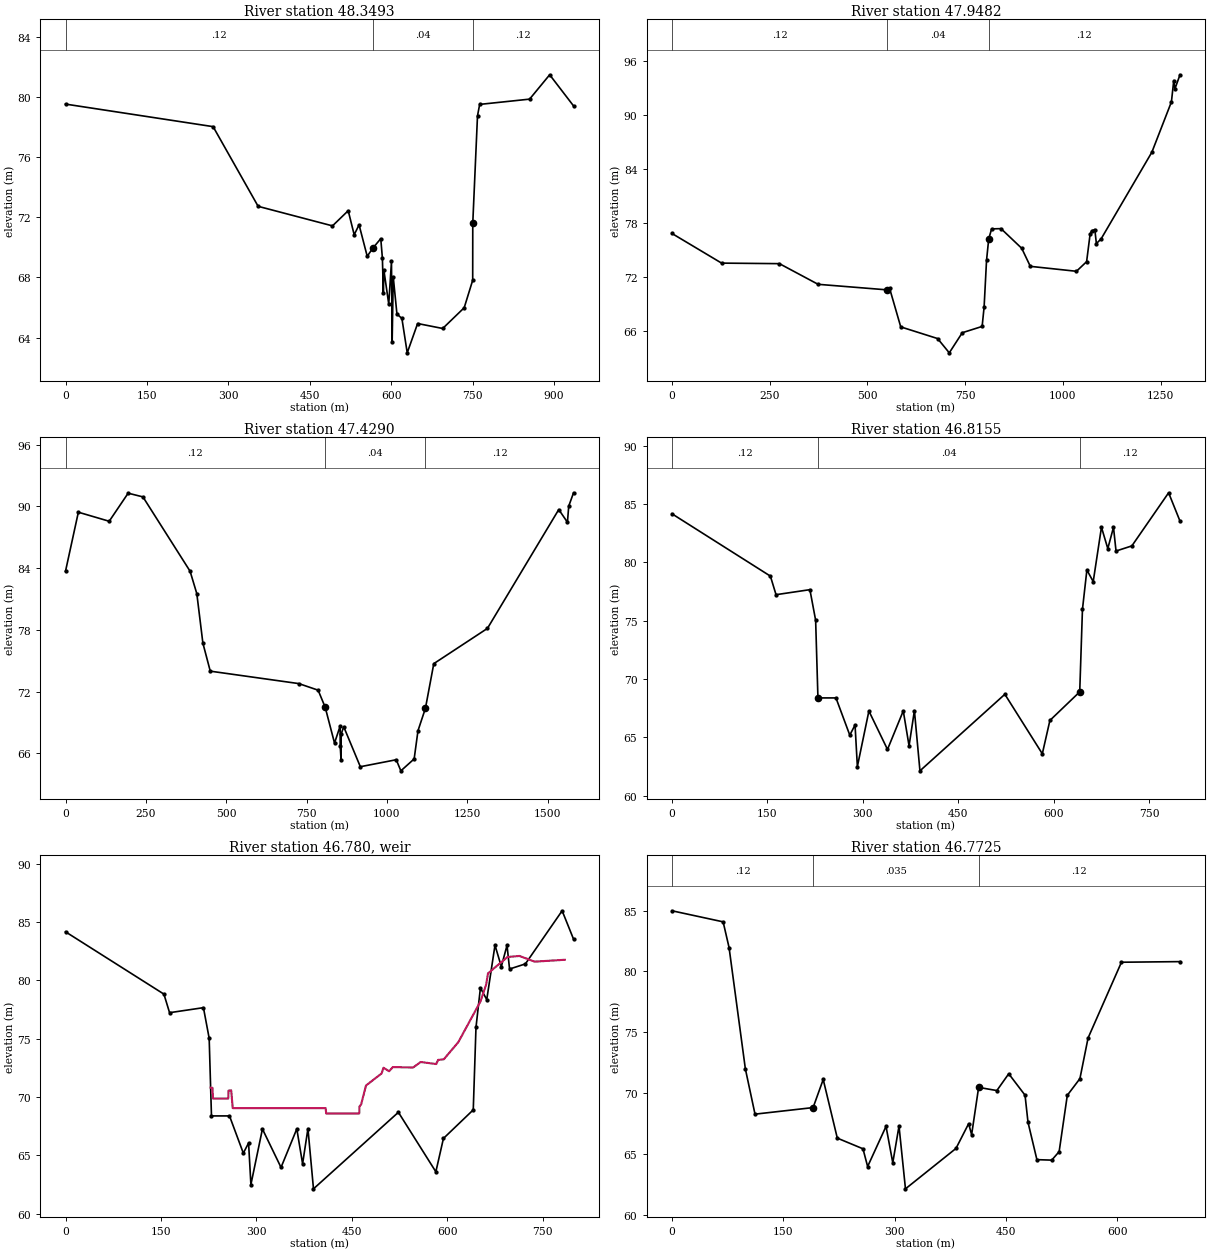
Type RM Length L Ch R = 1 ,48.3493 ,323.78,401.12,495.42
BEGIN DESCRIPTION:
Grand Falls Golf Club - R03 (RIS 2013)
END DESCRIPTION:
XS GIS Cut Line= 4
594097.2124035985420723.51688309593722.7239035985420282.07668309
593591.9733035985420171.52808309593462.8692035985420037.68388309
#Sta/Elev= 30
       0   79.53  271.95   78.03  354.93   72.73  491.91   71.43   520.9   72.44
   531.9   70.84   540.9    71.5  555.89   69.41  566.73   69.97  580.88   70.58
  583.87   69.29  585.64  66.995  586.71  68.465  595.59  66.225   600.6  69.065
  601.87  63.705  603.84  68.045  610.67  65.565  619.81  65.275  629.63  62.985
  648.77  64.935     695  64.605   734.6  65.985  750.26  67.815  750.39    71.6
  759.11   78.75  763.11   79.51  855.09   79.86  892.09   81.48  936.08   79.41
#Mann= 3 , 0 , 0
       0     .12       0  566.73     .04       0  750.39     .12       0
Bank Sta=566.73,750.39
XS Rating Curve= 0 ,0
Exp/Cntr=0.3,0.1

Type RM Length L Ch R = 1 ,47.9482 ,466.43,519.18,595.07
BEGIN DESCRIPTION:
DS of Rushy Pond Brook - R04 (RIS 2013)
END DESCRIPTION:
XS GIS Cut Line= 4
594169.7219035985420692.43048309594013.3890035985420154.02098309
593979.8898035995419678.27508309594038.2769035995419422.95438309
#Sta/Elev= 30
       0   76.81  126.92   73.51  274.83   73.45  373.77   71.15   550.7   70.53
  556.65    70.7  585.14   66.41  679.43   65.11   709.3   63.52  742.57   65.76
  793.33   66.46  798.37   68.61  804.61   73.82  810.16    76.2  817.61   77.32
   841.6   77.35   894.6   75.16  916.59   73.15 1034.57    72.6 1060.56   73.67
 1069.56   76.75 1073.56    77.1 1081.56   77.25 1085.56   75.69 1097.55    76.2
  1227.5   85.86 1277.49   91.46 1283.48   93.84 1286.48   92.92 1299.48   94.48
#Mann= 3 , 0 , 0
       0     .12       0   550.7     .04       0  810.16     .12       0
Bank Sta=550.7,810.16
XS Rating Curve= 0 ,0
Exp/Cntr=0.3,0.1

Type RM Length L Ch R = 1 ,47.4290 ,648.13,613.51,432.68
BEGIN DESCRIPTION:
R04A (SEM 2019)
END DESCRIPTION:
XS GIS Cut Line= 4
  594429.2282036 5421129.4479831  594228.1445036 5420880.7390831
  594282.1953036 5420653.8590831  594720.9810036 5419724.6056831
#Sta/Elev= 30
       0    83.7   39.98   89.44  135.93   88.56   194.9   91.29  240.87   90.93
  387.61    83.7  408.54   81.52  427.47    76.7   450.4   73.98     726   72.77
  785.98   72.13  807.97   70.47  837.01  66.985  854.51  68.645  854.67  66.695
  857.35  65.365  857.78  67.875  865.58  68.575  917.32  64.685 1029.05  65.365
 1043.41  64.285 1084.79  65.445 1096.67  68.185 1119.86   70.37 1145.85   74.71
 1312.79   78.14 1534.71    89.7  1561.7   88.46  1565.7   90.03  1580.7   91.33
#Mann= 3 , 0 , 0
       0     .12       0  807.97     .04       0 1119.86     .12       0
Bank Sta=807.97,1119.86
XS Rating Curve= 0 ,0
Exp/Cntr=0.3,0.1

Type RM Length L Ch R = 1 ,46.8155 ,102.81,43,165.09
BEGIN DESCRIPTION:
R05 (RIS 2013)
END DESCRIPTION:
XS GIS Cut Line= 6
  595151.1957036 5420826.9782831  594966.0689036 5420742.0971831
  594997.5544036 5420671.7178831  594967.9210036 5420499.2091831
  594876.3750036 5420390.4651831  594835.6290036 5420202.8752831
#Sta/Elev= 30
       0   84.15  154.61   78.81  163.48   77.22  216.69   77.65  225.69   75.03
  229.31  68.377 257.622  68.377 279.346  65.187 287.609  66.059 291.251  62.497
 309.362  67.255 338.582  63.963 363.374  67.265 372.458  64.273 380.855  67.291
 389.559   62.13 522.952  68.688 581.808  63.592 593.717  66.448 640.569  68.896
  644.85   75.96  651.82   79.34  661.77   78.34  674.71      83  684.66   81.17
  693.62   82.99   697.6   80.96  722.48    81.4   780.2   85.95  798.12   83.52
#Mann= 3 , 0 , 0
       0     .12       0  229.31     .04       0 640.569     .12       0
Bank Sta=229.31,640.569
XS Rating Curve= 0 ,0
Exp/Cntr=0.3,0.1

Type RM Length L Ch R = 5 ,46.780  ,,,
Node Photo=.\Photos\Goodyears Dam.JPG
BEGIN DESCRIPTION:
Goodyear's Dam
END DESCRIPTION:
Node Name=GY Dam
IW Pilot Flow=0
#Inline Weir SE= 30
     228  70.795 230.859  70.789 231.631  69.864 255.648  69.864 256.089  70.546
 260.282  70.569 262.695  69.044 408.695  69.044 409.516  68.584 461.516  68.584
 461.616  69.165 464.473  69.371  472.09  70.985 496.617  72.013 499.562  72.503
 508.395  72.205 514.284   72.56 546.061  72.523 557.865  72.995 582.374   72.82
 585.356  73.173 594.301  73.227  617.13    74.7 651.793  78.175 660.725  79.607
 663.703  80.588 694.376  81.992 713.165   82.08 736.899  81.592 784.313  81.752
IW Dist,WD,Coef,Skew,MaxSub,Min_El,Is_Ogee,SpillHt,DesHd
16,3.65,2.5,0,0.98,, 0 ,,,3,3,
Inline Weir Flap Gates= 0
IW Outlet Rating Curve= 0 ,False,,

Type RM Length L Ch R = 1 ,46.7725 ,238.71,238.6,356.06
BEGIN DESCRIPTION:
DS of Goodyear's Dam
END DESCRIPTION:
XS GIS Cut Line= 4
  595176.4633036 5420836.8297831  595037.1861036 5420663.0153831
  594997.4579036 5420440.5965831  594891.0985036 5420230.1995831
#Sta/Elev= 30
       0   84.99   68.92   84.08   76.91   81.97   98.88   71.99  111.87   68.27
  190.12   68.81  203.75   71.12  222.73    66.3 257.326  65.422 263.582  63.963
 288.374  67.265 297.458  64.273 305.855  67.291 314.559   62.13 382.608  65.452
  399.68   67.49  403.68   66.58  413.12   70.47  437.67   70.21  453.67   71.59
  475.64   69.83  479.64    67.6  491.63   64.53   511.6   64.49  521.59   65.19
  532.58   69.82  549.57   71.19  560.55   74.53  605.51   80.76  684.42   80.81
#Mann= 3 , 0 , 0
       0     .12       0  190.12    .035       0  413.12     .12       0
Bank Sta=190.12,413.12
XS Rating Curve= 0 ,0
Exp/Cntr=0.3,0.1

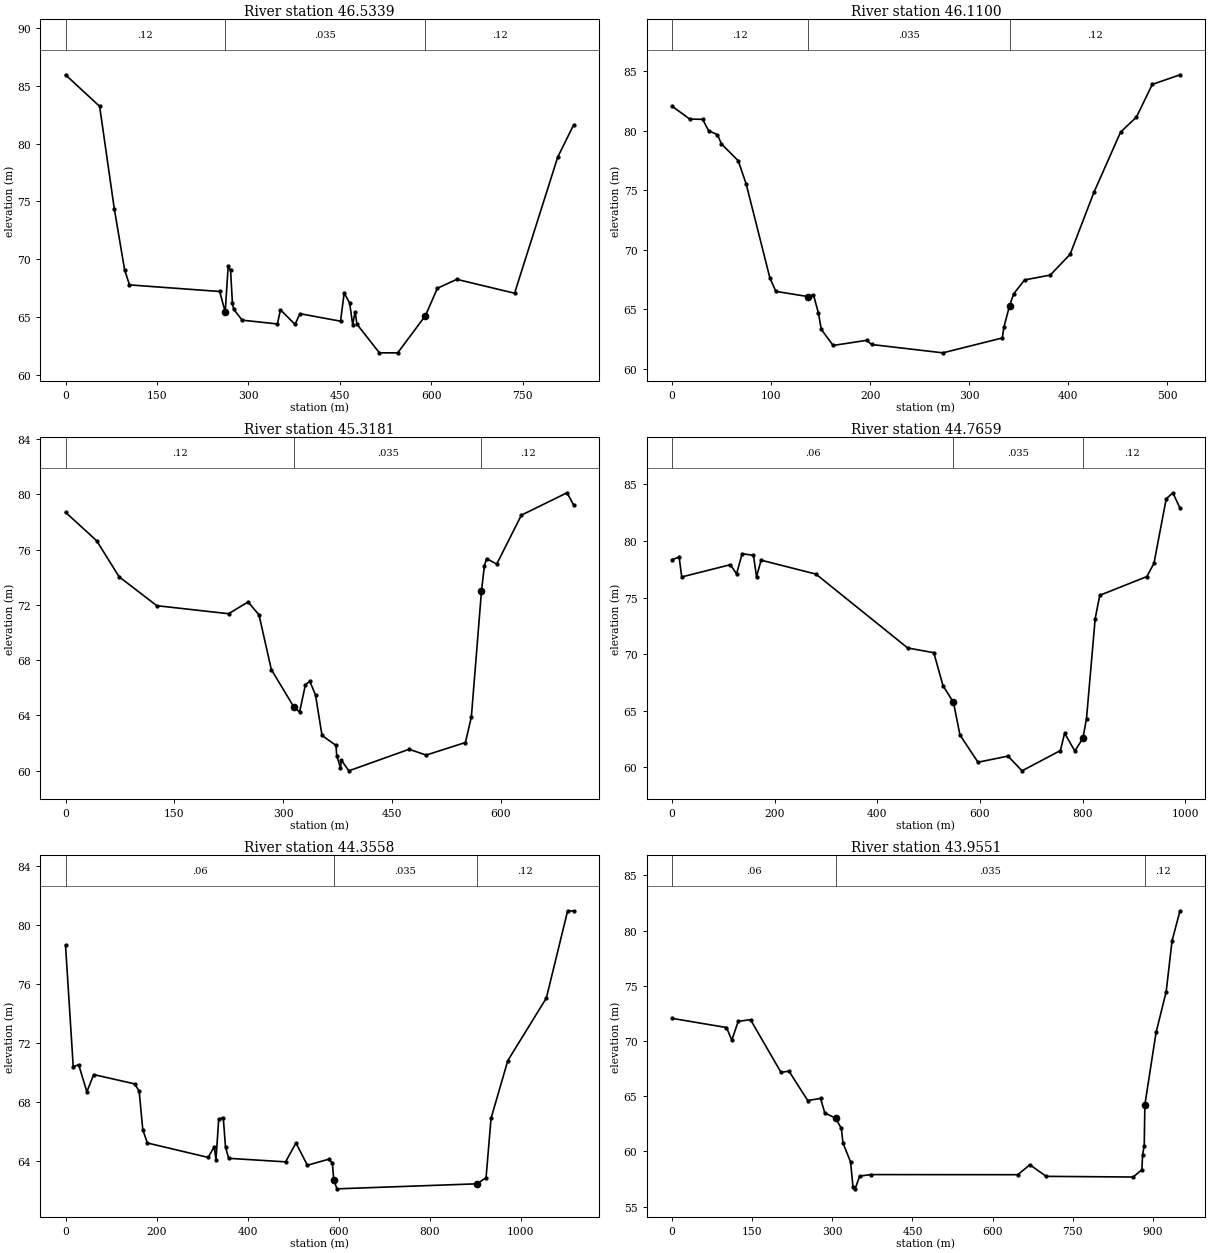
Type RM Length L Ch R = 1 ,46.5339 ,317.86,423.87,565.51
XS GIS Cut Line= 6
  595274.0180036 5420823.7344831  595239.7875036 5420555.3472831
  595238.4646036 5420486.5554831  595212.3369036 5420440.5839831
  595201.4228036 5420411.8104831  595203.4965036 5420001.7937831
#Sta/Elev= 30
       0   85.96   55.98   83.23   79.97   74.39   96.97   69.08  104.97   67.78
  252.92   67.21  262.03   65.43  266.87    69.4  270.84   69.03  273.83   66.19
  275.83   65.68  289.79   64.73  347.63    64.4  352.62   65.63  376.56   64.36
  384.54   65.29  451.21   64.64  457.19   67.08  466.16   66.21  471.14   64.34
  475.13   65.46  478.12   64.38     515  61.902     545  61.902  590.49   65.12
  610.08   67.49     642   68.26  736.74   67.06  807.55   78.84  833.48   81.61
#Mann= 3 , 0 , 0
       0     .12       0  262.03    .035       0  590.49     .12       0
Bank Sta=262.03,590.49
XS Rating Curve= 0 ,0
Exp/Cntr=0.3,0.1

Type RM Length L Ch R = 1 ,46.1100 ,800.96,791.92,793.35
BEGIN DESCRIPTION:
R07 (RIS 2013)
END DESCRIPTION:
XS GIS Cut Line= 4
595453.4822035985420727.51768309595538.1372035985420606.40498309
595665.5410035985420454.63808309595776.1744035995420329.63758309
#Sta/Elev= 30
       0   82.07   17.97   80.98   30.95   80.96   36.94   80.01   45.93   79.67
   49.92    78.9   66.89   77.48   74.88   75.54   98.84   67.65  104.83   66.52
  137.67   66.08  142.77   66.24  147.77   64.73  150.75   63.33  162.68  61.982
  196.65  62.412  201.42  62.062  273.43  61.362  333.52  62.612  334.97   63.49
  340.75    65.3  344.92   66.31  355.92   67.48   381.9   67.89   401.9   69.63
  425.88   74.82  452.87   79.89  468.87   81.15  484.86   83.89  512.85    84.7
#Mann= 3 , 0 , 0
       0     .12       0  137.67    .035       0  340.75     .12       0
Bank Sta=137.67,340.75
XS Rating Curve= 0 ,0
Exp/Cntr=0.3,0.1

Type RM Length L Ch R = 1 ,45.3181 ,604.09,552.23,528.89
BEGIN DESCRIPTION:
R08 (RIS 2013)
END DESCRIPTION:
XS GIS Cut Line= 2
595842.4030035995421461.21828309596295.4702035985420927.48878309
#Sta/Elev= 30
       0    78.7   42.94   76.64    73.9   74.03  125.84   71.94  224.71   71.36
  251.68   72.21  266.66   71.27  283.63   67.32  314.91   64.59  322.58   64.25
  330.57   66.21  336.57   66.48  344.56   65.47  353.48  62.551  372.73  61.831
  373.75  61.081  378.92  60.211  380.22  60.761  390.49  59.991  473.45  61.551
     497  61.131   551.1  62.041  559.28   63.89   573.2   72.98  577.26   74.83
  580.25   75.35  594.23   74.95  628.19   78.49  691.11   80.11   700.1   79.24
#Mann= 3 , 0 , 0
       0     .12       0  314.91    .035       0   573.2     .12       0
Bank Sta=314.91,573.2
XS Rating Curve= 0 ,0
Exp/Cntr=0.3,0.1

Type RM Length L Ch R = 1 ,44.7659 ,541.81,410.11,274.04
BEGIN DESCRIPTION:
R09 (RIS 2013)
END DESCRIPTION:
XS GIS Cut Line= 4
596246.1248035985422054.90958309596516.1615035985421558.45688309
596622.0283035985421353.49208309596761.9062035985421218.82748309
#Sta/Elev= 30
       0   78.34   13.98   78.58   18.97   76.82  113.83    77.9  125.81   77.09
  136.79   78.87  158.76   78.73  164.75   76.84  173.74    78.3  280.57   77.07
   459.3   70.55  510.23   70.13   528.2   67.21  548.52   65.75  561.15   62.87
  596.29  60.462  654.83  61.002  682.13  59.702  756.92  61.492  765.13  63.022
  785.05  61.452  800.87   62.59  807.78   64.32  824.71   73.15  833.67    75.2
  925.28   76.85  939.22   78.02  963.12   83.72  976.06   84.25     990   82.89
#Mann= 3 , 0 , 0
       0     .06       0  548.52    .035       0  800.87     .12       0
Bank Sta=548.52,800.87
XS Rating Curve= 0 ,0
Exp/Cntr=0.3,0.1

Type RM Length L Ch R = 1 ,44.3558 ,524.36,400.64,344.37
BEGIN DESCRIPTION:
First Falls
END DESCRIPTION:
XS GIS Cut Line= 4
     597278.6605     5422194.348      597007.465     5421671.309
     596869.2199     5421371.006     596764.6875     5421205.026
#Sta/Elev= 30
       0   78.62   16.98   70.37   28.96   70.51   46.93   68.67   61.91   69.84
  151.79   69.21  161.77   68.72  169.76    66.1  179.75    65.2  313.56   64.22
  326.54   64.95  330.53   64.06  336.52   66.82  346.51   66.92   351.5    64.9
  358.49   64.16  483.32   63.92  506.28    65.2  531.25   63.69  578.18    64.1
  586.17   63.85  589.17   62.71  596.16   62.09  903.41   62.43  923.75   62.84
   934.7   66.87  971.54   70.79 1056.18   75.03 1102.97   80.95 1115.92   80.93
#Mann= 3 , 0 , 0
       0     .06       0  589.17    .035       0  903.41     .12       0
Bank Sta=589.17,903.41
XS Rating Curve= 0 ,0
Exp/Cntr=0.3,0.1

Type RM Length L Ch R = 1 ,43.9551 ,107.68,95.97,20.95
BEGIN DESCRIPTION:
R11 (RIS 2013)
END DESCRIPTION:
XS GIS Cut Line= 3
597687.3123035985421827.51058309597121.5261035985421148.34858309
597054.8230035985421150.64028309
#Sta/Elev= 30
       0   72.05  101.99   71.22  111.99   70.08  123.99   71.78  146.99   71.93
  203.99   67.16  218.99   67.27  253.99   64.61  277.98    64.8  285.98   63.48
  306.01   63.02  316.98   62.09  319.98   60.77  334.15  59.054  338.84  56.754
  342.79  56.614  351.16  57.764  371.89  57.904  647.13  57.894  669.64  58.794
  700.34  57.744  863.07  57.684  879.31  58.344  880.69  59.714  883.73  60.514
  884.95   64.23  905.87   70.77   924.8   74.46  935.75   79.06   950.7   81.79
#Mann= 3 , 0 , 0
       0     .06       0  306.01    .035       0  884.95     .12       0
Bank Sta=306.01,884.95
XS Rating Curve= 0 ,0
Exp/Cntr=0.3,0.1

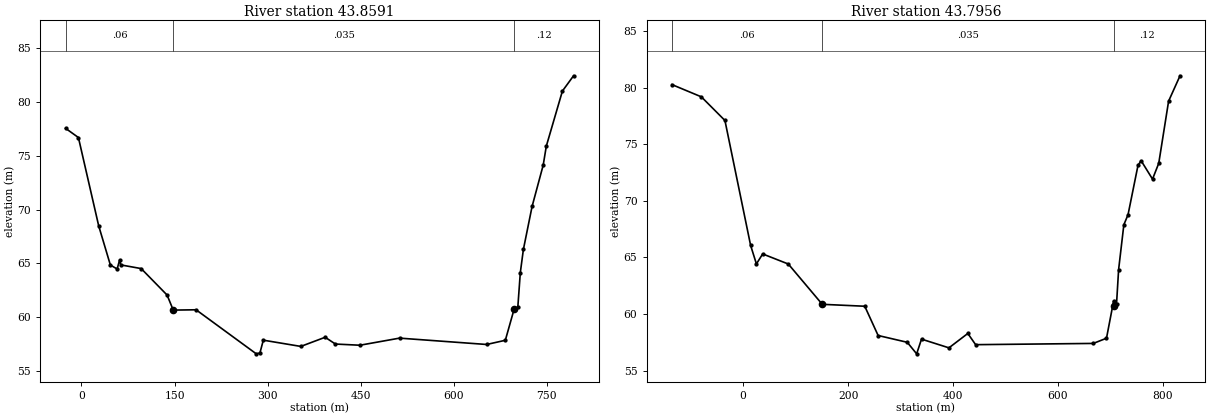
Type RM Length L Ch R = 1 ,43.8591 ,10.55,63.54,29.49
BEGIN DESCRIPTION:
Grand Falls Headpond
END DESCRIPTION:
XS GIS Cut Line= 5
  597643.7841036 5421540.2596831  597552.7011036 5421537.6815831
  597565.6518036 5421412.1162831  597114.0350036 5421122.2995831
  597052.4352036 5421142.5266831
#Sta/Elev= 30
   -25.7   77.55    -4.9   76.69   27.78   68.48    46.6   64.84    57.5   64.47
   61.46    65.3   63.44   64.85   96.23   64.51  137.98   62.05  147.92   60.65
  184.69   60.68  281.73  56.585   287.6  56.665  293.06  57.855  353.48  57.275
  392.73  58.125  409.26  57.495  448.75  57.385  512.54  58.045  652.95  57.455
  683.07  57.845  697.08   60.71  703.18   60.91  707.18   64.12  712.17   66.29
  726.16   70.28  744.11   74.13   749.1   75.89  775.04   81.01  792.99   82.43
#Mann= 3 , 0 , 0
   -25.7     .06       0  147.92    .035       0  697.08     .12       0
Bank Sta=147.92,697.08
XS Rating Curve= 0 ,0
Exp/Cntr=0.3,0.1

Type RM Length L Ch R = 1 ,43.7956 ,316.97,138.53,124.09
BEGIN DESCRIPTION:
Grand Falls Headpond
END DESCRIPTION:
XS GIS Cut Line= 6
  597730.0174036 5421503.0686831  597556.6698036 5421532.5221831
  597580.1693036 5421382.0480831  597466.4252036 5421254.2706831
  597113.7601036 5421095.2694831  597047.5184036 5421134.6734831
#Sta/Elev= 30
  -135.5   80.27  -79.55   79.19   -34.6    77.1   14.36   66.0625.35001   64.43
   37.33   65.31   86.12   64.42  150.82   60.86  231.79   60.69  257.24  58.105
  312.72  57.505  330.66  56.485  339.89  57.785  392.14  57.015  428.12  58.285
  442.99  57.295  667.17  57.405  692.32  57.865  705.95  61.165  706.87   60.71
  711.42   60.87  715.41   63.93  725.39   67.89  733.37   68.78  752.31   73.13
  758.27   73.55  780.01   71.92  791.87   73.32  810.64   78.81  832.38   81.05
#Mann= 3 , 0 , 0
  -135.5     .06       0  150.82    .035       0  706.87     .12       0
Bank Sta=150.82,706.87
XS Rating Curve= 0 ,0
Exp/Cntr=0.3,0.1

River Reach=Exploits River  ,CB to BF4
Reach XY= 30
597386.2387024965421161.31664681     597465.9448     5420773.451
     597441.9324    5420403.8134     597377.4104    5420331.5317
     597393.1335    5420131.3395     597574.4756    5419951.1848
     597854.7517    5419912.8074     598081.7714    5419759.8408
     598427.0818    5419906.0503     598693.5912    5419797.6487
     598706.3272    5419673.9989     598805.7913    5419654.6798
     598981.5729    5419746.6738     599326.3572    5419741.4218
     599897.9826    5419888.6298     600287.8965     5420012.289
     600603.2217    5420175.1729     601691.3917    5421438.2026
     601948.5621    5421678.6347     602709.6031    5422228.3508
     602997.5023    5422545.3811     604028.7933    5423466.9234
     604251.6472    5423740.7625     604777.6142    5424141.3618
     605280.2617      5424704.61     605694.7374    5425052.9373
     605890.3127    5425470.3459     606173.3597    5425833.8717
     606824.0366    5426407.5418607343.2426745345426949.64970111

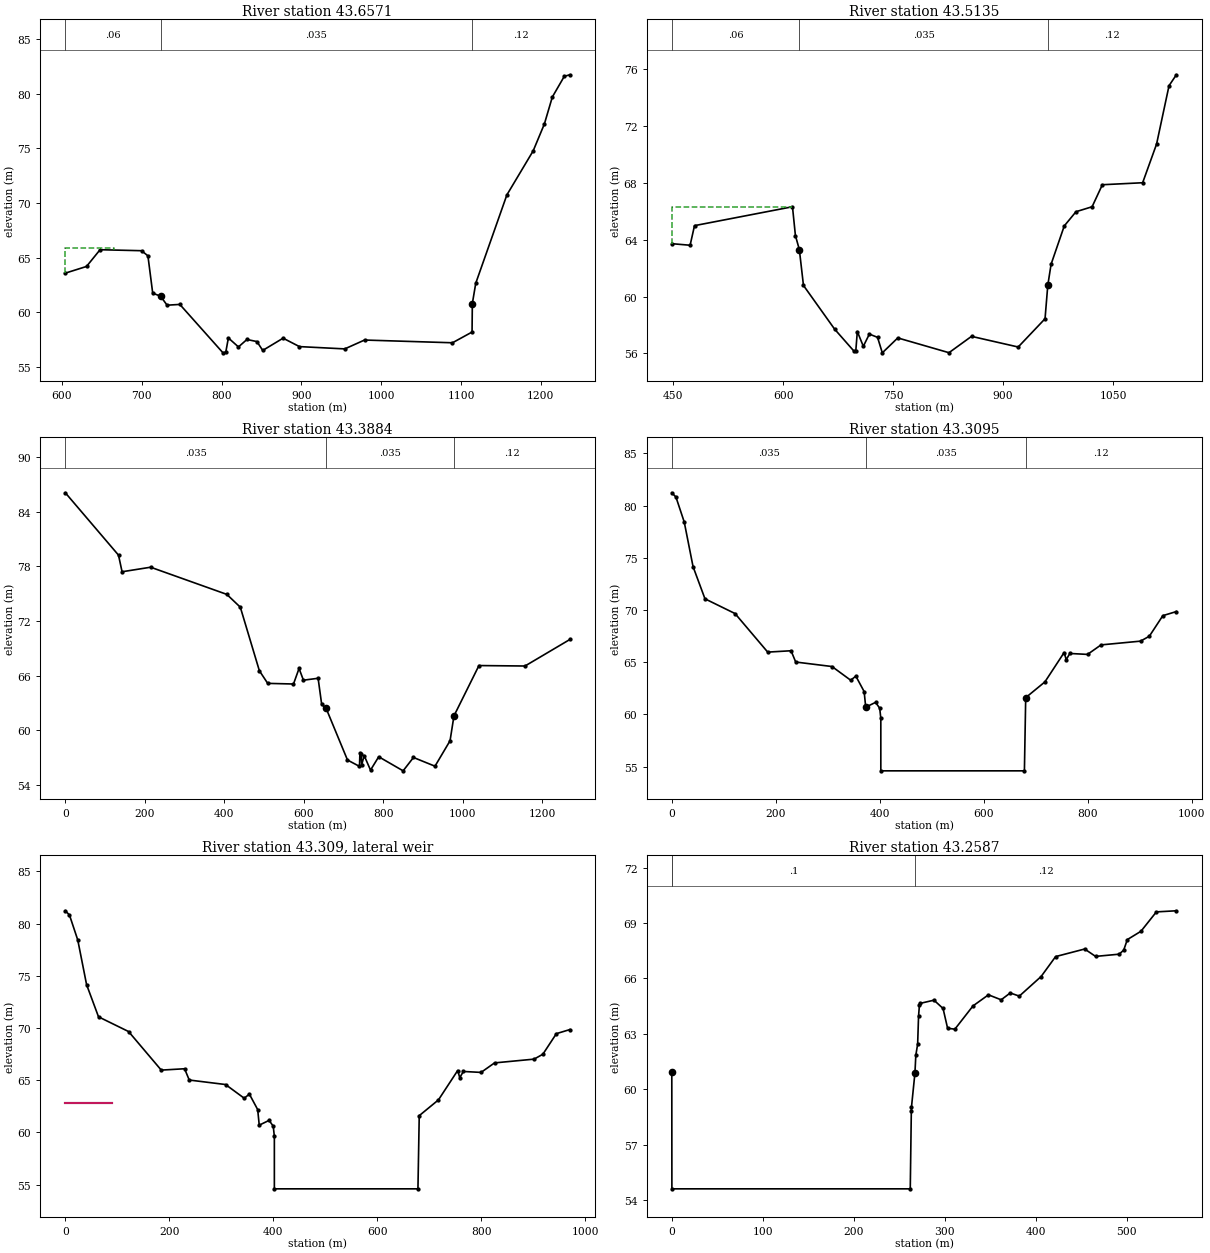
Type RM Length L Ch R = 1 ,43.6571 ,165.58,143.54,122.91
BEGIN DESCRIPTION:
Grand Falls Headpond
END DESCRIPTION:
XS GIS Cut Line= 2
  597695.1645036 5421183.9668831  597102.5594036 5420963.6381831
#Sta/Elev= 30
   604.2   63.59  630.73    64.2  647.73   65.73  699.71   65.64   707.7   65.17
   713.7   61.76  723.59   61.48  731.69   60.66  747.69   60.73  801.78  56.305
  805.27  56.365  808.51  57.665  821.15  56.845  831.76  57.525  844.29  57.335
  851.57  56.525  877.09  57.645  897.57  56.875  954.36  56.665  979.15  57.475
 1089.35  57.225 1113.88  58.205 1114.24   60.81 1118.53   62.67 1157.52   70.74
  1190.5   74.77  1204.5   77.22 1214.49   79.69 1229.49   81.58 1236.48   81.72
#Mann= 3 , 0 , 0
   604.2     .06       0  723.59    .035       0 1114.24     .12       0
#XS Ineff= 2 , 0
          665.19   65.92
Permanent Ineff=
       F       F
Bank Sta=723.59,1114.24
XS Rating Curve= 0 ,0
Exp/Cntr=0.3,0.1

Type RM Length L Ch R = 1 ,43.5135 ,151.21,125.11,95.9
BEGIN DESCRIPTION:
Grand Falls Headpond
END DESCRIPTION:
XS GIS Cut Line= 2
  597763.9970036 5421020.9887831  597096.9170036 5420850.6657831
#Sta/Elev= 30
     448   63.72  472.98   63.61  478.98   64.99  612.65   66.32  616.65   64.29
  621.99   63.31  627.64   60.78   670.1  57.706  696.87  56.136  699.04  56.176
   701.1  57.536  709.31  56.496  717.54  57.356  728.71  57.126   735.2  56.036
   756.3  57.086  826.14  56.046  856.92  57.196  920.59  56.446  957.21  58.436
  960.94   60.78  965.45   62.27  983.44   64.97  999.43   65.97 1021.42   66.32
 1035.41   67.87 1090.38   68.01 1109.37   70.73 1126.36   74.84 1136.36   75.61
#Mann= 3 , 0 , 0
     448     .06       0  621.99    .035       0  960.94     .12       0
#XS Ineff= 2 , 0
          612.66   66.32
Permanent Ineff=
       F       F
Bank Sta=621.99,960.94
XS Rating Curve= 0 ,0
Exp/Cntr=0.3,0.1

Type RM Length L Ch R = 1 ,43.3884 ,117.19,78.92,45.96
BEGIN DESCRIPTION:
Grand Falls Headpond
END DESCRIPTION:
XS GIS Cut Line= 3
598196.6806035985421119.79348309597703.5067035985420835.25138309
597004.9433035985420779.50268309
#Sta/Elev= 30
       0   86.11  133.85   79.25  142.84   77.42  214.76   77.92  406.55   74.93
  440.51   73.52  488.46   66.53  509.44   65.14  574.37   65.07  588.36   66.78
  599.36   65.49  636.35    65.7  645.35   62.82  656.23   62.42  710.29  56.706
   740.5  56.006  741.57  57.436  744.31  57.396  746.04  56.186  752.28  57.196
  768.28  55.596  788.91  57.066  850.34  55.516  876.36  56.986  930.56  56.026
  968.48  58.826  978.31   61.56 1041.23    67.1 1157.19   67.05 1270.15   69.97
#Mann= 3 , 0 , 0
       0    .035       0  656.23    .035       0  978.31     .12       0
Bank Sta=656.23,978.31
XS Rating Curve= 0 ,0
Exp/Cntr=0.3,0.1

Type RM Length L Ch R = 1 ,43.3095 ,77.56,50.84,23.88
BEGIN DESCRIPTION:
Grand Falls Headpond
END DESCRIPTION:
XS GIS Cut Line= 4
  597978.1346036 5420818.1539831  597617.2500036 5420716.1466831
  597306.4205036 5420759.0828831  597025.8009036 5420733.1719831
#Sta/Elev= 30
       0   81.22    7.98   80.81   23.94   78.42   40.89   74.15   63.83   71.07
  121.68   69.66  184.52   65.97   229.4    66.1  238.38   65.02   308.2   64.59
   344.1   63.28  354.08   63.67  370.04   62.19  373.03    60.7  392.01   61.16
  399.95    60.6   402.1  59.636  402.11  54.606  678.33  54.606  680.81   61.61
  717.78   63.12  754.76   65.93  758.76   65.25  765.75   65.84  799.73   65.75
  825.71   66.66  901.66   67.02  918.65   67.49  944.63   69.46  970.62   69.85
#Mann= 3 , 0 , 0
       0    .035       0  373.03    .035       0  680.81     .12       0
Bank Sta=373.03,680.81
XS Rating Curve= 0 ,0
Exp/Cntr=0.3,0.1

Type RM Length L Ch R = 6 ,43.309  ,,,
BEGIN DESCRIPTION:
Forebay Gate Structure
END DESCRIPTION:
Lateral Weir Pos= 1
Lateral Weir End=                ,                ,        ,Power Canal
Lateral Weir Distance=0
Lateral Weir TW Multiple XS=0
Lateral Weir WD=4
Lateral Weir Coef=1.45
LW OverFlow Method 2D=0
LW OverFlow Use Velocity Into 2D=0
Lateral Weir WSCriteria=-1
Lateral Weir Flap Gates= 0
Lateral Weir Hagers EQN= 0 ,,,,,
Lateral Weir SS=0.05,0.05,
Lateral Weir Type= 0
Lateral Weir Connection Pos and Dist= 3 ,
Lateral Weir SE= 2
       0  62.826      90  62.826
Lateral Weir Centerline= 0
Lateral Weir HW RS User Defined=-1
Lateral Weir HW RS Station=43.3095,0
Lateral Weir HW RS Station=43.2587,90.01
LW Gate Name Wd,H,Inv,GCoef,Exp_T,Exp_O,Exp_H,Type,WCoef,Is_Ogee,SpillHt,DesHd,#Openings
Gate #1     ,2.44,3.66,54.606,0.6,0,1,0.5, 0 ,1.67, 0 ,,, 17 ,0,0.8, 0 ,0.6,,0,0,0, 0
   16.22   19.88   23.53   27.19   30.85   34.51   38.16   41.82   45.48   50.66
   54.32   57.97   61.63   65.29   68.95    72.6   76.26
LW Gate Opening=1,Opening #1,0
LW Gate Opening=2,Opening #2,0
LW Gate Opening=3,Opening #3,0
LW Gate Opening=4,Opening #4,0
LW Gate Opening=5,Opening #5,0
LW Gate Opening=6,Opening #6,0
LW Gate Opening=7,Opening #7,0
LW Gate Opening=8,Opening #8,0
LW Gate Opening=9,Opening #9,0
LW Gate Opening=10,Opening #10,0
LW Gate Opening=11,Opening #11,0
LW Gate Opening=12,Opening #12,0
LW Gate Opening=13,Opening #13,0
LW Gate Opening=14,Opening #14,0
LW Gate Opening=15,Opening #15,0
LW Gate Opening=16,Opening #16,0
LW Gate Opening=17,Opening #17,0
LW Div RC= 0 ,False,,

Type RM Length L Ch R = 1 ,43.2587 ,255.78,14.78,12.14
BEGIN DESCRIPTION:
US of Grand Falls Main Dam
END DESCRIPTION:
XS GIS Cut Line= 3
597569.7686035985420650.02038309597308.0210035985420738.51608309
597030.5393035985420715.01628309
#Sta/Elev= 30
       0  60.906      .1  54.606   262.2  54.606  263.37  58.806  263.55  59.036
  267.33   60.87  268.32   61.84  270.32   62.44  271.32   63.96  272.31   64.57
  273.31   64.65  288.28   64.82  298.26   64.37  303.25    63.3  311.24   63.25
   331.2   64.51  348.17   65.11  362.14   64.84  372.12   65.21   382.1   65.04
  406.06    66.1  422.03   67.18  453.97   67.59  465.95   67.19   491.9   67.31
  496.89   67.53  500.88    68.1  515.85   68.55  532.82    69.6  554.78   69.66
#Mann= 3 , 0 , 0
       0    .035       0       0      .1       0  267.33     .12       0
Bank Sta=0,267.33
XS Rating Curve= 0 ,0
Exp/Cntr=0.3,0.1

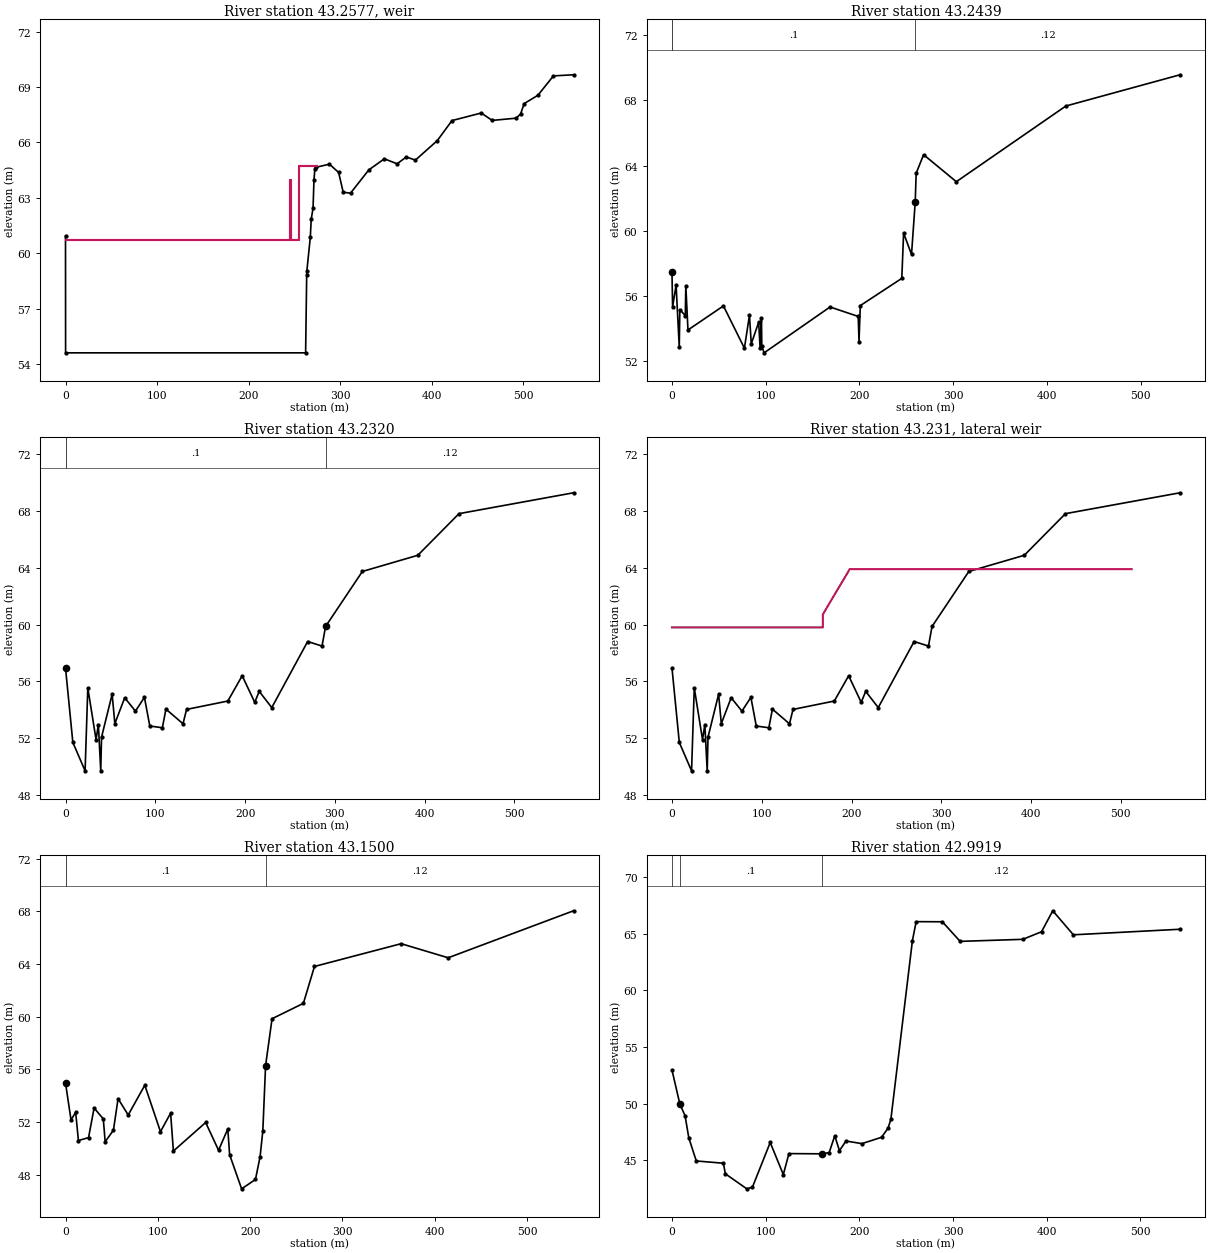
Type RM Length L Ch R = 5 ,43.2577 ,,,
Node Photo=.\Photos\Grand Falls Dam.JPG
BEGIN DESCRIPTION:
Grand Falls Main Dam
END DESCRIPTION:
Node Name=GF Dam & Spillwa
IW Pilot Flow=0
#Inline Weir SE= 8
       0  60.706   244.9  60.706   244.9  63.956  246.05  63.956  246.05  60.706
   254.9  60.706   254.9  64.706   274.9  64.706
IW Dist,WD,Coef,Skew,MaxSub,Min_El,Is_Ogee,SpillHt,DesHd
0.1,4,2.1,0,0.98,, 0 ,,,3,3,
IW Gate Name Wd,H,Inv,GCoef,Exp_T,Exp_O,Exp_H,Type,WCoef,Is_Ogee,SpillHt,DesHd,#Openings
Outside Gate,6.096,3.9624,54.602,0.59,0,1,0.5, 0 ,1.67, 0 ,,, 1 ,0,0.8, 1 ,0.59,Sluice Gate Main Dam,0,0,0, 0
      11
IW Gate Opening=1,GFOG,0
IW Gate Name Wd,H,Inv,GCoef,Exp_T,Exp_O,Exp_H,Type,WCoef,Is_Ogee,SpillHt,DesHd,#Openings
Obermeyer   ,8.85,1.5,59.206,,0,1,0.5, 3 ,2.1, 0 ,,, 1 ,0,0.8, 0 ,,,0,0,0, 0
 250.475
IW Gate Opening=1,GFOB,0
IW Gate User Curve Set=Sluice Gate Main Dam
IW Gate User Curve Set Headwater=1
 61.0208
IW Gate User Curve Set Gate Opening=13
       1       2       3       4       5       6       7       8       9      10
      11      12      13
IW Gate User Curve Set Flows
 12.431124.52239 36.3022 47.742258.8424169.5744979.9667789.9909499.64698108.9349
117.7981126.2931147.2476
Inline Weir Flap Gates= 0
IW Outlet Rating Curve= 0 ,True,0,1
IW OutletRC Name=GF Power

Type RM Length L Ch R = 1 ,43.2439 ,0,11.92,18.02
BEGIN DESCRIPTION:
DS of Grand Falls Main Dam
END DESCRIPTION:
XS GIS Cut Line= 4
597556.9618035985420638.48298309597407.3939035985420690.40898309
597298.9594035995420731.87748309597032.1585035995420711.26798309
#Sta/Elev= 30
       0   57.47    .676  55.321     4.4  56.658   7.776  52.852   8.393   55.15
  14.224  54.779  14.762  56.622   17.06  53.899  54.897  55.379  77.271  52.782
  82.671  54.803  84.604  53.052  92.507  54.376   94.01  52.812  95.487  54.619
   95.84  52.905  98.308  52.495 168.656  55.313 198.699  54.731 199.537  53.187
  200.93  55.398 245.194   57.07 247.125  59.852  255.57   58.54  259.53   61.78
  260.53   63.53  268.46   64.67  303.37   63.01   420.2   67.66  542.02   69.58
#Mann= 3 , 0 , 0
       0    .035       0       0      .1       0  259.53     .12       0
Bank Sta=0,259.53
XS Rating Curve= 0 ,0
Exp/Cntr=0.3,0.1

Type RM Length L Ch R = 1 ,43.2320 ,0,81.92,129.03
XS GIS Cut Line= 3
597576.9952035985420619.82858309597273.7651035985420724.04668309
597029.2998035985420705.11098309
#Sta/Elev= 30
       0   56.95    8.17  51.706   21.82  49.706   24.83  55.546   34.03  51.906
    36.6  52.966   39.25  49.706   40.14  52.076   51.94    55.1   54.94   53.03
   65.93   54.85   77.91   53.91    87.9   54.88   93.89   52.86  107.88   52.74
  111.87   54.05  130.85   53.02  134.85   54.03   180.8   54.62  196.78    56.4
  210.76   54.53  215.76    55.3  229.74   54.16   269.7   58.81  285.68   58.49
  289.67   59.87  330.61   63.74   392.4   64.88  438.25   67.81  565.84   69.28
#Mann= 3 , 0 , 0
       0    .035       0       0      .1       0  289.67     .12       0
Bank Sta=0,289.67
XS Rating Curve= 0 ,0
Exp/Cntr=0.3,0.1

Type RM Length L Ch R = 6 ,43.231  ,,,
BEGIN DESCRIPTION:
Power Canal RCC Dam and west embankment section
END DESCRIPTION:
Lateral Weir Pos= 0
Lateral Weir End=                ,                ,        ,Power Canal
Lateral Weir Distance=0
Lateral Weir TW Multiple XS=0
Lateral Weir WD=4
Lateral Weir Coef=1.65
LW OverFlow Method 2D=0
LW OverFlow Use Velocity Into 2D=0
Lateral Weir WSCriteria=-1
Lateral Weir Flap Gates= 0
Lateral Weir Hagers EQN= 0 ,,,,,
Lateral Weir SS=0.05,0.05,
Lateral Weir Type= 0
Lateral Weir Connection Pos and Dist= 3 ,
Lateral Weir SE= 6
       0  59.806     168  59.806     168  60.716     198  63.906  431.39  63.906
     512  63.906
Lateral Weir Centerline= 0
Lateral Weir HW RS User Defined=-1
Lateral Weir HW RS Station=43.232,0
Lateral Weir HW RS Station=43.15,56
Lateral Weir HW RS Station=43.097*,112.3188
Lateral Weir HW RS Station=43.045*,167.575
Lateral Weir HW RS Station=42.9919,224
Lateral Weir HW RS Station=42.926*,278.5
Lateral Weir HW RS Station=42.8601,333
Lateral Weir HW RS Station=42.8015,342
Lateral Weir HW RS Station=42.749*,384.554
Lateral Weir HW RS Station=42.697*,426.7026
Lateral Weir HW RS Station=42.645*,468.8513
Lateral Weir HW RS Station=42.593,511
Lateral Weir HW RS Station=42.538*,530
LW Gate Name Wd,H,Inv,GCoef,Exp_T,Exp_O,Exp_H,Type,WCoef,Is_Ogee,SpillHt,DesHd,#Openings
Inside Gate ,4.572,2.1336,54.602,0.59,0,1,0.5, 0 ,1.67, 0 ,,, 1 ,0,0.8, 1 ,0.59,,0,0,0, 0
      10
LW Gate Opening=1,GFIG,0
LW Gate Name Wd,H,Inv,GCoef,Exp_T,Exp_O,Exp_H,Type,WCoef,Is_Ogee,SpillHt,DesHd,#Openings
RCC Fboards ,168,0.9,59.806,,0,1,0.5, 3 ,1.8, 0 ,,, 1 ,0,0.8, 0 ,,,0,0,0, 0
      84
LW Gate Opening=1,GFRCCFB,0
LW Div RC= 0 ,False,,

Type RM Length L Ch R = 1 ,43.1500 ,56.333,105.41,111.457
XS GIS Cut Line= 2
597571.8794035995420564.08708309597025.4067035985420630.16758309
#Sta/Elev= 30
       0   54.97    5.99   52.16   10.99   52.75   13.99    50.6   24.98   50.82
   30.97   53.07   40.96   52.24   42.96    50.5   51.95   51.39   56.94   53.78
   67.93   52.54   85.91    54.8   102.9   51.27  113.89   52.68  116.88    49.8
  151.85   51.97  165.84   49.86  175.83   51.48  177.82   49.52  190.81   46.93
   205.8   47.64  210.79   49.36  213.79   51.33  216.78   56.29  223.78   59.85
  257.74   61.02  269.73   63.82  363.64   65.55  414.59   64.48  550.45   68.05
#Mann= 3 , 0 , 0
       0    .035       0       0      .1       0  216.78     .12       0
Bank Sta=0,216.78
XS Rating Curve= 0 ,0
Exp/Cntr=0.3,0.1

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
Type RM Length L Ch R = 1 ,42.9919 ,159.645,115.34,119.86
XS GIS Cut Line= 2
597531.1858035985420409.68748309596992.9203035985420476.67608309
#Sta/Elev= 30
       0   52.98    8.39   49.98   13.98   48.94   17.98   46.98   25.97   44.95
   54.94   44.75   56.94   43.82   79.91   42.49   85.91   42.64  104.89   46.58
  118.87   43.75  124.87    45.6  160.71   45.58  167.82   45.69  173.81   47.17
  178.81   45.86   185.8   46.71  202.78   46.48  223.76   47.04  230.75   47.85
  233.75   48.65  256.72    64.4  260.72   66.07  288.69   66.06  307.67   64.33
   374.6   64.51  394.58   65.18  406.56   67.03  428.54   64.91  542.42    65.4
#Mann= 3 , 0 , 0
       0    .035       0    8.39      .1       0  160.71     .12       0
Bank Sta=8.39,160.71
XS Rating Curve= 0 ,0
Exp/Cntr=0.3,0.1

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