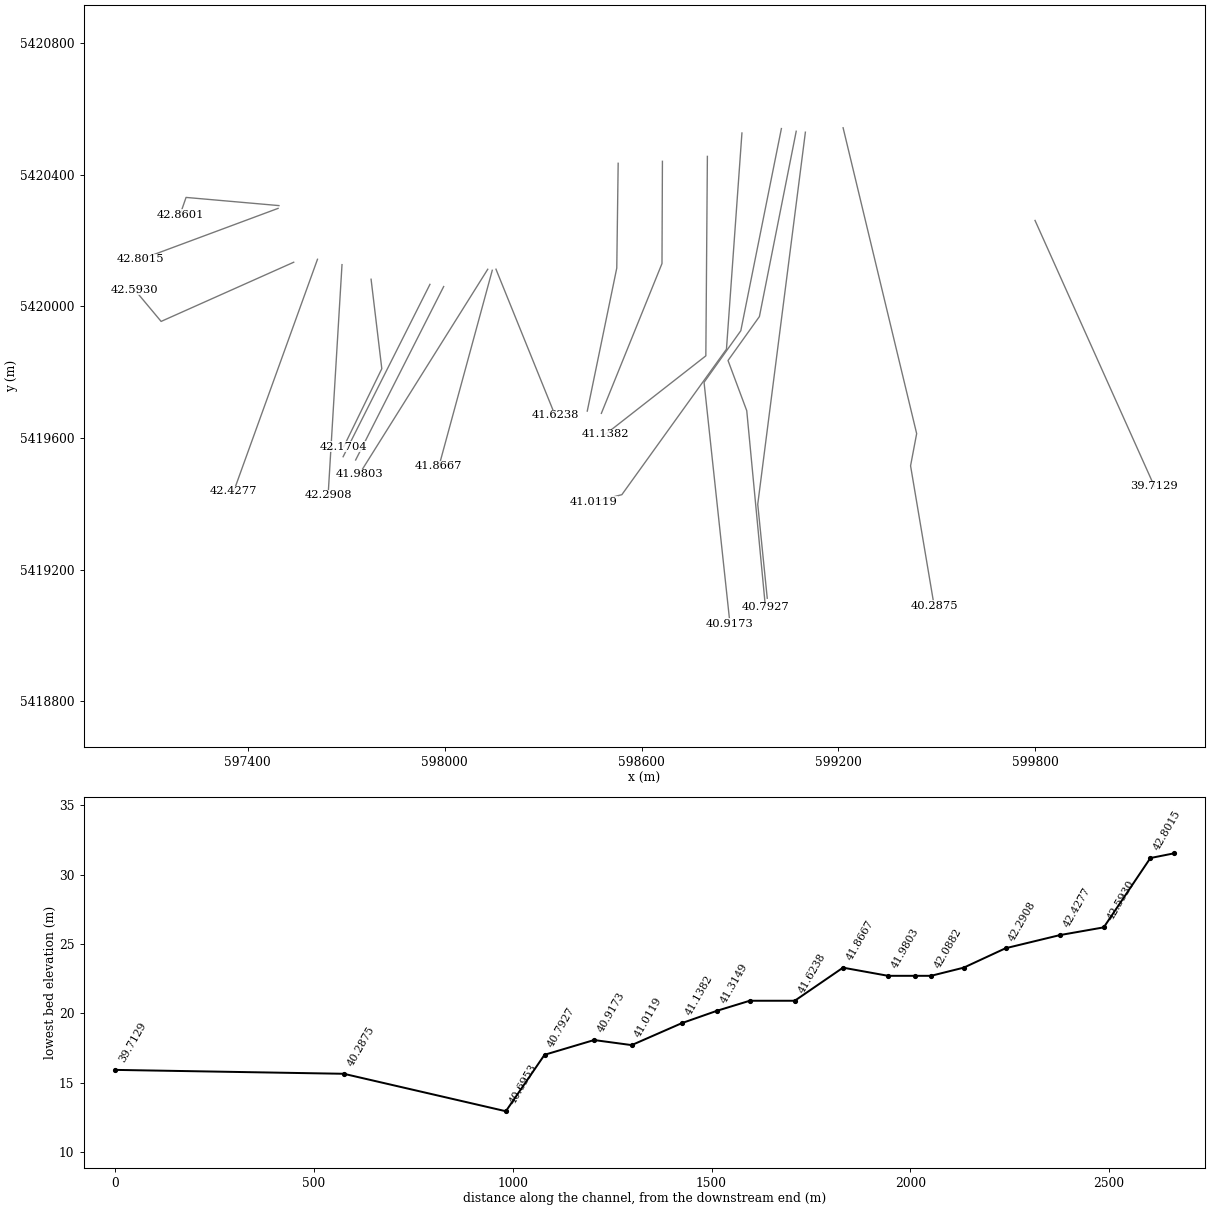
HEC-RAS study Exploits_FMM.prj: Exploits_FMM

--- Exploits_FMM.g01 (geometry) --- (continued)

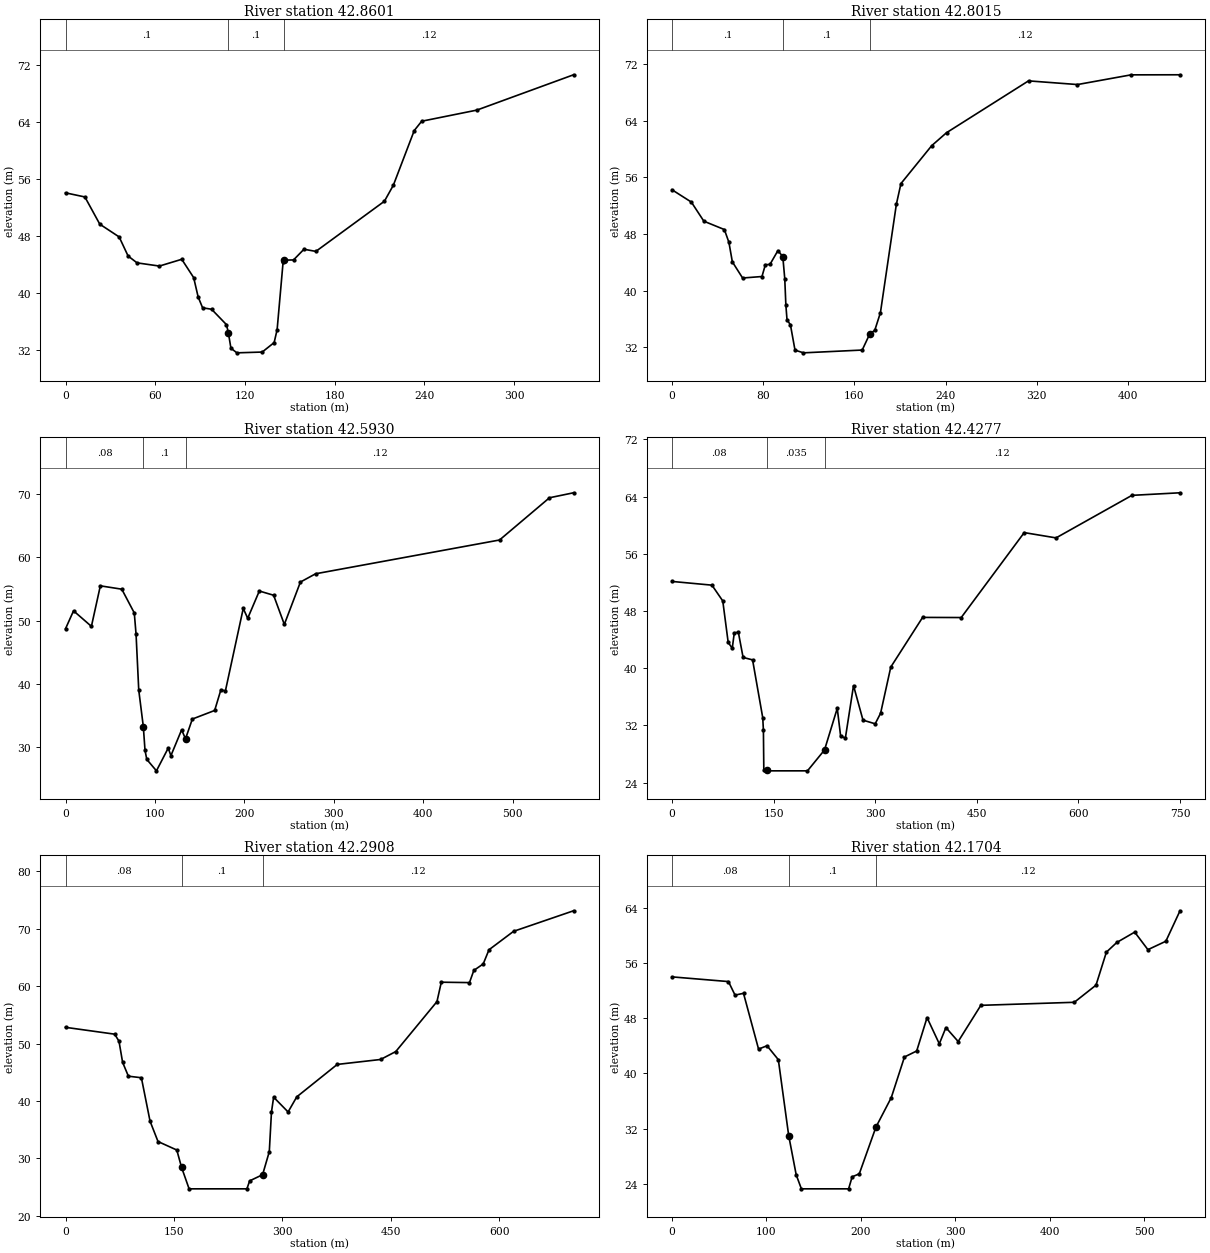
Type RM Length L Ch R = 1 ,42.8601 ,54.26,58.64,95.11
XS GIS Cut Line= 3
597495.0681035985420306.46288309597212.0706035985420331.30568309
597193.7150035985420278.68958309
#Sta/Elev= 30
       0      54   12.96   53.42   22.93    49.6   35.88   47.81   41.87   45.13
   47.85   44.17    62.8   43.72   77.75   44.67   85.72    42.1   88.71   39.39
    91.7   37.86   97.69   37.66  107.65    35.5  108.91   34.38  110.64   32.19
  114.63   31.54  131.58   31.65  139.55   32.98  141.54   34.79  145.53   44.26
  146.01   44.55  152.51   44.58  159.49   46.08  167.46   45.78  213.31   52.82
  219.29   55.07  233.25   62.74  238.23   64.05  275.11   65.61  339.81   70.57
#Mann= 3 , 0 , 0
       0      .1       0  108.91      .1       0  146.01     .12       0
Bank Sta=108.91,146.01
XS Rating Curve= 0 ,0
Exp/Cntr=0.3,0.1

Type RM Length L Ch R = 1 ,42.8015 ,102.183,117.272,109.268
XS GIS Cut Line= 2
597492.4103035985420297.95878309597074.4635035985420142.98428309
#Sta/Elev= 30
       0   54.23   16.99   52.49   27.98   49.79   45.97   48.61   49.97    46.8
   52.97   44.05   61.97   41.77   78.96   41.98   81.95   43.65   85.95   43.68
   92.95   45.64   97.23    44.8   98.95    41.7   99.94   37.92  100.94   35.87
  103.94   35.16  107.94   31.59 115.385  31.206  166.91    31.6  173.67   33.92
   177.9   34.37   182.9   36.88  196.89   52.19  200.89    55.1  227.87   60.45
  240.87   62.28  312.83    69.6   355.8   69.08  402.78   70.45  445.75   70.46
#Mann= 3 , 0 , 0
       0      .1       0   97.23      .1       0  173.67     .12       0
Bank Sta=97.23,173.67
XS Rating Curve= 0 ,0
Exp/Cntr=0.3,0.1

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
Type RM Length L Ch R = 1 ,42.5930 ,94.2,110.187,126.55
XS GIS Cut Line= 3
597540.0600035985420134.24288309597136.0700035985419954.32478309
597055.4412035985420050.61358309
#Sta/Elev= 30
       0   48.71    8.98   51.55   28.95   49.09   38.93   55.51   62.89   54.98
   76.87   51.22   78.86   47.84   81.86      39   86.99    33.2   88.85   29.47
   90.84   28.02  101.64  26.207   114.8   29.81   117.8   28.61  129.78    32.7
  134.13   31.28  141.76   34.41  166.71   35.77   173.7   39.06  178.69   38.85
  198.66   51.93  203.65   50.37  216.63   54.69   232.6   54.02  244.58    49.4
  262.55   56.11  279.52   57.42   485.1   62.77  540.92   69.46  567.83   70.25
#Mann= 3 , 0 , 0
       0     .08       0   86.99      .1       0  134.13     .12       0
Bank Sta=86.99,134.13
XS Rating Curve= 0 ,0
Exp/Cntr=0.3,0.1

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
Type RM Length L Ch R = 1 ,42.4277 ,122.945,136.96,163.235
BEGIN DESCRIPTION:
Grand Falls Powerhouse
END DESCRIPTION:
XS GIS Cut Line= 2
597612.5543035995420143.22608309597357.4101035995419438.13158309
#Sta/Elev= 30
       0   52.14   58.99   51.62   74.98   49.41   82.98    43.6   88.98    42.8
   91.98   44.95   97.98   45.03  104.98   41.51  118.97   41.17  133.97   33.08
  134.97   31.31  135.56  25.707 139.829  25.707     140   25.65     200   25.65
  225.14   28.57  243.95   34.39  248.95   30.49  255.94   30.24  267.94   37.57
  281.94   32.74  299.93   32.23  307.93   33.71  322.93   40.16  369.92   47.11
  426.91   47.09  519.89   58.97  566.88   58.23  678.85   64.18  749.84   64.54
#Mann= 3 , 0 , 0
       0     .08       0 139.829    .035       0  225.14     .12       0
Bank Sta=139.829,225.14
XS Rating Curve= 0 ,0
Exp/Cntr=0.3,0.1

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
Type RM Length L Ch R = 1 ,42.2908 ,102.61,105.315,118.92
XS GIS Cut Line= 2
597687.2405035985420126.97068309597644.8885035985419425.34598309
#Sta/Elev= 30
       0   52.83   67.99   51.64   73.99   50.42   78.99   46.74   86.99   44.32
  104.99   44.05  116.98   36.48  127.98   32.94  153.98   31.46  160.55   28.45
     171    24.7     251    24.7  254.75  26.087  272.67   27.16  281.96   31.18
  284.96   38.08  287.96   40.66  307.96   38.09  319.95   40.72  375.95   46.37
  435.94   47.23  456.94   48.61  513.93   57.31  519.93   60.69  558.92   60.62
  564.92   62.74  577.92   63.87  585.92   66.34  619.91   69.55   702.9   73.13
#Mann= 3 , 0 , 0
       0     .08       0  160.55      .1       0  272.67     .12       0
Bank Sta=160.55,272.67
XS Rating Curve= 0 ,0
Exp/Cntr=0.3,0.1

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
Type RM Length L Ch R = 1 ,42.1704 ,99.05,82.24,54.4
XS GIS Cut Line= 3
597775.8355035995420082.58128309597808.5226035985419810.51958309
597692.5833035995419573.53828309
#Sta/Elev= 30
       0   53.99   59.79   53.31   66.76   51.35   75.73   51.61   91.67   43.53
  100.64   44.02   112.6      42  123.57   31.01  131.53   25.32     137    23.3
     187    23.3  190.75  25.042  198.29   25.47  215.93   32.24  232.17   36.51
  246.12   42.39  259.07   43.26  270.03   48.09  283.01    44.3  290.01   46.65
     303   44.63  326.98   49.87  425.92   50.31   448.9   52.79  459.89   57.57
  470.89   58.97  489.87   60.47  503.86   57.93  522.85   59.15  537.84   63.56
#Mann= 3 , 0 , 0
       0     .08       0  123.57      .1       0  215.93     .12       0
Bank Sta=123.57,215.93
XS Rating Curve= 0 ,0
Exp/Cntr=0.3,0.1

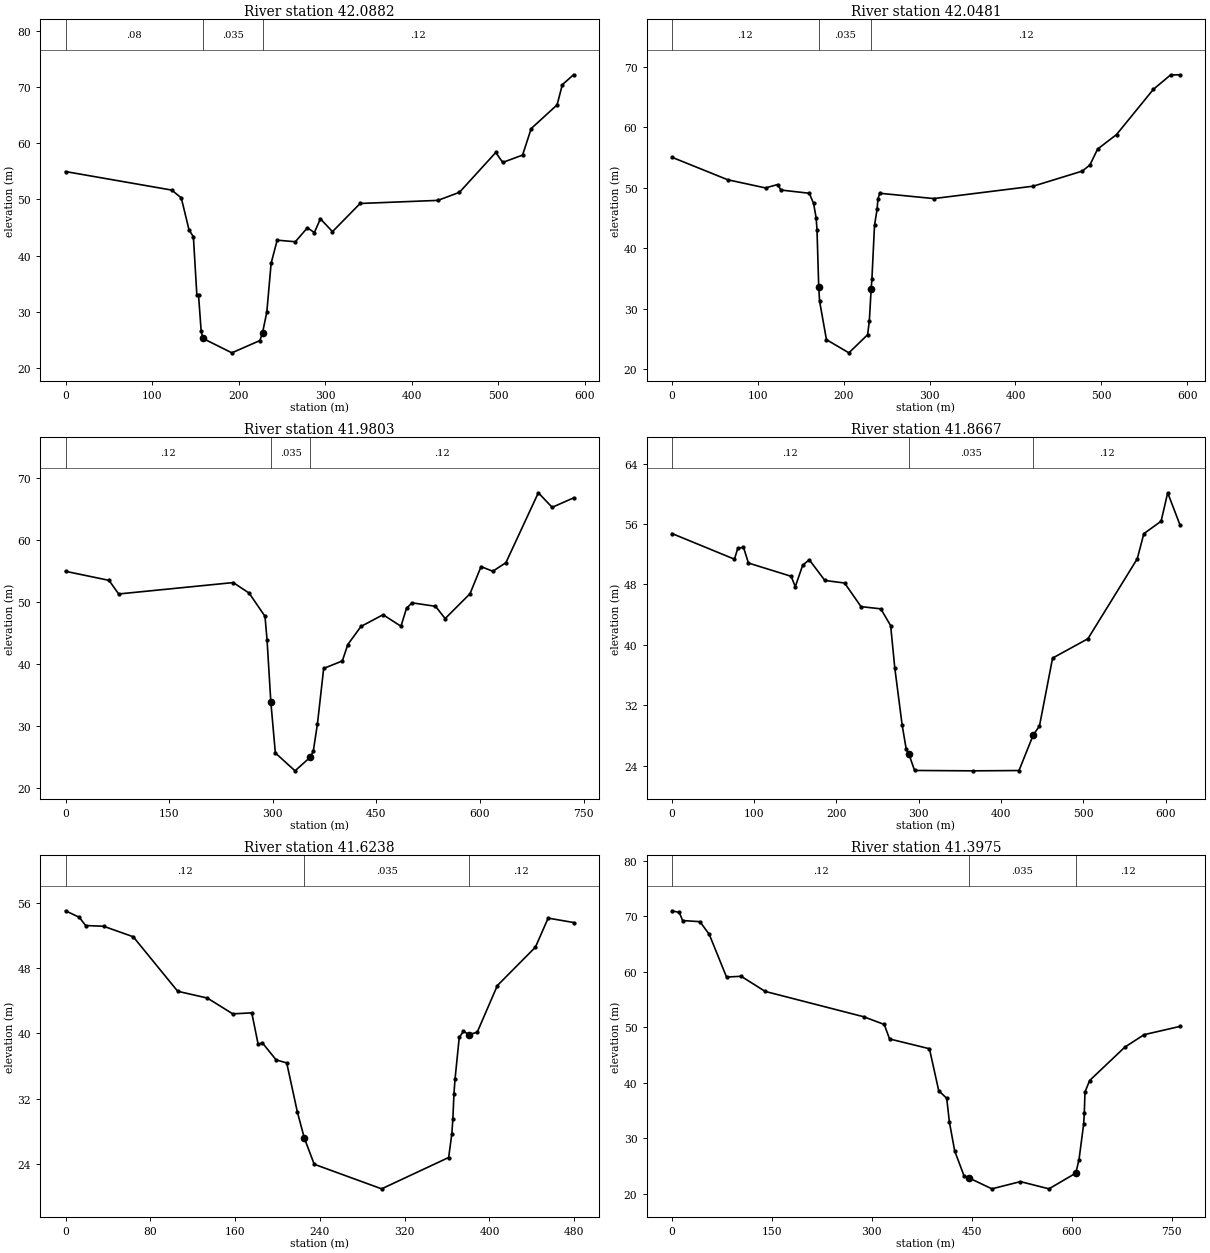
Type RM Length L Ch R = 1 ,42.0882 ,39.86,40.01,40.58
BEGIN DESCRIPTION:
US Mill Bridge
END DESCRIPTION:
XS GIS Cut Line= 2
597955.2319035995420067.01388309597690.6361035985419542.94588309
#Sta/Elev= 30
       0   54.97  122.81   51.67  133.79   50.28  142.78   44.56  147.77   43.38
  151.76   33.03  153.76   32.92  156.75   26.58  158.75   25.28 192.265  22.712
  224.65    24.9  227.74   26.31  232.63   29.97  237.63   38.68  244.62   42.76
  265.58   42.48  279.56   44.97  287.55   44.11  294.54   46.56  308.51   44.28
  340.46   49.29  430.32   49.84  455.28   51.28  497.22   58.37   505.2   56.59
  528.17    57.9  538.15   62.62  568.11   66.84   574.1   70.43  587.08   72.19
#Mann= 3 , 0 , 0
       0     .08       0  158.75    .035       0  227.74     .12       0
Bank Sta=158.75,227.74
XS Rating Curve= 0 ,0
Exp/Cntr=0.3,0.1

Type RM Length L Ch R = 1 ,42.0481 ,69.91,67.89,65.71
BEGIN DESCRIPTION:
DS Mill Bridge
END DESCRIPTION:
XS GIS Cut Line= 2
597997.0352035985420060.35468309597728.8329035985419533.00958309
#Sta/Elev= 30
       0   55.05   64.96   51.33  108.93   49.98  122.92   50.54  126.92   49.63
   159.9    49.1   164.9   47.41  167.89   45.05  168.89   43.03  170.89   33.66
  171.89   31.27  179.89   24.89 206.025  22.712  227.86   25.71  229.86   28.05
  231.98   33.35  232.85   34.94  235.85   43.77  238.85   46.43  239.85   48.12
  241.85    49.1  304.81   48.22  420.74   50.27   477.7   52.76  486.69   53.77
  495.69   56.41  517.67    58.8  560.65   66.29  580.64   68.66  591.63   68.69
#Mann= 3 , 0 , 0
       0     .12       0  170.89    .035       0  231.98     .12       0
Bank Sta=170.89,231.98
XS Rating Curve= 0 ,0
Exp/Cntr=0.3,0.1

Type RM Length L Ch R = 1 ,41.9803 ,105.17,113.56,170.98
XS GIS Cut Line= 2
598131.3099035985420112.89648309597740.0376035985419490.01148309
#Sta/Elev= 30
       0   54.93   62.96   53.47   76.96   51.27  242.86   53.11  265.85   51.41
  288.84   47.66  291.83   43.82   297.3   33.82  303.83    25.6 332.335  22.712
  354.62   24.94   358.8   25.92  364.79   30.31  373.79   39.25  400.77   40.45
  408.77   43.11  427.76   46.02  459.74   47.92  485.72   46.06  493.72   48.96
  501.71   49.84   535.7   49.28  549.69    47.3  585.67   51.31  601.66   55.69
  618.65   54.94  637.64   56.32  684.61   67.61   704.6   65.26  735.58   66.78
#Mann= 3 , 0 , 0
       0     .12       0   297.3    .035       0  354.62     .12       0
Bank Sta=297.3,354.62
XS Rating Curve= 0 ,0
Exp/Cntr=0.3,0.1

Type RM Length L Ch R = 1 ,41.8667 ,94.84,121.425,152.8
XS GIS Cut Line= 2
598145.1294035995420109.78868309597982.5971035995419513.98098309
#Sta/Elev= 30
       0   54.75   75.95   51.35   79.95   52.78   86.94   52.93   92.94   50.84
   144.9   49.08   149.9    47.7  158.89   50.55  166.89   51.27  185.87   48.53
  209.86   48.19  229.84   45.06  253.83   44.77  265.82   42.55  270.82   36.97
  279.81   29.36  284.81   26.14  287.96   25.52  294.93   23.35  365.47    23.3
  421.85   23.34  439.22   28.07   446.7   29.23  462.68   38.24  505.66   40.81
  565.61    51.4  573.61   54.73  594.59   56.38  602.59   60.15  617.58   55.88
#Mann= 3 , 0 , 0
       0     .12       0  287.96    .035       0  439.22     .12       0
Bank Sta=287.96,439.22
XS Rating Curve= 0 ,0
Exp/Cntr=0.3,0.1

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
Type RM Length L Ch R = 1 ,41.6238 ,150.015,113.19,92.86
XS GIS Cut Line= 2
  598156.4052036 5420113.0567831  598336.5925036 5419668.8636831
#Sta/Elev= 30
       0   55.04   12.98   54.24   18.97   53.23   35.95   53.14   63.91   51.85
  105.86   45.16  133.82   44.33  157.79   42.39  175.76   42.51  181.75   38.66
  185.75   38.83  198.73   36.74  208.72   36.37   218.7   30.38  225.31   27.15
  234.68   23.93 298.275  20.914  361.51   24.76  364.51   27.67   365.5   29.54
   366.5   32.55   367.5   34.34   371.5    39.5  375.49   40.25  380.76   39.84
  388.47   40.14  407.45   45.86   443.4   50.58  455.38   54.14  479.35    53.6
#Mann= 3 , 0 , 0
       0     .12       0  225.31    .035       0  380.76     .12       0
Bank Sta=225.31,380.76
XS Rating Curve= 0 ,0
Exp/Cntr=0.3,0.1

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
Type RM Length L Ch R = 1 ,41.3975 ,123.69,82.54,74.28
XS GIS Cut Line= 3
  598528.7382036 5420435.1340831  598524.4723036 5420116.4904831
  598434.5741036 5419681.6617831
#Sta/Elev= 30
       0   70.96   10.99   70.66   15.98    69.2   41.96      69   55.94   66.72
   81.92   59.03  103.89   59.17  139.86   56.45   287.7   51.89  318.67    50.5
  326.66   47.89  386.52   46.13  400.49   38.57  412.47   37.21  416.46   32.96
  424.44   27.73  438.41   23.27  446.16   22.86  480.27  20.914  523.13  22.214
  565.99  20.914  606.19   23.74  611.03   26.14  618.02   32.55  619.01   34.49
  620.01   38.32     627   40.41  679.88   46.42  708.82   48.66   762.7   50.15
#Mann= 3 , 0 , 0
       0     .12       0  446.16    .035       0  606.19     .12       0
Bank Sta=446.16,606.19
XS Rating Curve= 0 ,0
Exp/Cntr=0.3,0.1

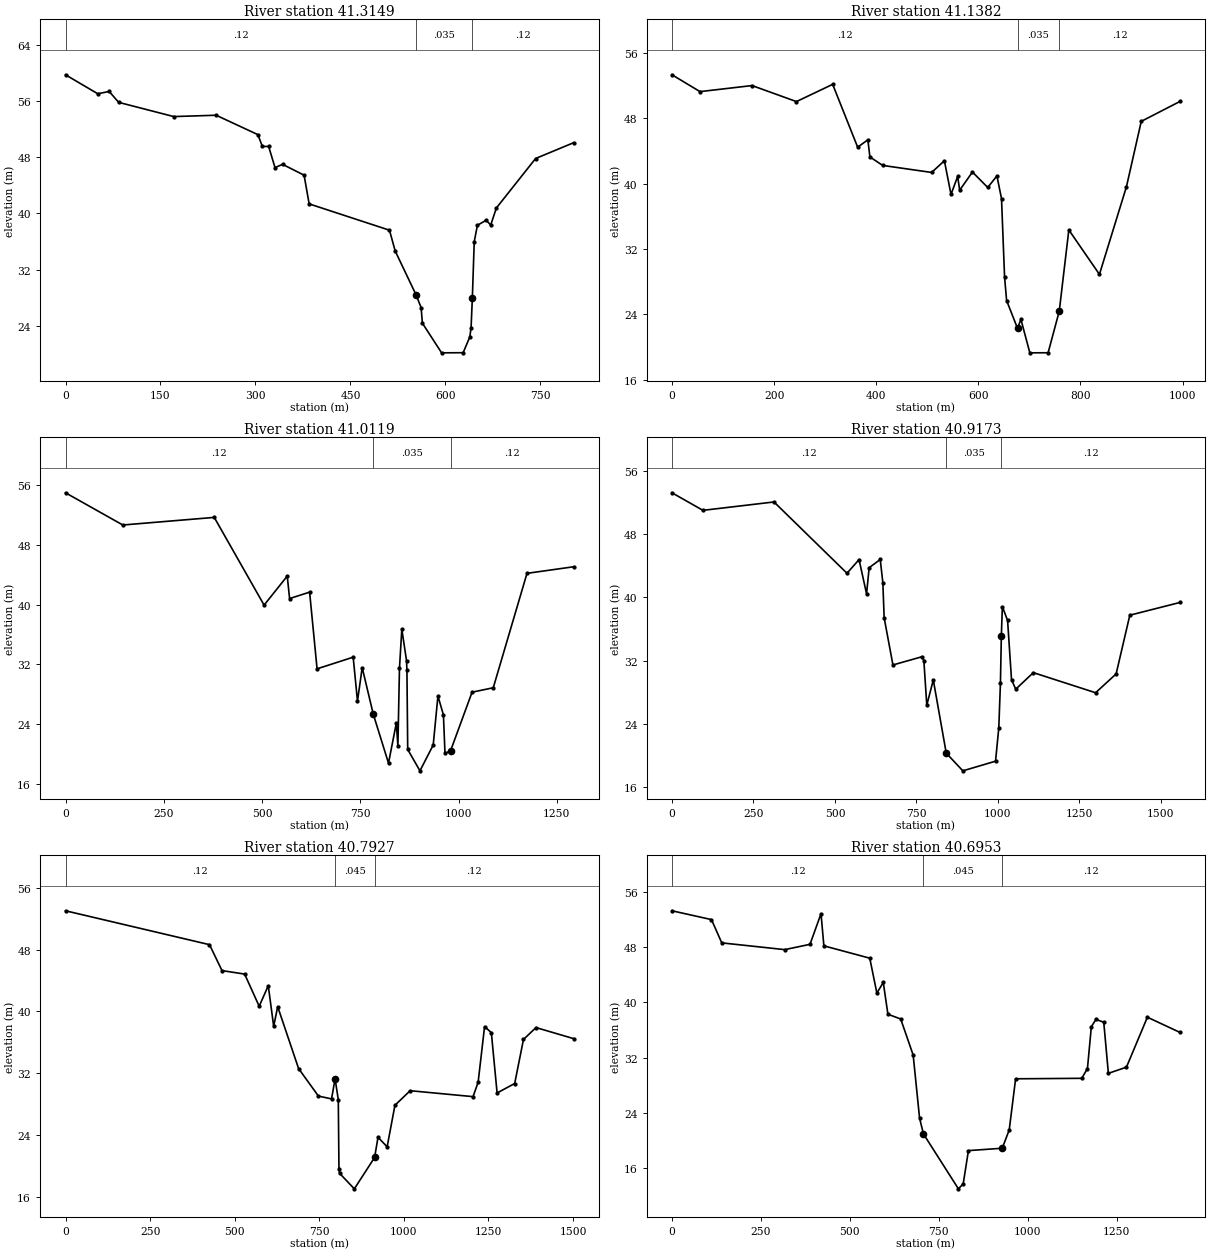
Type RM Length L Ch R = 1 ,41.3149 ,99.285,88.355,80.53
XS GIS Cut Line= 3
  598663.5854036 5420441.1382831  598662.2569036 5420130.2724831
  598477.5198036 5419674.8176831
#Sta/Elev= 30
       0   59.71   50.98   57.01   68.97   57.34   83.96   55.79  170.93   53.77
   237.9   53.96  303.87    51.2  310.87   49.53  320.86   49.52  330.85   46.52
  342.84   46.98   376.8   45.44  384.79   41.36  511.66   37.62  520.65   34.67
  553.45   28.47  561.61   26.63  563.61   24.41  593.99   20.19  628.03   20.21
  638.53   22.45  640.53   23.76  642.53   27.98  645.52      36  650.52   38.32
   664.5   39.04   671.5   38.34  680.49   40.78  742.42   47.81  802.36   50.05
#Mann= 3 , 0 , 0
       0     .12       0  553.45    .035       0  642.53     .12       0
Bank Sta=553.45,642.53
XS Rating Curve= 0 ,0
Exp/Cntr=0.3,0.1

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
Type RM Length L Ch R = 1 ,41.1382 ,63.25,126.28,148.07
XS GIS Cut Line= 3
  598800.5850036 5420456.0698831  598795.8666036 5419849.6393831
  598489.4724036 5419610.6914831
#Sta/Elev= 30
       0   53.32   54.95   51.26  156.86      52  243.78   50.04  314.71   52.15
  363.67   44.46  383.65   45.36  387.65   43.27  412.62   42.23  508.54   41.37
  533.52    42.8   546.5   38.68  559.49   40.88  563.49    39.2  588.47   41.42
  618.44   39.53  636.41   40.95   645.4   38.17   651.4   28.57  655.39    25.7
  676.79   22.29  683.36   23.41  700.87    19.3  736.68   19.31  758.51    24.4
  777.25   34.34  837.18    28.9  890.12   39.63  919.09   47.62     995   50.06
#Mann= 3 , 0 , 0
       0     .12       0  676.79    .035       0  758.51     .12       0
Bank Sta=676.79,758.51
XS Rating Curve= 0 ,0
Exp/Cntr=0.3,0.1

Type RM Length L Ch R = 1 ,41.0119 ,22.93,94.61,179.55
XS GIS Cut Line= 4
  598905.8685036 5420527.1683831  598858.6945036 5419869.8341831
  598539.9867036 5419427.5964831  598454.2653036 5419405.6642831
#Sta/Elev= 30
       0   54.99  145.78   50.67  378.44   51.69  505.25   39.93  564.17   43.82
  570.16   40.81  621.08   41.67  640.05   31.39  731.91   32.95  742.89   27.07
  754.87   31.55  783.07   25.31  821.82  18.745  841.73   24.12  845.72   21.05
  849.71   31.45   855.7    36.7  867.68   32.48  868.68   31.22  870.68   20.58
  901.83  17.715  935.57   21.18  947.55   27.74  961.53   25.22  965.52   20.07
  979.56   20.38 1034.41   28.26 1088.32   28.85 1174.18   44.19 1292.62   45.07
#Mann= 3 , 0 , 0
       0     .12       0  783.07    .035       0  979.56     .12       0
Bank Sta=783.07,979.56
XS Rating Curve= 0 ,0
Exp/Cntr=0.3,0.1

Type RM Length L Ch R = 1 ,40.9173 ,104.51,124.65,154.26
XS GIS Cut Line= 4
  599026.1086036 5420540.6695831  598902.4502036 5419926.0542831
  598790.4353036 5419769.2360831  598869.5036036 5419034.6033831
#Sta/Elev= 30
       0   53.22   94.99      51  312.97   52.06  536.94   43.05  573.94   44.78
  596.94   40.45  604.93   43.75  638.91   44.79   646.9   41.87   650.9   37.43
  677.86   31.46  767.73   32.51  772.72   32.01  781.71   26.38  801.68   29.57
  841.38   20.32  892.32   18.08  992.62    19.3 1002.62   23.53 1007.62   29.14
 1010.45   35.17 1013.61   38.83 1029.61   37.08 1041.61   29.61 1054.61    28.4
  1108.6   30.49 1299.58   27.95 1362.57   30.33 1404.56   37.75 1558.54   39.36
#Mann= 3 , 0 , 0
       0     .12       0  841.38    .035       0 1010.45     .12       0
Bank Sta=841.38,1010.45
XS Rating Curve= 0 ,0
Exp/Cntr=0.3,0.1

Type RM Length L Ch R = 1 ,40.7927 ,135.24,97.35,89.19
XS GIS Cut Line= 5
  599071.2521036 5420532.4645831  598959.0884036 5419969.0653831
  598863.4854036 5419835.5306831  598920.5291036 5419682.8368831
  598977.4507036 5419085.5791831
#Sta/Elev= 30
       0   53.04   425.6   48.65  462.56   45.29   529.5   44.84  572.46   40.67
  599.34   43.33  615.26   38.08  627.21   40.61  688.92    32.6  747.63   29.03
  786.39   28.67   796.8   31.28  806.27   28.57  808.26   19.59  810.24   19.02
 853.695  17.016  913.63   21.08  923.68    23.7  950.68   22.46  973.68   27.84
 1018.68   29.73 1204.66   28.96 1219.66   30.84 1238.66   38.04 1258.66   37.25
 1275.65   29.44 1327.65   30.66 1353.65   36.37 1390.64   37.91 1501.64   36.48
#Mann= 3 , 0 , 0
       0     .12       0   796.8    .045       0  913.63     .12       0
Bank Sta=796.8,913.63
XS Rating Curve= 0 ,0
Exp/Cntr=0.3,0.1

Type RM Length L Ch R = 1 ,40.6953 ,368.69,407.83,456.42
BEGIN DESCRIPTION:
R13 (RIS 2013)
END DESCRIPTION:
XS GIS Cut Line= 3
  599099.2065036 5420529.6327831  598954.0399036 5419398.3266831
  598982.9888036 5419112.7675831
#Sta/Elev= 30
       0   53.31  110.96   52.03  139.95   48.65  316.88   47.67  387.86   48.44
  418.85   52.89  426.84   48.22   555.8   46.43  575.79   41.36  593.78   42.91
  606.78   38.29  642.76    37.6  677.75   32.37  695.75   23.21   706.6   20.92
  804.92  12.946  818.38  13.676  833.05  18.496  928.07   18.84  947.65   21.49
  965.65   28.92 1151.55   28.99 1167.49   30.41 1178.46   36.48 1191.41   37.54
 1213.34   37.13 1226.29   29.71 1277.12   30.61 1335.92   37.86 1427.61   35.65
#Mann= 3 , 0 , 0
       0     .12       0   706.6    .045       0  928.07     .12       0
Bank Sta=706.6,928.07
XS Rating Curve= 0 ,0
Exp/Cntr=0.3,0.1

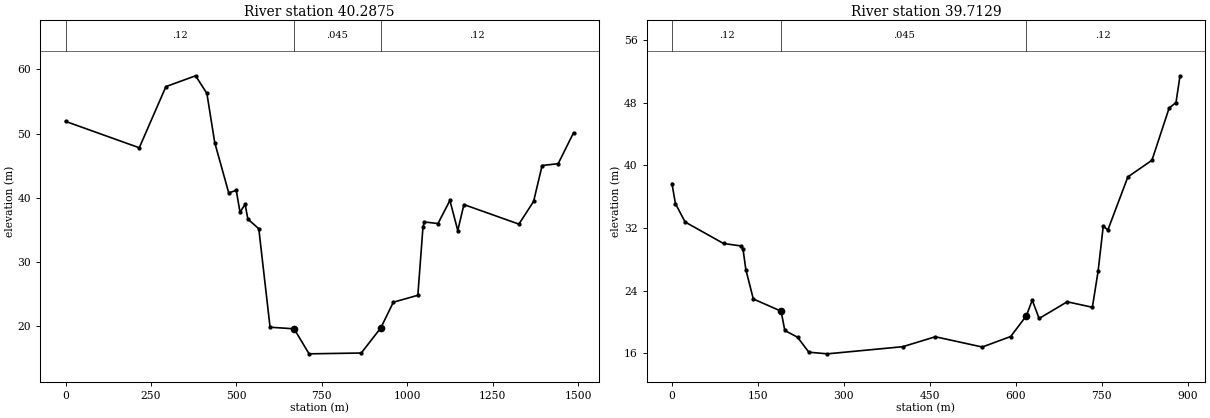
Type RM Length L Ch R = 1 ,40.2875 ,574.92,574.64,644.45
BEGIN DESCRIPTION:
R14 (RIS 2013)
END DESCRIPTION:
XS GIS Cut Line= 4
599214.1084035985420543.04368309599438.2531035985419613.21718309
599419.7029035995419515.35288309599491.4356035985419090.56948309
#Sta/Elev= 30
       0   51.91  215.88   47.79  293.83   57.33  380.79   59.02  413.77   56.27
  436.75   48.59  477.73   40.75  499.72   41.15  510.71   37.74   525.7   38.98
   533.7   36.67  565.68   35.16  598.66    19.8  669.01   19.55  712.83  15.647
  865.61  15.777  922.84    19.7  959.46    23.7 1031.17   24.78 1046.11   35.38
  1050.1   36.22 1090.06   35.97 1125.04   39.57 1148.03   34.88 1166.02   38.93
 1326.94   35.88 1369.92   39.42  1394.9   45.02 1441.88   45.31 1486.86   50.13
#Mann= 3 , 0 , 0
       0     .12       0  669.01    .045       0  922.84     .12       0
Bank Sta=669.01,922.84
XS Rating Curve= 0 ,0
Exp/Cntr=0.3,0.1

Type RM Length L Ch R = 1 ,39.7129 ,581.88,619.1,724.22
BEGIN DESCRIPTION:
Gorge Park - R15 (RIS 2013)
END DESCRIPTION:
XS GIS Cut Line= 2
599798.9278035985420261.30898309600162.7547035985419452.58748309
#Sta/Elev= 30
       0   37.66       6    35.1   22.99   32.75   89.98   30.01  120.97   29.69
  123.97    29.3  128.97   26.67  141.97   22.93   190.5   21.37  196.95   18.91
  219.12  18.048  238.91  16.138  271.27  15.928  402.76  16.838  459.76  18.108
   541.6  16.798  591.18  18.138  618.51   20.77  628.85   22.78  640.85   20.44
  689.84   22.57  733.83   21.87  743.83   26.48  752.82   32.23  760.82   31.73
  795.81   38.51   837.8   40.63   867.8   47.29   879.8      48  886.79   51.41
#Mann= 3 , 0 , 0
       0     .12       0   190.5    .045       0  618.51     .12       0
Bank Sta=190.5,618.51
XS Rating Curve= 0 ,0
Exp/Cntr=0.3,0.1