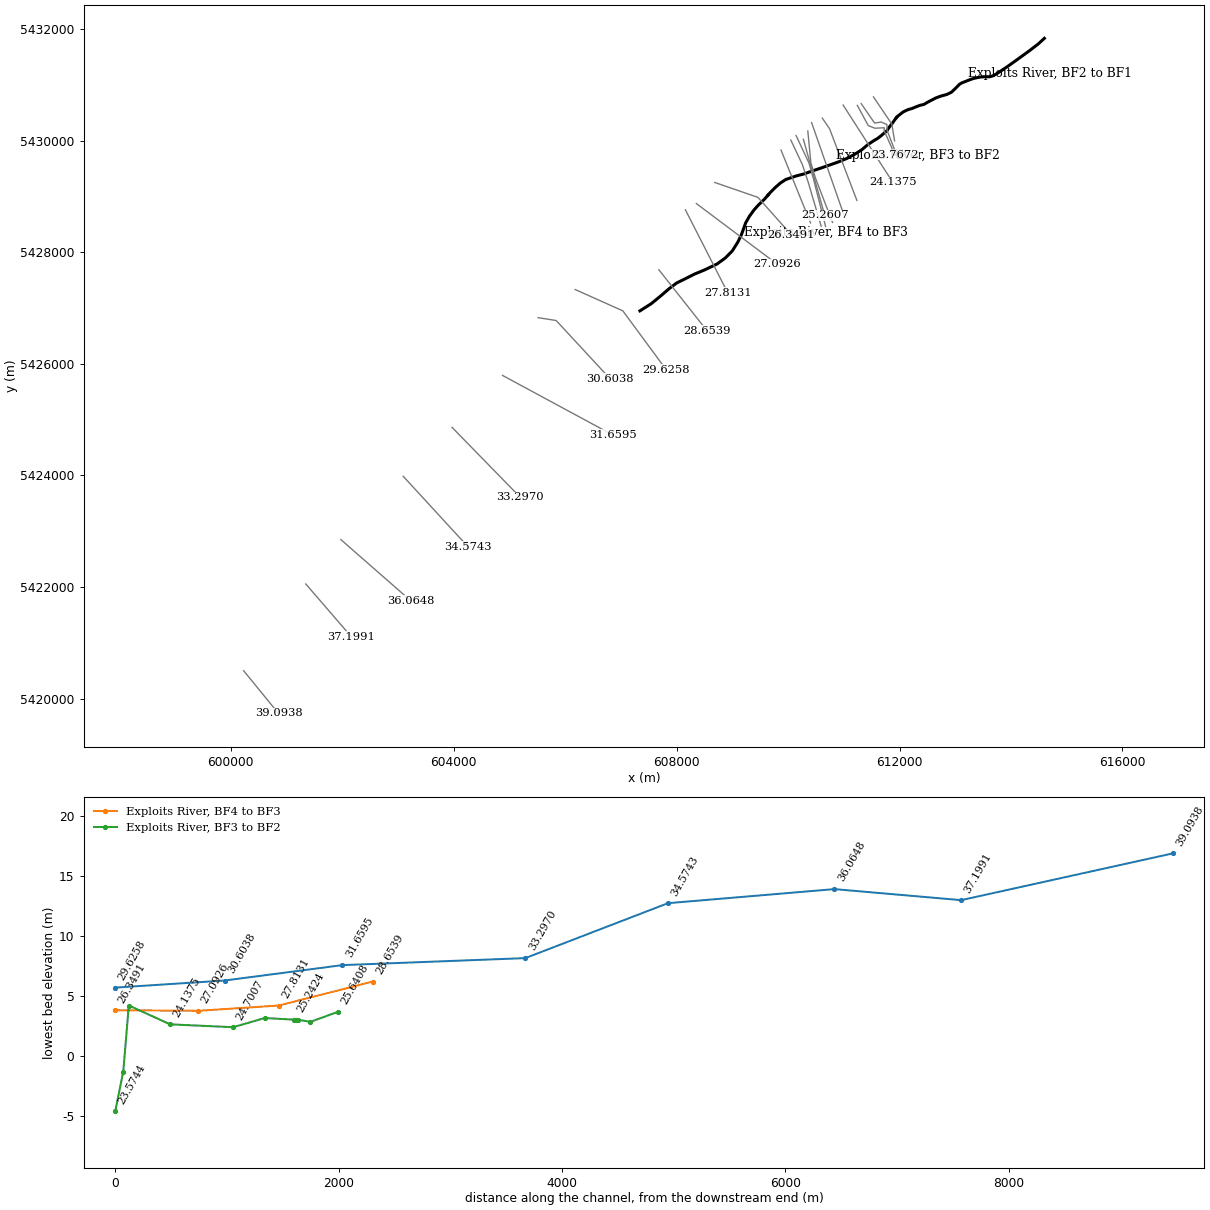
HEC-RAS study Exploits_FMM.prj: Exploits_FMM

--- Exploits_FMM.g01 (geometry) --- (continued)

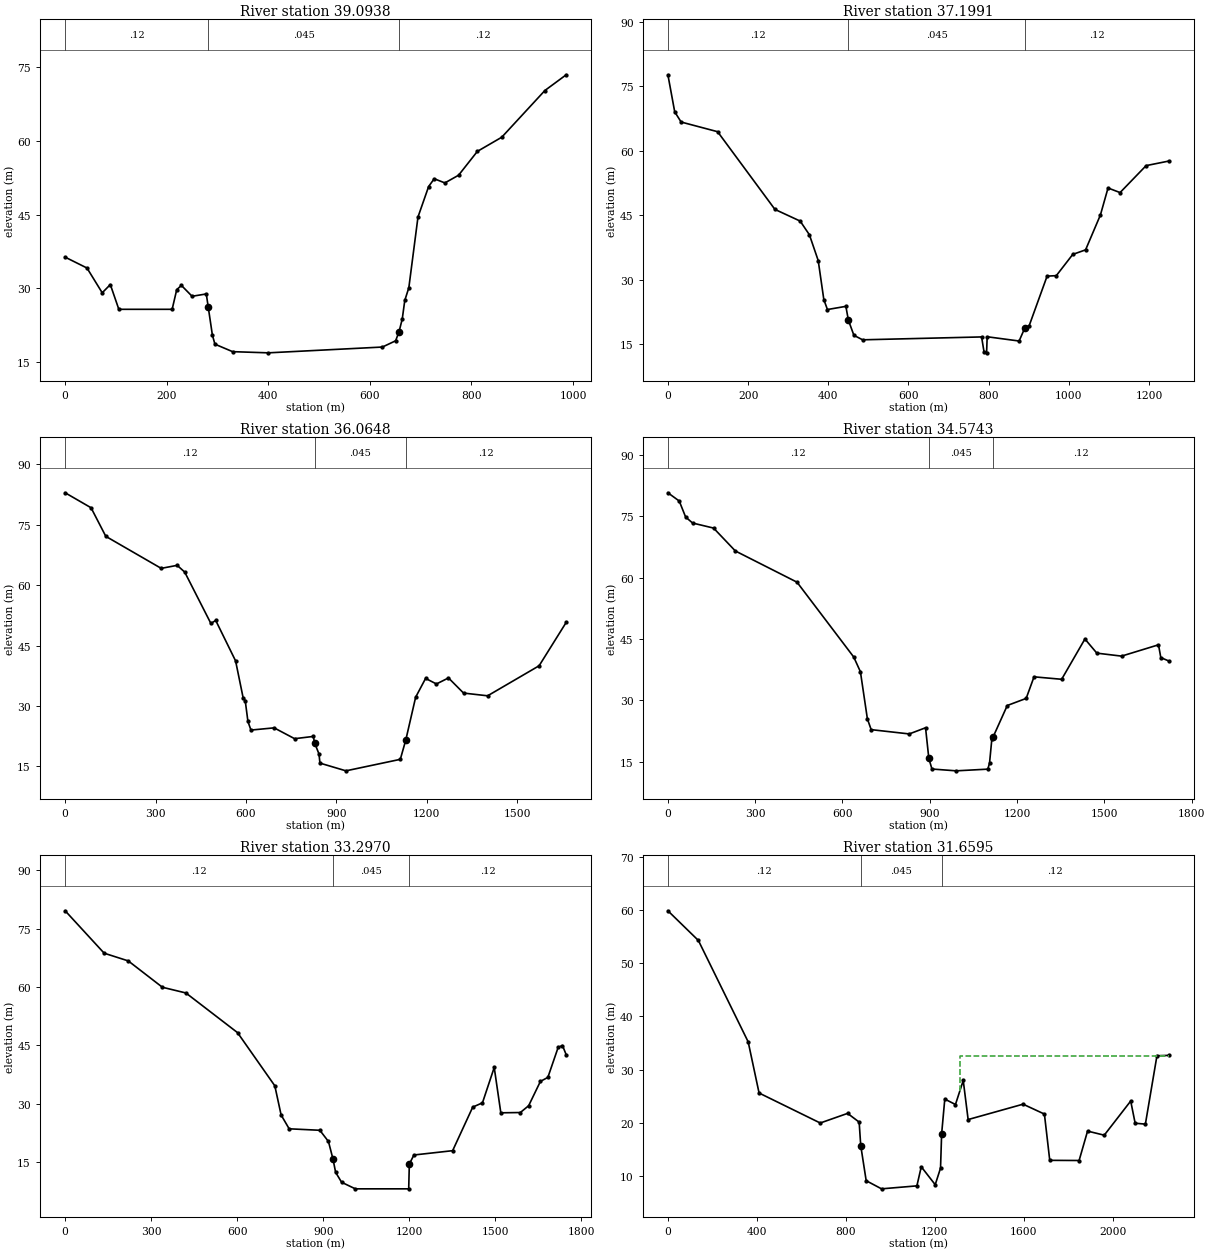
Type RM Length L Ch R = 1 ,39.0938 ,1968.3,1894.64,1905.8
BEGIN DESCRIPTION:
Grand Falls Wastewater Treatment Facility - R16 (RIS 2013)
END DESCRIPTION:
XS GIS Cut Line= 2
600233.6252035985420499.83648309600857.4626035985419735.54198309
#Sta/Elev= 30
       0   36.33   42.98   34.12   72.97   29.08   88.96   30.75  105.68  25.717
  210.66  25.717  219.69  29.717   228.9   30.58  249.89   28.37  277.88   28.84
  281.69    26.2  289.87   20.49  294.87   18.62  329.73  17.097  399.88  16.857
  624.63  18.037  650.72   19.31  657.48   21.19  663.71   23.73  668.71   27.52
  676.71   30.12   694.7    44.5  715.69   50.71  726.69   52.29  747.68   51.44
  774.67   53.01  811.65   57.86  859.63   60.74   944.6   70.25  986.58   73.45
#Mann= 3 , 0 , 0
       0     .12       0  281.69    .045       0  657.48     .12       0
Bank Sta=281.69,657.48
XS Rating Curve= 0 ,0
Exp/Cntr=0.3,0.1

Type RM Length L Ch R = 1 ,37.1991 ,1163.25,1134.34,1181.2
BEGIN DESCRIPTION:
R17 (RIS 2013)
END DESCRIPTION:
XS GIS Cut Line= 2
601348.7466035985422054.15248309602165.4492035985421108.26418309
#Sta/Elev= 30
       0   77.64      17   69.02   32.99   66.65  123.97    64.4  266.93   46.33
  329.92   43.61  352.91   40.43   374.9   34.43   388.9   25.35   397.9   23.04
  443.89   23.78  450.13   20.57  463.94  17.037   485.7  15.997  782.41  16.667
  788.66  13.057  794.85  12.967  796.27  16.707  875.96  15.717  890.69   18.86
  900.77   19.21  945.76   30.81  968.75   30.92 1009.74   35.86 1041.73   36.92
 1078.72   45.03 1097.72   51.31 1127.71   50.24  1192.7   56.51 1249.68   57.58
#Mann= 3 , 0 , 0
       0     .12       0  450.13    .045       0  890.69     .12       0
Bank Sta=450.13,890.69
XS Rating Curve= 0 ,0
Exp/Cntr=0.3,0.1

Type RM Length L Ch R = 1 ,36.0648 ,1505.09,1490.5,1521.76
BEGIN DESCRIPTION:
R18 (RIS 2013)
END DESCRIPTION:
XS GIS Cut Line= 2
601977.4418035985422849.76258309603229.9842035985421755.09568309
#Sta/Elev= 30
       0   82.94   85.97   79.22  134.96   72.12   318.9   64.17  371.88   64.92
  396.88   63.25  483.85   50.48  499.84   51.24  565.82   41.19  590.81   32.05
  597.81   31.31  606.81   26.14  616.81   24.01  693.78   24.56  761.76   21.87
  823.74   22.43  828.53   20.75  842.73   18.07  845.86  15.806  932.16  13.886
 1112.65   16.74  1130.8   21.53 1163.63   32.18 1196.62   36.84 1232.61   35.46
  1272.6   36.96 1322.58    33.2 1402.55   32.52  1573.5   39.98 1663.47   50.76
#Mann= 3 , 0 , 0
       0     .12       0  828.53    .045       0  1130.8     .12       0
Bank Sta=828.53,1130.8
XS Rating Curve= 0 ,0
Exp/Cntr=0.3,0.1

Type RM Length L Ch R = 1 ,34.5743 ,1277.25,1277.24,1303.62
XS GIS Cut Line= 2
603096.5604035985423984.08028309604262.4876035985422716.83918309
#Sta/Elev= 30
       0   80.79   38.98   78.77   60.96   74.85   84.95   73.38  156.91   72.15
  231.87   66.54  443.74    58.9  638.63   40.58  661.62   36.98   685.6   25.43
   698.6    22.8  829.52   21.75  885.49   23.26  896.75   15.75  907.48   13.16
  990.71  12.715 1099.37   13.13 1105.36    14.6 1113.36   20.55 1118.34   21.12
 1166.32   28.71 1231.29   30.45 1258.27   35.73 1353.21   35.13 1433.16   44.99
 1474.14   41.53 1559.08    40.8 1686.01   43.57    1694   40.44 1721.98   39.59
#Mann= 3 , 0 , 0
       0     .12       0  896.75    .045       0 1118.34     .12       0
Bank Sta=896.75,1118.34
XS Rating Curve= 0 ,0
Exp/Cntr=0.3,0.1

Type RM Length L Ch R = 1 ,33.2970 ,1594.2,1637.57,1749.24
BEGIN DESCRIPTION:
R20 (RIS 2013)
END DESCRIPTION:
XS GIS Cut Line= 2
603972.1877035985424861.26948309605192.9212035985423611.68818309
#Sta/Elev= 30
       0   79.59  135.99   68.69  219.99   66.71  338.98   59.94  420.98   58.47
  600.97   48.28  730.96   34.62  752.96   27.11  780.96   23.57  887.95   23.19
  917.95   20.31  933.89   15.75  942.97  12.384   963.8   9.834  1011.7   8.144
 1197.74   8.144 1199.93   14.52 1215.93   16.84 1350.92   17.95 1420.92   29.14
 1454.92   30.25 1495.91   39.33 1518.91   27.68 1586.91   27.75  1615.9    29.5
  1656.9   35.75  1682.9   36.78  1718.9   44.51  1733.9   44.97  1746.9   42.59
#Mann= 3 , 0 , 0
       0     .12       0  933.89    .045       0 1199.93     .12       0
Bank Sta=933.89,1199.93
XS Rating Curve= 0 ,0
Exp/Cntr=0.3,0.1

Type RM Length L Ch R = 1 ,31.6595 ,1164.99,1055.65,1002.89
BEGIN DESCRIPTION:
Great Rattling Brook - R21 (RIS 2013)
END DESCRIPTION:
XS GIS Cut Line= 2
604876.8866035985425792.79938309606859.2917035995424723.62268309
#Sta/Elev= 30
       0   59.85  136.96   54.27   360.9    35.2  409.88   25.58   684.8   19.94
  807.77   21.75  859.76   20.11   866.8   15.71  891.32   9.091  960.35   7.561
 1119.26   8.121 1138.94  11.711 1201.65   8.341 1225.53  11.461 1230.45   17.88
 1244.64   24.44 1292.63   23.42 1327.62   27.94 1349.61   20.59 1596.54   23.48
 1692.51   21.62  1716.5   12.92 1848.46   12.89 1886.45   18.42 1961.43   17.65
  2080.4   24.07 2100.39    19.9 2146.38   19.73 2198.37   32.59 2252.35   32.66
#Mann= 3 , 0 , 0
       0     .12       0   866.8    .045       0 1230.45     .12       0
#XS Ineff= 2 , 0
                            1312            32.5
Permanent Ineff=
       F       T
Bank Sta=866.8,1230.45
XS Rating Curve= 0 ,0
Exp/Cntr=0.3,0.1

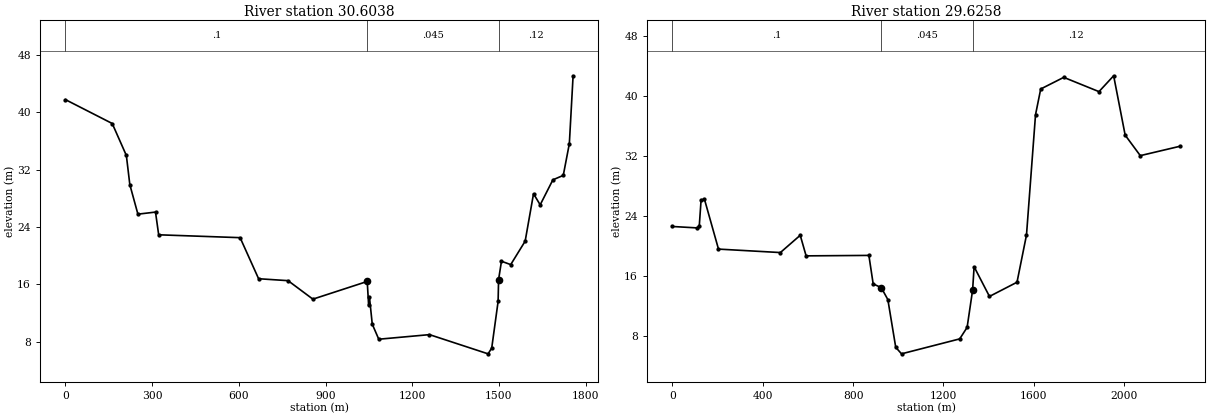
Type RM Length L Ch R = 1 ,30.6038 ,995.75,978.05,1026.58
BEGIN DESCRIPTION:
R22 (RIS 2013)
END DESCRIPTION:
XS GIS Cut Line= 3
605516.7172035985426827.71408309605840.1641035985426776.41938309
606811.6739035985425728.32808309
#Sta/Elev= 30
       0   41.75  161.75   38.42  210.67   33.96  222.65   29.89  250.61   25.77
  311.51   26.06   322.5   22.89  604.32   22.49  668.28   16.76  770.21   16.49
  856.16   13.91 1044.21   16.38 1049.04   13.05 1051.88  14.199 1061.61  10.419
  1084.1   8.319 1259.67   8.959 1462.36   6.279 1474.97   7.079  1497.1  13.589
 1498.76   16.65 1508.75    19.2 1540.73   18.73  1590.7      22 1619.68   28.62
 1642.67   27.07 1686.64   30.56 1722.62   31.18  1743.6    35.6  1756.6   45.08
#Mann= 3 , 0 , 0
       0      .1       0 1044.21    .045       0 1498.76     .12       0
Bank Sta=1044.21,1498.76
XS Rating Curve= 0 ,0
Exp/Cntr=0.3,0.1

Type RM Length L Ch R = 1 ,29.6258 ,978.79,971.85,1004.28
BEGIN DESCRIPTION:
R23 (RIS 2013)
END DESCRIPTION:
XS GIS Cut Line= 3
606181.7716035985427331.43518309607036.3379035985426949.59128309
607814.8299035985425893.65648309
#Sta/Elev= 30
       0   22.64     110   22.45     119   22.75     127   26.19     142   26.25
     204   19.63     478   19.17     566   21.47     592   18.73     870   18.79
     889      15  924.81    14.5     954   12.91  988.89   6.559  1014.5   5.689
 1272.22   7.679 1304.99   9.209 1329.31   14.17 1335.96   17.28 1403.95   13.33
 1525.94   15.22 1567.94   21.51 1607.93   37.52 1630.93   40.94 1732.92   42.49
 1888.91   40.59  1953.9    42.7 2004.89    34.8 2071.89   32.07 2247.88   33.32
#Mann= 3 , 0 , 0
       0      .1       0  924.81    .045       0 1329.31     .12       0
Bank Sta=924.81,1329.31
XS Rating Curve= 0 ,0
Exp/Cntr=0.3,0.1

River Reach=Exploits River  ,BF4 to BF3
Reach XY= 30
607343.2426745345426949.64970111     607345.9132    5426950.9593
     607547.4921    5427079.5337     607712.9027    5427215.0511
     607865.6824    5427346.1726     608001.8888    5427449.5581
     608149.1006    5427521.3414     608325.7119    5427610.4406
     608496.2256    5427680.4211     608553.7015     5427707.696
     608584.7843    5427722.4643     608599.9284    5427729.6432
     608725.4925    5427789.2625     608874.3401    5427897.0445
     608999.6626    5428023.5751     609099.1736     5428181.503
     609163.0484    5428313.5636     609223.0258    5428479.6001
     609239.6293    5428525.5251     609240.6419    5428528.3582
     609304.7675    5428641.3738     609340.6036    5428690.7819
      609360.451    5428718.1712     609360.8441    5428718.6963
     609384.6299     5428751.497     609389.9918     5428758.907
     609402.2218    5428772.4971      609465.085    5428842.4396
     609575.8523    5428949.7203609642.395047543 5429026.2014789

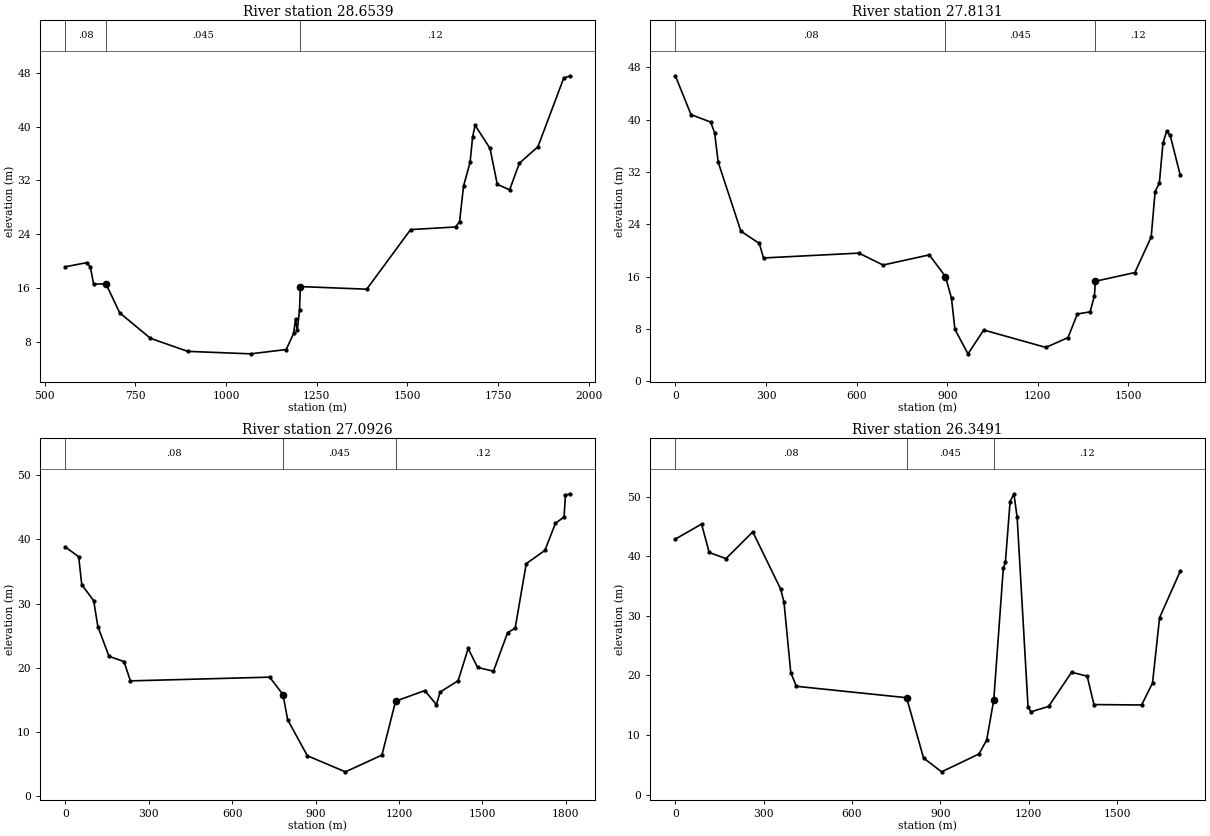
Type RM Length L Ch R = 1 ,28.6539 ,904.14,840.86,800.26
BEGIN DESCRIPTION:
Hobbs Park - R24 (RIS 2013)
END DESCRIPTION:
XS GIS Cut Line= 2
  607682.2606036 5427686.4279831  608544.8664036 5426594.5330831
#Sta/Elev= 30
     557   19.15  615.92   19.76  625.91   19.15  634.91   16.57     669    16.6
  706.87   12.29  791.59     8.5  894.17    6.56  1067.7    6.19 1165.96    6.83
 1186.31    9.23 1191.56   11.34 1196.35    9.71 1202.58   12.64 1204.83    16.2
 1387.81   15.81 1508.79   24.68 1632.77   25.07 1643.77   25.86 1654.77   31.16
 1672.76   34.68 1679.76    38.5 1686.76   40.19 1727.75   36.76 1747.75   31.41
 1781.75    30.6 1808.74   34.57 1859.73      37 1930.72    47.2 1948.72   47.57
#Mann= 3 , 0 , 0
     557     .08       0     669    .045       0 1204.83     .12       0
Bank Sta=669,1204.83
XS Rating Curve= 0 ,0
Exp/Cntr=0.3,0.1

Type RM Length L Ch R = 1 ,27.8131 ,616.01,720.41,859.47
BEGIN DESCRIPTION:
Greenridge Rd - R25 (RIS 2013)
END DESCRIPTION:
XS GIS Cut Line= 2
608158.5093035995428760.83048309608918.8907035985427272.76338309
#Sta/Elev= 30
       0   46.69   51.97   40.75  116.94   39.62  129.93      38  141.92   33.48
  216.88   22.95  277.85   21.07  291.84   18.85  607.67   19.59  687.62   17.77
  840.54   19.32  894.17   16.01  914.14  12.679  925.42   7.939   968.7   4.199
 1020.79   7.839 1226.45   5.179 1299.72   6.679 1330.83  10.289 1373.01  10.619
 1387.32  13.089 1390.24   15.29 1521.17   16.62 1575.15   22.06 1588.14      29
 1602.13   30.29 1614.12   36.38 1626.12    38.2 1638.11   37.57 1671.09   31.55
#Mann= 3 , 0 , 0
       0     .08       0  894.17    .045       0 1390.24     .12       0
Bank Sta=894.17,1390.24
XS Rating Curve= 0 ,0
Exp/Cntr=0.3,0.1

Type RM Length L Ch R = 1 ,27.0926 ,742.06,743.57,752.95
BEGIN DESCRIPTION:
Market Rd - R26 (RIS 2013)
END DESCRIPTION:
XS GIS Cut Line= 2
608355.4606035995428872.55618309609808.3645035985427783.83918309
#Sta/Elev= 30
       0   38.82   47.99   37.29   58.99   32.94  101.97   30.44  116.97   26.41
  156.96   21.77  210.95   20.95  233.94   17.94  734.82   18.52  782.67   15.81
  799.56  11.869  870.32   6.269 1007.23   3.759 1138.53   6.369 1187.63   14.77
 1292.68   16.43 1334.67   14.23 1347.66   16.19 1412.65   17.97 1448.64   22.99
 1482.63   20.03 1539.62   19.45 1590.61   25.47  1617.6   26.14 1657.59   36.22
 1724.58   38.28 1762.57    42.5 1793.56    43.5 1798.56   46.91 1815.56   47.11
#Mann= 3 , 0 , 0
       0     .08       0  782.67    .045       0 1187.63     .12       0
Bank Sta=782.67,1187.63
XS Rating Curve= 0 ,0
Exp/Cntr=0.3,0.1

Type RM Length L Ch R = 1 ,26.3491 ,771.02,708.28,710.07
BEGIN DESCRIPTION:
Exploits Ln - R27 (RIS 2013)
END DESCRIPTION:
XS GIS Cut Line= 3
608685.2408035985429250.72878309609459.4595035995428983.85958309
610055.9901035995428316.22838309
#Sta/Elev= 30
       0   42.91   88.99   45.43  114.99   40.66  171.98   39.63  262.98   44.12
  357.97   34.47  368.97    32.3  391.96   20.48  410.96   18.18  785.28   16.26
  842.77   6.139  904.04   3.809  1030.9   6.809 1057.31   9.149 1081.32   15.93
 1113.69   38.03 1120.69   38.98 1136.68   49.22 1149.67   50.52 1160.66   46.54
 1197.63   14.74 1207.62   13.89 1267.58    14.8 1345.52   20.54 1398.48   19.88
 1421.46   15.11 1583.34   15.04 1620.31   18.72 1644.29    29.7 1714.24   37.49
#Mann= 3 , 0 , 0
       0     .08       0  785.28    .045       0 1081.32     .12       0
Bank Sta=785.28,1081.32
XS Rating Curve= 0 ,0
Exp/Cntr=0.3,0.1

River Reach=Exploits River  ,BF3 to BF2
Reach XY= 30
609642.395047543 5429026.2014789     609643.8462    5429027.9299
      609680.094    5429069.6141     609769.9196    5429159.7003
     609771.1849    5429160.8069     609773.7455    5429163.0205
     609804.7866    5429190.0673     609814.4847    5429198.4944
     609866.1774    5429243.5019     609937.4002    5429289.1467
     609960.6224    5429304.0115     610148.1457    5429367.8673
     610285.2447    5429403.5311     610426.3872    5429454.0769
     610584.4277    5429506.9552     610755.0814    5429566.3493
     610910.9747    5429621.3092     611054.1254     5429680.341
     611197.0431    5429756.2983     611325.0708     5429838.419
     611423.4382    5429922.2587     611528.3213    5429993.4853
     611608.1275    5430041.1033     611664.7054    5430084.1755
     611773.1234    5430176.2571     611773.5386    5430176.6226
     611827.5051    5430257.7575     611871.2467    5430311.2498
     611919.0221    5430379.6041611946.6080034565430415.72603256

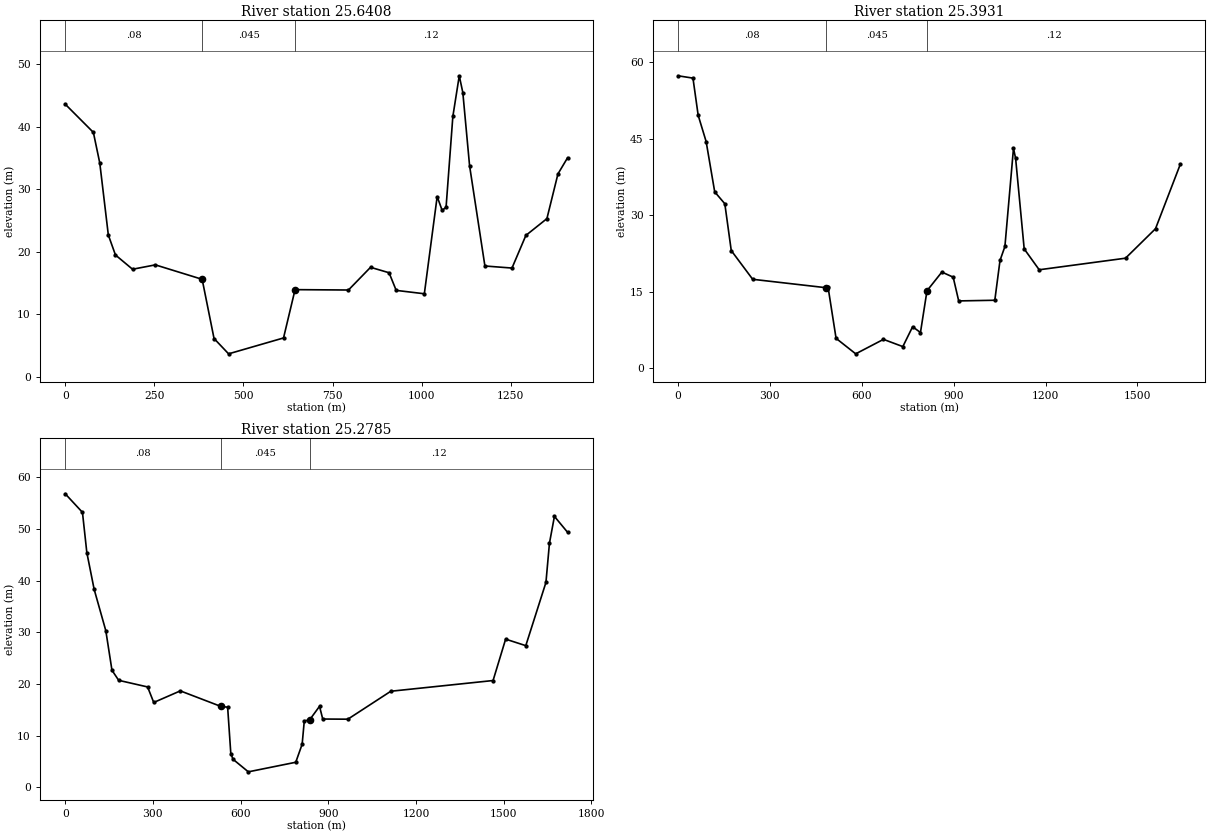
Type RM Length L Ch R = 1 ,25.6408 ,257.43,247.69,261.1
BEGIN DESCRIPTION:
Doves Ln - R28 (RIS 2013)
END DESCRIPTION:
XS GIS Cut Line= 2
609873.9750035985429831.75668309610403.7701035985428525.84358309
#Sta/Elev= 30
       0   43.59   78.96   39.08   96.95   34.18  120.94   22.67  140.93   19.48
   188.9    17.2  252.87    17.9  384.16   15.59  417.51   6.126  458.32   3.676
  612.44   6.216   644.8   13.94   794.6   13.88  856.57   17.51  908.54   16.64
  928.53   13.82 1007.49   13.28 1043.47   28.82 1057.47   26.61 1068.46   27.12
 1087.45   41.62 1105.44   48.13 1115.44   45.45 1134.43   33.73  1177.4   17.72
 1253.37   17.39 1292.35   22.61 1351.32   25.29  1382.3   32.44 1409.29   35.02
#Mann= 3 , 0 , 0
       0     .08       0  384.16    .045       0   644.8     .12       0
Bank Sta=384.16,644.8
XS Rating Curve= 0 ,0
Exp/Cntr=0.3,0.1

Type RM Length L Ch R = 1 ,25.3931 ,120.13,114.65,111.21
BEGIN DESCRIPTION:
Cannings Ln - R28A (SEM 2019)
END DESCRIPTION:
XS GIS Cut Line= 4
610050.0674035995430010.72108309610257.7009035985429570.22728309
610361.8800035995429255.41998309610594.2340035985428467.55488309
#Sta/Elev= 30
       0   57.38      49   56.92      66   49.63      92   44.48  119.99   34.61
  152.99   32.28  173.99    23.1  243.99   17.46  483.55   15.81  489.97   15.95
  516.19    5.88  580.28    2.84  670.94    5.68  734.13    4.26  766.11    8.16
   791.7    7.02     813   15.21  861.55   18.88  898.52   17.88  916.51   13.22
 1034.42   13.35 1051.41   21.16  1067.4    23.9 1095.38   43.15 1102.37   41.17
 1130.35   23.42 1179.31   19.33 1461.11    21.6 1559.03   27.38 1639.97   40.02
#Mann= 3 , 0 , 0
       0     .08       0  483.55    .045       0     813     .12       0
Bank Sta=483.55,813
XS Rating Curve= 0 ,0
Exp/Cntr=0.3,0.1

Type RM Length L Ch R = 1 ,25.2785 ,20.11,17.77,18.26
BEGIN DESCRIPTION:
US of Bishop's Falls Trestle - R29-1 (RIS 2013)
END DESCRIPTION:
XS GIS Cut Line= 4
610144.2476035985430091.33098309610376.7635035985429596.68548309
610454.8157035985429320.19548309610673.6588035985428463.30998309
#Sta/Elev= 30
       0   56.76   58.95   53.17   73.94   45.39   98.92    38.3  138.89   30.29
  159.87   22.66  182.86   20.71  281.78   19.43  302.76   16.43  393.69   18.67
  532.79   15.66  555.55   15.52  566.38   6.565  573.94   5.455  626.34   3.025
   788.5   4.875  810.42   8.365  817.69  12.855  836.27   13.09  869.84   15.69
  880.83   13.23  966.77    13.2 1113.67    18.6 1463.43   20.67  1506.4   28.67
 1575.35   27.41  1644.3   39.63 1656.29   47.21 1673.28   52.39 1718.25   49.32
#Mann= 3 , 0 , 0
       0     .08       0  532.79    .045       0  836.27     .12       0
Bank Sta=532.79,836.27
XS Rating Curve= 0 ,0
Exp/Cntr=0.3,0.1

Type RM Length L Ch R = 3 ,25.262  ,,,
Node Photo=.\Photos\E-CR-2.JPG
BEGIN DESCRIPTION:
Bishop's Falls Trestle
END DESCRIPTION:
Node Name=E-CR-2
Bridge Culvert--1,0,-1,-1, 0
Deck Dist Width WeirC Skew NumUp NumDn MinLoCord MaxHiCord MaxSubmerge Is_Ogee
0.1,5,1.4,0, 250, 250, , , 0.98, 0, 3,3,,
     437 443.931 452.843 456.803 464.724 468.696 480.622 493.511 506.349 511.286
 517.211 520.174 522.149 525.112     528 531.801 535.603   540.5 542.498 544.496
 546.494 549.491 563.477 567.474  571.47 577.464 579.462 584.457 587.454  591.45
 593.448 599.442  601.44 606.435  611.43 616.425 637.404 642.399 645.396  651.39
 653.388 658.383 672.369 676.366 680.362 697.345 703.339 709.333 723.319 728.314
 741.301 747.295 758.284 764.278 774.268 775.267 801.242 809.234 810.233 814.229
 816.227 818.225  823.22 824.219 828.215 836.191 842.089 847.004 847.988 850.937
 852.903 855.852 861.813 863.804 867.786 872.764 874.755 879.733 883.716 887.694
 889.682 891.669 893.656 897.631 899.618 902.599  905.58 910.549 913.529 917.504
 919.491 932.409 938.337 940.313 949.205 956.121 968.964  970.94 982.796 987.736
  989.72 991.705 993.6891003.6111005.5961010.5571019.4871022.4641026.4321027.425
1031.3921032.3821034.3641037.3361043.2791048.2331052.1951055.1671059.1291063.092
1069.0361072.9981076.9611082.9041084.8861088.8481090.8291095.7821099.7451101.734
1106.7291109.7251116.7181119.7141122.7111124.7091126.7061127.7051135.6961137.694
1146.6841153.676 1158.671161.6671168.6591171.6561174.652 1176.651182.6431190.634
1193.6311195.6291198.6251201.6221205.6171207.6151209.613 1212.611213.6091217.604
1219.6021221.5991225.5951231.5881233.5861235.5841237.5811239.5791241.575 1247.56
1252.5471254.5421257.5341258.5321262.5211264.5161268.5061270.5011271.4981277.483
1281.473 1286.461288.4541291.4471294.4391297.4311300.4241306.408  1309.41310.398
1314.3871316.3821318.3771324.3621327.3541332.3411338.3261340.3211342.3151346.305
1350.2951354.2851358.2741359.2721363.2611366.2541370.2431372.2381374.2331376.228
1382.2131384.2071386.2021388.1971390.1921396.1771398.1711401.1641403.1581404.156
 1410.141415.1271417.1221419.1171421.1121423.1071427.102  1429.11431.0971434.094
1436.0921438.0891441.086 1446.081449.0761451.0741453.0711458.0651459.0641461.062
1463.0591465.0571467.0551470.0511474.0461481.0381483.0361485.033 1488.031490.027
 18.6041 18.6739 18.9704 19.2303 19.6415  19.726 19.8477 19.8462 19.7893 19.6917
 19.6919 19.6141 19.8989 19.8206    20.3    20.3    20.3    20.3    20.3    20.3
    20.3    20.3    20.3    20.3    20.3    20.3    20.3    20.3    20.3    20.3
    20.3    20.3    20.3    20.3    20.3    20.3    20.3    20.3    20.3    20.3
    20.3    20.3    20.3    20.3    20.3    20.3    20.3    20.3    20.3    20.3
    20.3    20.3    20.3    20.3    20.3    20.3    20.3    20.3    20.3    20.3
    20.3    20.3    20.3 19.8705 19.4745 18.9711 18.4814 18.3796  18.467 17.9516
 18.6274 18.8158 18.2364 18.3114 18.7706 18.7818 18.9955 18.8815 19.3398 19.3649
 18.9451 18.8329 19.0207 19.1171 19.0663 19.2799 19.0733 19.1196 18.9966 19.5074
 19.1793 19.1011 19.0097 19.0772 19.1248 19.1081 18.9111 18.9774 18.7805 18.5617
 18.6627 18.5308 18.6749 18.5336 18.4207 18.5024 18.4061 18.5598 18.5282 18.3851
 18.5829 18.0117 17.2873 16.9914 16.9743  16.666 17.0368  16.767 16.7478 16.5443
 16.6718 16.8367 16.7872 17.0334 16.9612 17.1091 17.0229  17.018 17.3159 17.0578
 17.0874 17.2507  17.387 17.6402 17.4309 17.5908 17.5024 17.7007 17.8167  17.711
 17.8656 18.2014 18.1233 18.4307 18.4936 18.4116 18.4877 18.3802 18.5532 18.5282
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                                   19.16   19.16   19.16   19.16   19.16   19.16
   19.16   19.16   19.16   19.16   19.16   19.16   19.16   19.16   19.16   19.16
   19.16   19.16   19.16   19.16   19.16   19.16   19.16   19.16   19.16   19.16
   19.16   19.16   19.16   19.16   19.16   19.16   19.16   19.16   19.16   19.16
   19.16   19.16   19.16   19.16   19.16   19.16   19.16   19.16   19.16   19.16
   19.16   19.16   19.16
     350 356.931 365.843 369.803 377.724 381.696 393.622 406.511 419.349 424.286
 430.211 433.174 435.149 438.112     441 444.801 448.603   453.5 455.498 457.496
 459.494 462.491 476.477 480.474  484.47 490.464 492.462 497.457 500.454  504.45
 506.448 512.442  514.44 519.435  524.43 529.425 550.404 555.399 558.396  564.39
 566.388 571.383 585.369 589.366 593.362 610.345 616.339 622.333 636.319 641.314
 654.301 660.295 671.284 677.278 687.268 688.267 714.242 722.234 723.233 727.229
 729.227 731.225  736.22 737.219 741.215 749.191 755.089 760.004 760.988 763.937
 765.903 768.852 774.813 776.804 780.786 785.764 787.755 792.733 796.716 800.694
 802.682 804.669 806.656 810.631 812.618 815.599  818.58 823.549 826.529 830.504
 832.491 845.409 851.337 853.313 862.205 869.121 881.964  883.94 895.796 900.736
  902.72 904.705 906.689 916.611 918.596 923.557 932.487 935.464 939.432 940.425
 944.392 945.383 947.364 950.336 956.279 961.233 965.195 968.167 972.129 976.092
 982.036 985.998 989.961 995.904 997.8861001.8481003.8291008.7821012.7451014.734
1019.7291022.7261029.7181032.7141035.7111037.7091039.7061040.7051048.6961050.694
1059.6841066.676 1071.671074.6671081.6591084.6561087.652 1089.651095.6431103.634
1106.6311108.6291111.6251114.6221118.6171120.6151122.613 1125.611126.6091130.604
1132.6021134.5991138.5951144.5881146.5861148.5841150.5811152.5791154.575 1160.56
1165.5471167.5421170.5341171.5321175.5211177.5161181.5061183.5011184.4981190.483
1194.473 1199.461201.4541204.4471207.4391210.4311213.4241219.408  1222.41223.398
1227.3871229.3821231.3771237.3621240.3541245.3411251.3261253.3211255.3151259.305
1263.2951267.2851271.2741272.2721276.2611279.2541283.2431285.2381287.2331289.228
1295.2131297.2071299.2021301.1971303.1921309.1771311.1711314.1641316.1581317.156
 1323.141328.1271330.1221332.1171334.1121336.1071340.102  1342.11344.0971347.094
1349.0921351.0891354.086 1359.081362.0761364.0741366.0711371.0651372.0641374.062
1376.0591378.0571380.0551383.0511387.0461394.0381396.0361398.033 1401.031403.027
 18.6041 18.6739 18.9704 19.2303 19.6415  19.726 19.8477 19.8462 19.7893 19.6917
 19.6919 19.6141 19.8989 19.8206    20.3    20.3    20.3    20.3    20.3    20.3
    20.3    20.3    20.3    20.3    20.3    20.3    20.3    20.3    20.3    20.3
    20.3    20.3    20.3    20.3    20.3    20.3    20.3    20.3    20.3    20.3
    20.3    20.3    20.3    20.3    20.3    20.3    20.3    20.3    20.3    20.3
    20.3    20.3    20.3    20.3    20.3    20.3    20.3    20.3    20.3    20.3
    20.3    20.3    20.3 19.8705 19.4745 18.9711 18.4814 18.3796  18.467 17.9516
 18.6274 18.8158 18.2364 18.3114 18.7706 18.7818 18.9955 18.8815 19.3398 19.3649
 18.9451 18.8329 19.0207 19.1171 19.0663 19.2799 19.0733 19.1196 18.9966 19.5074
 19.1793 19.1011 19.0097 19.0772 19.1248 19.1081 18.9111 18.9774 18.7805 18.5617
 18.6627 18.5308 18.6749 18.5336 18.4207 18.5024 18.4061 18.5598 18.5282 18.3851
 18.5829 18.0117 17.2873 16.9914 16.9743  16.666 17.0368  16.767 16.7478 16.5443
 16.6718 16.8367 16.7872 17.0334 16.9612 17.1091 17.0229  17.018 17.3159 17.0578
 17.0874 17.2507  17.387 17.6402 17.4309 17.5908 17.5024 17.7007 17.8167  17.711
 17.8656 18.2014 18.1233 18.4307 18.4936 18.4116 18.4877 18.3802 18.5532 18.5282
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                                   19.16   19.16   19.16   19.16   19.16   19.16
   19.16   19.16   19.16   19.16   19.16   19.16   19.16   19.16   19.16   19.16
   19.16   19.16   19.16   19.16   19.16   19.16   19.16   19.16   19.16   19.16
   19.16   19.16   19.16   19.16   19.16   19.16   19.16   19.16   19.16   19.16
   19.16   19.16   19.16   19.16   19.16   19.16   19.16   19.16   19.16   19.16
   19.16   19.16   19.16
Pier Skew, UpSta & Num, DnSta & Num=  ,615, 2 ,506.25, 2 , 0 , 0 , 0 ,,
       4       4
       0    19.7
       4       4
       0    19.7
Pier Skew, UpSta & Num, DnSta & Num=  ,685, 2 ,587.5, 2 , 0 , 0 , 0 ,,
       4       4
       0    19.7
       4       4
       0    19.7
Pier Skew, UpSta & Num, DnSta & Num=  ,755, 2 ,668.75, 2 , 0 , 0 , 0 ,,
       4       4
       0    19.7
       4       4
       0    19.7
BR Coef=-1 , 0 , 0 ,, 0 ,,,0.8,-1,,0,
WSPro=,,,, 1 ,,,, 0 ,,,, 0 ,,,,-1 ,-1 ,-1 , 0 , 0 , 0 , 0 , 0
BC Design=,, 0 ,, 0 ,,,,,,
BC HTab HWMax=30
BC Use User HTab Curves=0
BC User HTab FreeFlow(D)= 0

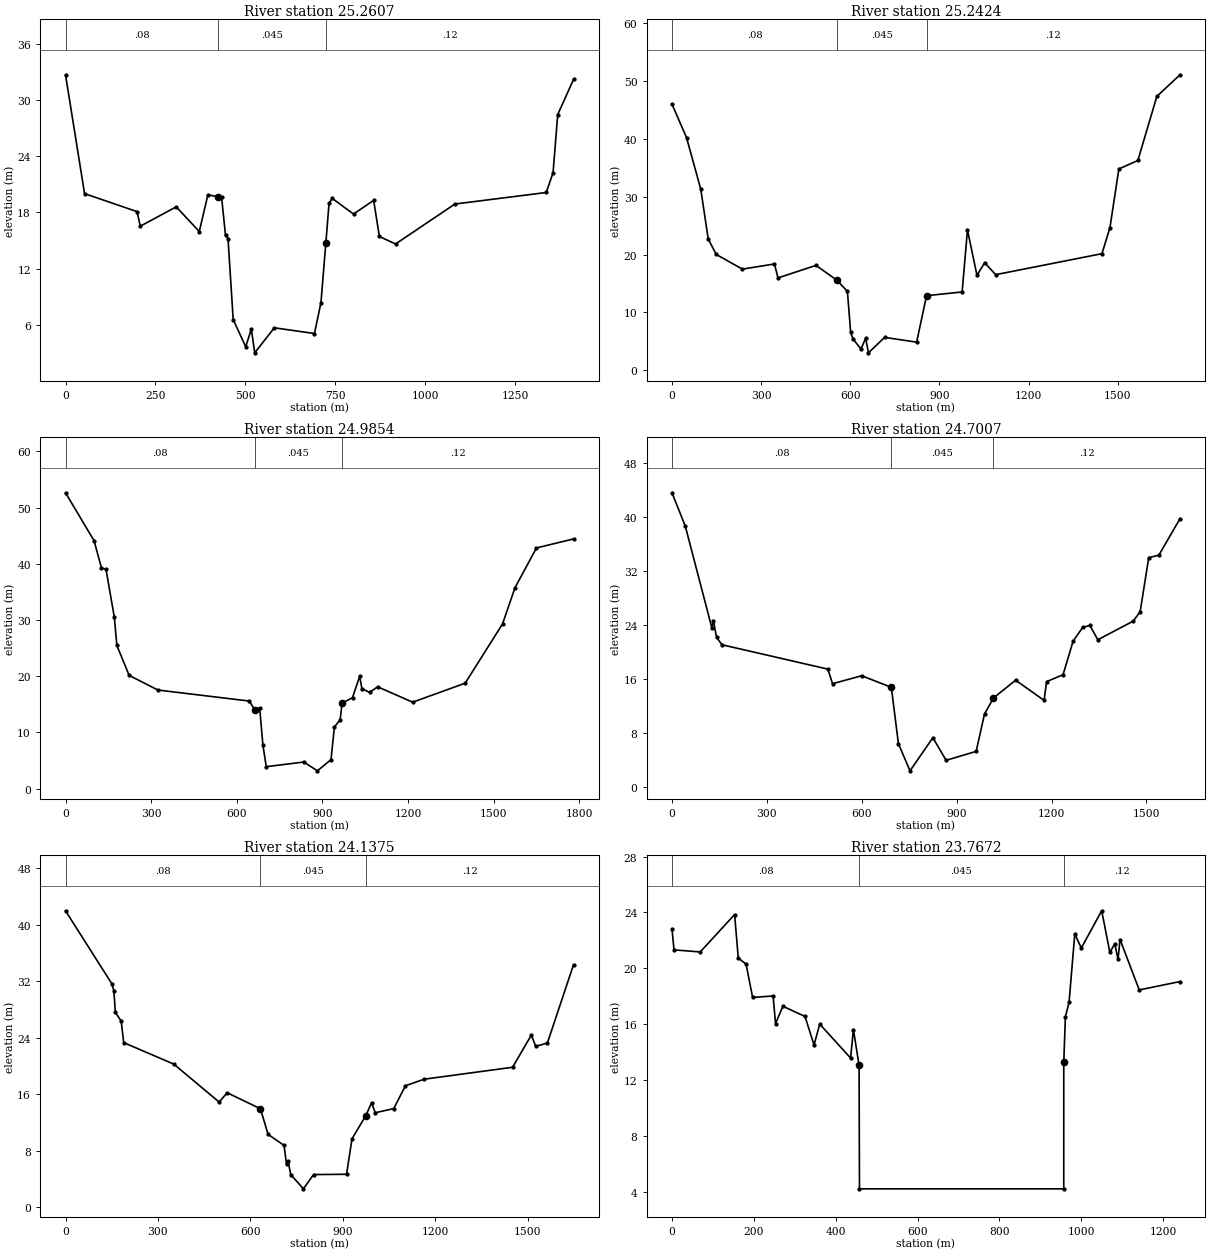
Type RM Length L Ch R = 1 ,25.2607 ,18.92,18.24,21.96
BEGIN DESCRIPTION:
DS of Bishop's Falls Trestle - R29-2 (RIS 2013)
END DESCRIPTION:
XS GIS Cut Line= 2
610274.9696035985430023.95548309610657.9911035985428663.86218309
#Sta/Elev= 30
       0   32.67      53      20     199   18.08     208   16.53     308   18.59
     372   15.96     396   19.86   424.7   19.68     434   19.66     445   15.55
     452   15.19  466.38   6.565   501.2   3.675  516.82   5.555  526.34   3.025
  580.65   5.695  692.35   5.085  710.42   8.365  724.14   14.78     733   18.97
     742   19.49     801   17.82     857   19.28     873   15.43     918   14.63
    1083   18.89 1336.99   20.12 1355.99   22.22 1368.99   28.43 1412.99   32.18
#Mann= 3 , 0 , 0
       0     .08       0   424.7    .045       0  724.14     .12       0
Bank Sta=424.7,724.14
XS Rating Curve= 0 ,0
Exp/Cntr=0.3,0.1

Type RM Length L Ch R = 1 ,25.2424 ,246.1,257.07,267.74
BEGIN DESCRIPTION:
NLENHM0003 ER at Bishop's Falls Trestle
END DESCRIPTION:
XS GIS Cut Line= 4
610354.8152035985430173.47438309610409.8365035985429603.30008309
610491.8574035985429329.45598309610797.9386035995428535.14458309
#Sta/Elev= 30
       0   46.03   48.98   40.24   96.97   31.31  121.96   22.73  148.95   20.04
  236.93    17.5  344.89   18.39  356.89   15.98  484.85   18.15  555.25   15.57
  590.54  13.645  601.38   6.565  608.94   5.455   636.2   3.675  651.82   5.555
  661.34   3.025  715.65   5.695   823.5   4.875  856.84   12.91  976.58   13.55
  994.56   24.28 1026.53   16.43 1052.51   18.61 1089.48   16.54 1447.17   20.17
 1474.15   24.69 1504.12   34.82 1568.06   36.28 1632.01   47.37 1709.94    51.1
#Mann= 3 , 0 , 0
       0     .08       0  555.25    .045       0  856.84     .12       0
Bank Sta=555.25,856.84
XS Rating Curve= 0 ,0
Exp/Cntr=0.3,0.1

Type RM Length L Ch R = 1 ,24.9854 ,281.37,284.66,290.76
BEGIN DESCRIPTION:
Kinsmen Dr - R29-2A (SEM 2019)
END DESCRIPTION:
XS GIS Cut Line= 4
610422.5005035985430323.93238309610645.3163035985429687.96708309
610741.2790035985429414.51798309611010.8034035985428643.77428309
#Sta/Elev= 30
       0   52.65   99.98   44.13  125.98   39.29  141.97   39.01  170.97   30.54
  179.96   25.48  222.96   20.15  323.94   17.54  643.88   15.58  663.45      14
  680.29   14.38  691.65    7.75  703.53     3.9  835.07    4.73  882.72    3.16
   930.4    5.16  942.07   10.96  962.42   12.26  969.07   15.19 1005.64   16.19
 1030.62   19.97 1038.62   17.79  1065.6   17.12 1093.59   18.12 1216.51   15.38
 1400.39   18.76 1531.31   29.31 1575.28   35.79 1650.23   42.83 1780.15   44.44
#Mann= 3 , 0 , 0
       0     .08       0  663.45    .045       0  969.07     .12       0
Bank Sta=663.45,969.07
XS Rating Curve= 0 ,0
Exp/Cntr=0.3,0.1

Type RM Length L Ch R = 1 ,24.7007 ,537.64,563.23,612.52
BEGIN DESCRIPTION:
Riverside Dr - R30 (RIS 2013)
END DESCRIPTION:
XS GIS Cut Line= 3
610614.6886035995430404.38208309610744.1562035985430215.60338309
611235.2131035985428928.88678309
#Sta/Elev= 30
       0   43.58   41.98   38.66  125.95    23.6  130.95   24.65  140.94   22.17
  157.94   21.07  492.76   17.46  507.75    15.3   599.7   16.48   693.5   14.76
  715.93   6.414  752.57   2.394   824.8   7.304  866.69   3.954  961.67   5.274
  988.07  10.814 1016.27   13.18 1086.43   15.82 1176.38   12.83 1184.38   15.61
 1236.35   16.63 1268.33   21.62 1298.32   23.63  1321.3   23.93 1346.29   21.81
 1458.23   24.57 1480.22   25.97  1507.2   33.97 1539.19   34.34 1606.15   39.74
#Mann= 3 , 0 , 0
       0     .08       0   693.5    .045       0 1016.27     .12       0
Bank Sta=693.5,1016.27
XS Rating Curve= 0 ,0
Exp/Cntr=0.3,0.1

Type RM Length L Ch R = 1 ,24.1375 ,197.35,370.28,378.31
BEGIN DESCRIPTION:
Sydney St - R31 (RIS 2013)
END DESCRIPTION:
XS GIS Cut Line= 2
610988.3413035985430637.88788309611880.7428035985429250.63758309
#Sta/Elev= 30
       0   42.01  149.95   31.71  156.95   30.71  161.95   27.62  180.94   26.37
  188.94   23.34  351.89   20.29  498.85   14.92  524.84   16.24  632.99  13.973
  657.79  10.343  709.65   8.783  717.56   6.103  722.78   6.583  731.11   4.663
  772.46   2.633  805.33   4.653  912.48   4.693  930.23   9.723   975.2  13.013
   993.7   14.82  1005.7   13.41 1065.68      14 1103.67   17.23 1164.65   18.16
 1451.56   19.85 1512.55   24.41 1526.54   22.81 1564.53   23.28  1649.5   34.38
#Mann= 3 , 0 , 0
       0     .08       0  632.99    .045       0   975.2     .12       0
Bank Sta=632.99,975.2
XS Rating Curve= 0 ,0
Exp/Cntr=0.3,0.1

Type RM Length L Ch R = 1 ,23.7672 ,284.19,49.69,32.96
BEGIN DESCRIPTION:
US of Bishop's Falls Dam
END DESCRIPTION:
XS GIS Cut Line= 6
  611243.3111036 5430632.4161831  611439.1032036 5430269.9362831
  611558.4305036 5430222.8402831  611727.4996036 5430231.5715831
  611723.5308036 5430179.9777831  611918.3175036 5429745.2664831
#Sta/Elev= 30
       0   22.83       5   21.32      69   21.17  152.99   23.85  161.99   20.73
  180.99    20.3  196.99   17.91  246.99   18.02  252.99   16.04  270.99   17.28
  324.98   16.55  346.98   14.51  360.98      16  436.34   13.57  443.16   15.61
  457.03   13.05     458     4.2     957     4.2  957.02   13.26     961   16.53
  969.96   17.56  983.91   22.46  999.85   21.45 1049.67   24.12 1069.59   21.14
 1081.55   21.75 1089.52   20.65  1094.5   22.06 1141.33   18.45 1240.97   19.05
#Mann= 3 , 0 , 0
       0     .08       0  457.03    .045       0  957.02     .12       0
Bank Sta=457.03,957.02
XS Rating Curve= 0 ,0
Exp/Cntr=0.3,0.1

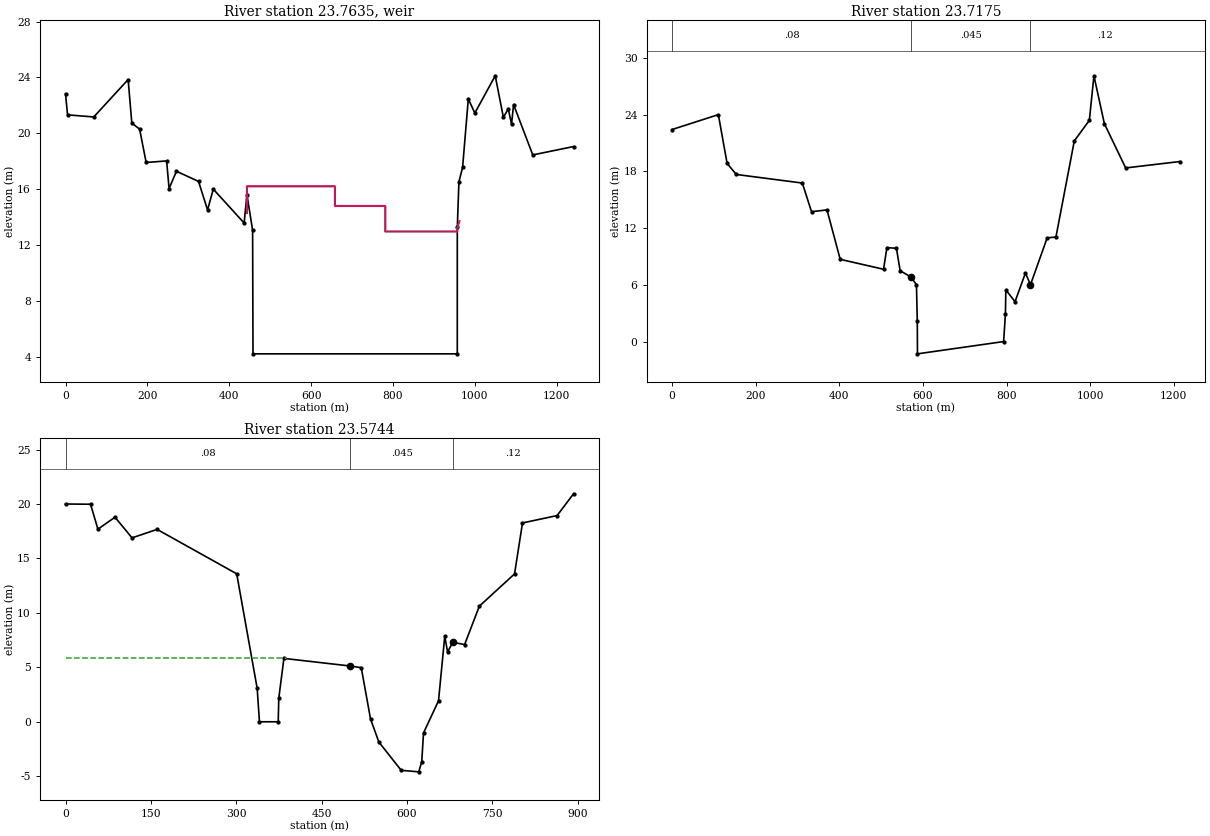
Type RM Length L Ch R = 5 ,23.7635 ,,,
Node Photo=.\Photos\Bishops Falls Dam.JPG
BEGIN DESCRIPTION:
Bishop's Falls Dam
END DESCRIPTION:
Node Name=BF Dam
IW Pilot Flow=0
#Inline Weir SE= 11
  443.16  14.282  443.16  16.202     658  16.202     658  14.792     706  14.792
     706  14.792     781  14.792     781  12.962   956.9  12.962   957.3  13.229
   962.1  13.702
IW Dist,WD,Coef,Skew,MaxSub,Min_El,Is_Ogee,SpillHt,DesHd
10,10,1.8,0,0.98,, 0 ,,,3,3,
IW Gate Name Wd,H,Inv,GCoef,Exp_T,Exp_O,Exp_H,Type,WCoef,Is_Ogee,SpillHt,DesHd,#Openings
BF Gates    ,5.5,4.328,4.577,0.555,0,1,0.5, 0 ,1.45, 0 ,,, 9 ,0,0.8, 0 ,0.555,,0,0,0, 0
     720     727     734     741     748     755     762     769     776
IW Gate Opening=1,BFG02,0
IW Gate Opening=2,BFG03,0
IW Gate Opening=3,BFG04,0
IW Gate Opening=4,BFG05,0
IW Gate Opening=5,BFG06,0
IW Gate Opening=6,BFG07,0
IW Gate Opening=7,BFG08,0
IW Gate Opening=8,BFG09,0
IW Gate Opening=9,BFG10,0
IW Gate Name Wd,H,Inv,GCoef,Exp_T,Exp_O,Exp_H,Type,WCoef,Is_Ogee,SpillHt,DesHd,#Openings
BF Fboards  ,175.9,1.22,11.742,,0,1,0.5, 3 ,1.8, 0 ,,, 1 ,0,0.8, 0 ,,,0,0,0, 0
  868.95
IW Gate Opening=1,BFFB,0
Inline Weir Flap Gates= 0
IW Outlet Rating Curve= 0 ,True,690,1
IW OutletRC Name=BF Power

Type RM Length L Ch R = 1 ,23.7175 ,53.31,71.56,87.51
BEGIN DESCRIPTION:
DS of Bishop's Falls Dam
END DESCRIPTION:
XS GIS Cut Line= 6
  611313.4258036 5430662.8432831  611552.8742036 5430314.9154831
  611671.9370036 5430333.4363831  611773.8017036 5430289.7800831
  611777.7549036 5430182.9476831  611940.4896036 5429761.9352831
#Sta/Elev= 30
       0   22.43  110.89   24.01  131.87   18.84  153.85   17.68   311.7   16.77
  333.68   13.74  370.65   13.93  402.27     8.7  505.94    7.65  513.88    9.94
   536.7    9.87  545.63    7.49  571.59    6.83  584.57    6.02  586.57    2.17
     587  -1.298     793       0  797.31    2.93   798.3    5.47  820.27    4.22
  845.22    7.26   857.2    6.01  897.13   10.97  918.09   11.06  962.02   21.23
  997.96    23.4 1008.94   28.12 1033.89   23.05 1084.84   18.37 1214.77   19.05
#Mann= 3 , 0 , 0
       0     .08       0  571.59    .045       0   857.2     .12       0
Bank Sta=571.59,857.2
XS Rating Curve= 0 ,0
Exp/Cntr=0.3,0.1

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
Type RM Length L Ch R = 1 ,23.5744 ,273.17,183.95,201.98
BEGIN DESCRIPTION:
Fallsview Park - RB01 (RIS 2012)
END DESCRIPTION:
XS GIS Cut Line= 3
  611532.4663036 5430784.4777831  611862.0448036 5430297.7895831
  611911.6487036 5429996.7166831
#Sta/Elev= 30
       0      20   43.98   19.98   56.98   17.69   86.97   18.79  116.96   16.89
  160.94   17.67  300.89   13.59  336.88    3.07  340.87       0  373.86       0
  374.86    2.17  383.86    5.82  500.76    5.12  519.81    4.97  536.13    .252
  550.71  -1.858     590  -4.458  620.86  -4.598  626.14  -3.658  629.24  -1.028
  655.59    1.93  666.56    7.86  671.55    6.41  680.56     7.3  701.46    7.09
  727.39   10.62  789.22   13.58  803.18   18.26  864.01   18.94  892.92   20.94
#Mann= 3 , 0 , 0
       0     .08       0  500.76    .045       0  680.56     .12       0
#XS Ineff= 2 , 0
             387    5.84
Permanent Ineff=
       T       F
Bank Sta=500.76,680.56
XS Rating Curve= 0 ,0
Exp/Cntr=0.3,0.1

River Reach=Exploits River  ,BF2 to BF1
Reach XY= 30
611946.6080034565430415.72603256     611958.5627    5430430.9212
      612065.398    5430514.8727     612147.4253    5430554.0507
     612229.6479    5430578.4125     612296.9983     5430606.818
     612368.6156    5430633.1598     612436.1334    5430648.8685
     612518.0493    5430696.5044     612652.5928    5430766.0124
     612743.1718    5430798.9537     612848.6127    5430827.8612
     612930.6401    5430867.0393     612991.2618    5430924.9839
     613078.9862    5431012.9135     613125.2099    5431038.9208
     613177.8657    5431058.6633     613243.1247    5431084.9214
     613316.8616    5431111.2913     613380.1506    5431126.9343
     613439.2664    5431138.3027     613515.3637    5431145.6551
     613619.0759    5431144.9022     613671.7875    5431160.4158
     613743.2376    5431199.4546     613938.3654    5431329.0169
     614110.2926     5431451.924     614330.4237    5431611.4438
     614487.6714    5431732.1277  614598.8519133  5431833.881883