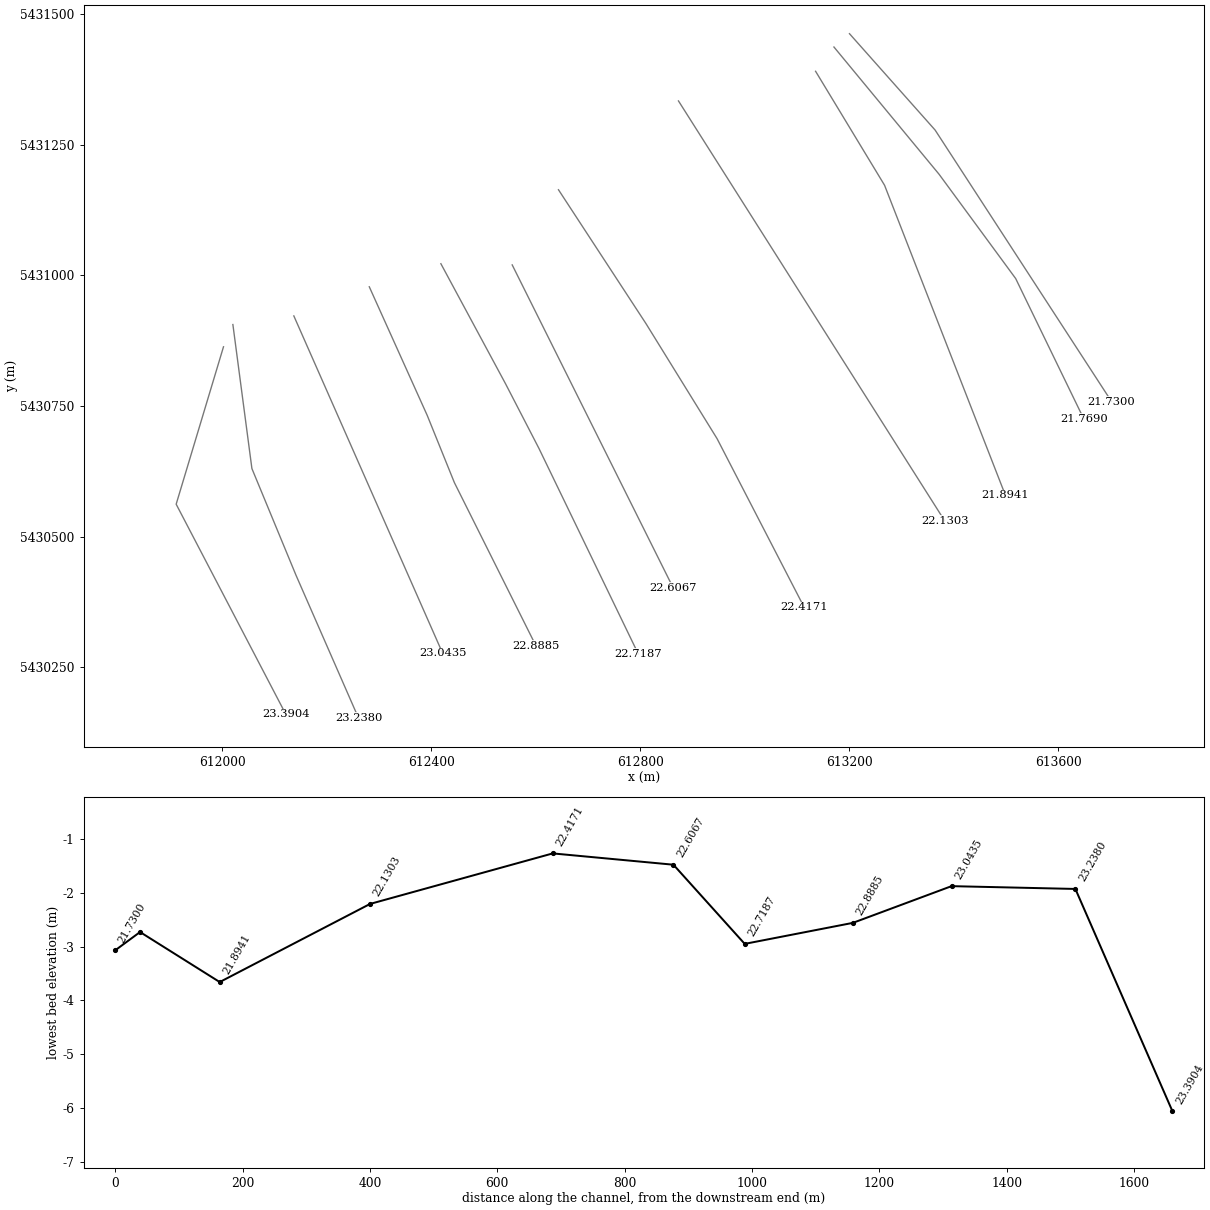
HEC-RAS study Exploits_FMM.prj: Exploits_FMM

--- Exploits_FMM.g01 (geometry) --- (continued)

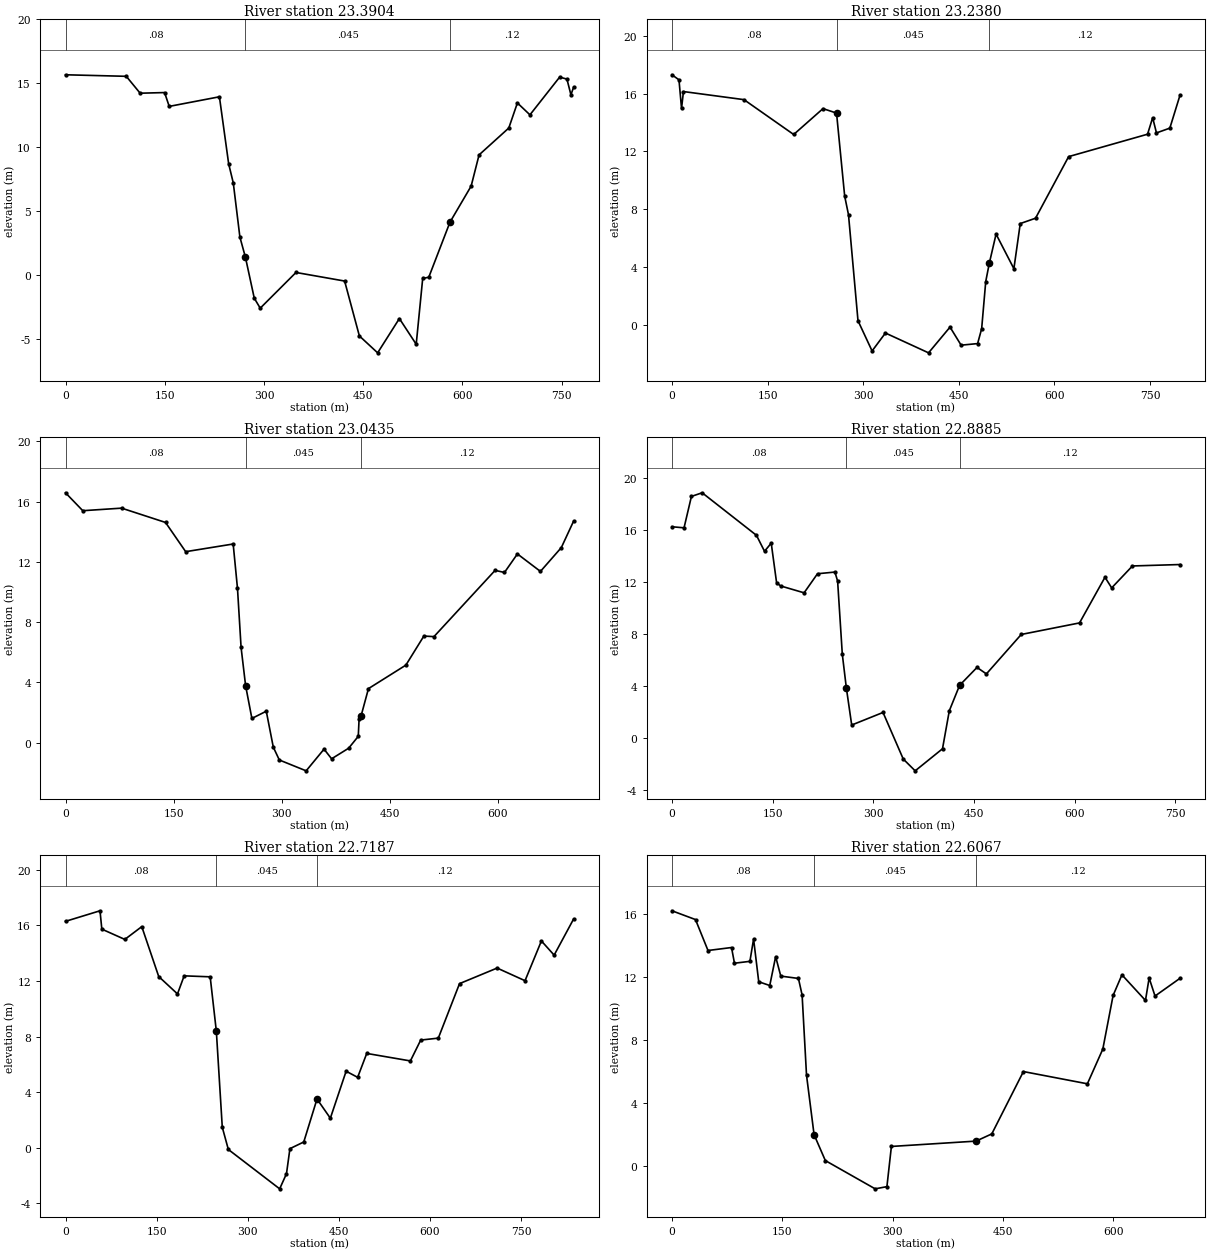
Type RM Length L Ch R = 1 ,23.3904 ,138.39,152.45,147.72
BEGIN DESCRIPTION:
RB02 (RIS 2012)
END DESCRIPTION:
XS GIS Cut Line= 3
612002.7701035985430863.30138309611912.2141035985430562.14938309
612121.9974035985430160.23608309
#Sta/Elev= 30
       0   15.67   91.85   15.55  112.81   14.23  149.75   14.28  156.74    13.2
  232.61   13.95  246.59    8.71  253.57    7.22  263.56    2.99  271.97     1.4
  285.29  -1.788   294.3  -2.568  348.34    .222  421.84   -.448  444.15  -4.738
  471.75  -6.058   504.6  -3.378  530.04  -5.388  539.85   -.248  549.06   -.148
  581.06    4.15  613.06    6.97  625.04    9.41  669.98   11.51  682.96   13.47
  701.93   12.54  746.87   15.49  757.86   15.33  763.85   14.11  767.84   14.68
#Mann= 3 , 0 , 0
       0     .08       0  271.97    .045       0  581.06     .12       0
Bank Sta=271.97,581.06
XS Rating Curve= 0 ,0
Exp/Cntr=0.3,0.1

Type RM Length L Ch R = 1 ,23.2380 ,188.98,194.52,204.76
BEGIN DESCRIPTION:
RB02A (SEM 2019)
END DESCRIPTION:
XS GIS Cut Line= 4
612020.7285035985430905.86818309612057.1210035985430630.34298309
612141.3590035985430426.56098309612261.0617035985430153.06188309
#Sta/Elev= 30
       0    17.3      11   16.95      15   14.97   17.99   16.14  112.97   15.58
  190.94   13.17  236.93   14.96  258.16   14.65  270.92    8.91  276.92    7.62
  291.82     .29  313.92    -1.8  334.86    -.56   402.5   -1.93  436.18    -.15
  453.59    -1.4  479.47   -1.29  485.81    -.26   492.2       3  497.72    4.25
  508.41    6.28  536.37    3.89  546.35    7.01  570.32    7.38  622.24   11.64
  746.05   13.19  754.04   14.33  760.03   13.28     781   13.61  796.97   15.89
#Mann= 3 , 0 , 0
       0     .08       0  258.16    .045       0  497.72     .12       0
Bank Sta=258.16,497.72
XS Rating Curve= 0 ,0
Exp/Cntr=0.3,0.1

Type RM Length L Ch R = 1 ,23.0435 ,158.58,154.99,157.25
BEGIN DESCRIPTION:
RB03 (RIS 2012)
END DESCRIPTION:
XS GIS Cut Line= 2
612137.3516035985430922.37948309612422.0569035985430276.89158309
#Sta/Elev= 30
       0   16.58   23.98   15.39   77.94   15.56   138.9   14.61  166.88   12.67
  232.83   13.18  238.83   10.23  243.82    6.31  250.08    3.78  258.81     1.6
   278.8    2.08  288.56   -.308  296.93  -1.158  334.17  -1.878  358.99   -.438
  369.53  -1.078  393.13   -.378  406.55    .412   407.7    1.58   410.4    1.76
  420.69    3.58  472.66    5.14  497.64    7.07  511.63    7.03  596.57   11.43
  609.56   11.29  627.54   12.52  659.52   11.36   688.5   12.94  705.49   14.69
#Mann= 3 , 0 , 0
       0     .08       0  250.08    .045       0   410.4     .12       0
Bank Sta=250.08,410.4
XS Rating Curve= 0 ,0
Exp/Cntr=0.3,0.1

Type RM Length L Ch R = 1 ,22.8885 ,160.64,169.83,174.21
BEGIN DESCRIPTION:
RB03A (SEM 2019)
END DESCRIPTION:
XS GIS Cut Line= 4
612281.6944035985430978.09398309612392.5191035985430732.10658309
612444.5200035985430603.41298309612600.2783035985430291.78168309
#Sta/Elev= 30
       0   16.25   17.99   16.17   28.98   18.59   44.97   18.87  125.91   15.59
   137.9   14.36  147.89   14.99  155.88   11.94  161.88   11.69  196.85   11.16
  216.84   12.63  242.82   12.76  246.82   12.06  253.81    6.42  259.82    3.83
   267.8     .97  314.47    1.94  344.61   -1.65  362.37   -2.56  403.09    -.86
  413.24    2.07  428.57    4.03  454.52    5.41   468.5    4.91  520.41    7.95
  607.26    8.84  645.19   12.36  655.17   11.54  686.12   13.23  756.99   13.34
#Mann= 3 , 0 , 0
       0     .08       0  259.82    .045       0  428.57     .12       0
Bank Sta=259.82,428.57
XS Rating Curve= 0 ,0
Exp/Cntr=0.3,0.1

Type RM Length L Ch R = 1 ,22.7187 ,113.52,111.97,142.35
BEGIN DESCRIPTION:
RB03B (SEM 2019)
END DESCRIPTION:
XS GIS Cut Line= 4
612418.6857035985431022.22958309612542.5272035985430792.28738309
612606.3272035985430668.78338309612796.2655035985430275.84498309
#Sta/Elev= 30
       0   16.29   56.82   17.05   59.81   15.73   97.69   14.99   125.6   15.91
  153.51   12.32  184.41   11.07  195.38   12.37  238.24    12.3  248.41    8.38
  258.17    1.48  268.16    -.12  352.67   -2.95  363.91   -1.86  369.56    -.06
  392.35     .42  414.16    3.51  436.13    2.13   462.1    5.51  481.08    5.07
  496.06    6.79  567.96    6.25  584.94    7.75  613.91    7.89  648.86   11.81
  710.78   12.93  756.72   12.02  783.69   14.88  804.66   13.86  836.62   16.45
#Mann= 3 , 0 , 0
       0     .08       0  248.41    .045       0  414.16     .12       0
Bank Sta=248.41,414.16
XS Rating Curve= 0 ,0
Exp/Cntr=0.3,0.1

Type RM Length L Ch R = 1 ,22.6067 ,178.5,189.54,215.43
BEGIN DESCRIPTION:
RB04 (RIS 2012)
END DESCRIPTION:
XS GIS Cut Line= 2
612555.1334035985431019.94838309612863.2975035985430401.75718309
#Sta/Elev= 30
       0   16.23   31.99   15.67   48.98    13.7   80.97   13.89   84.97   12.89
  105.96   13.01  110.96   14.43  117.96   11.71  132.95   11.47  140.95   13.31
  147.94   12.07  171.94   11.92  176.93   10.87  182.93    5.76  193.21    1.97
  208.52     .32  276.26   -1.48  292.24   -1.34  298.33    1.22  413.47    1.56
  434.84    2.02  477.82    5.99  564.79    5.21  585.78    7.42  599.78   10.84
  611.77   12.15  643.76   10.52  648.76   11.95  656.76    10.8  690.74   11.93
#Mann= 3 , 0 , 0
       0     .08       0  193.21    .045       0  413.47     .12       0
Bank Sta=193.21,413.47
XS Rating Curve= 0 ,0
Exp/Cntr=0.3,0.1

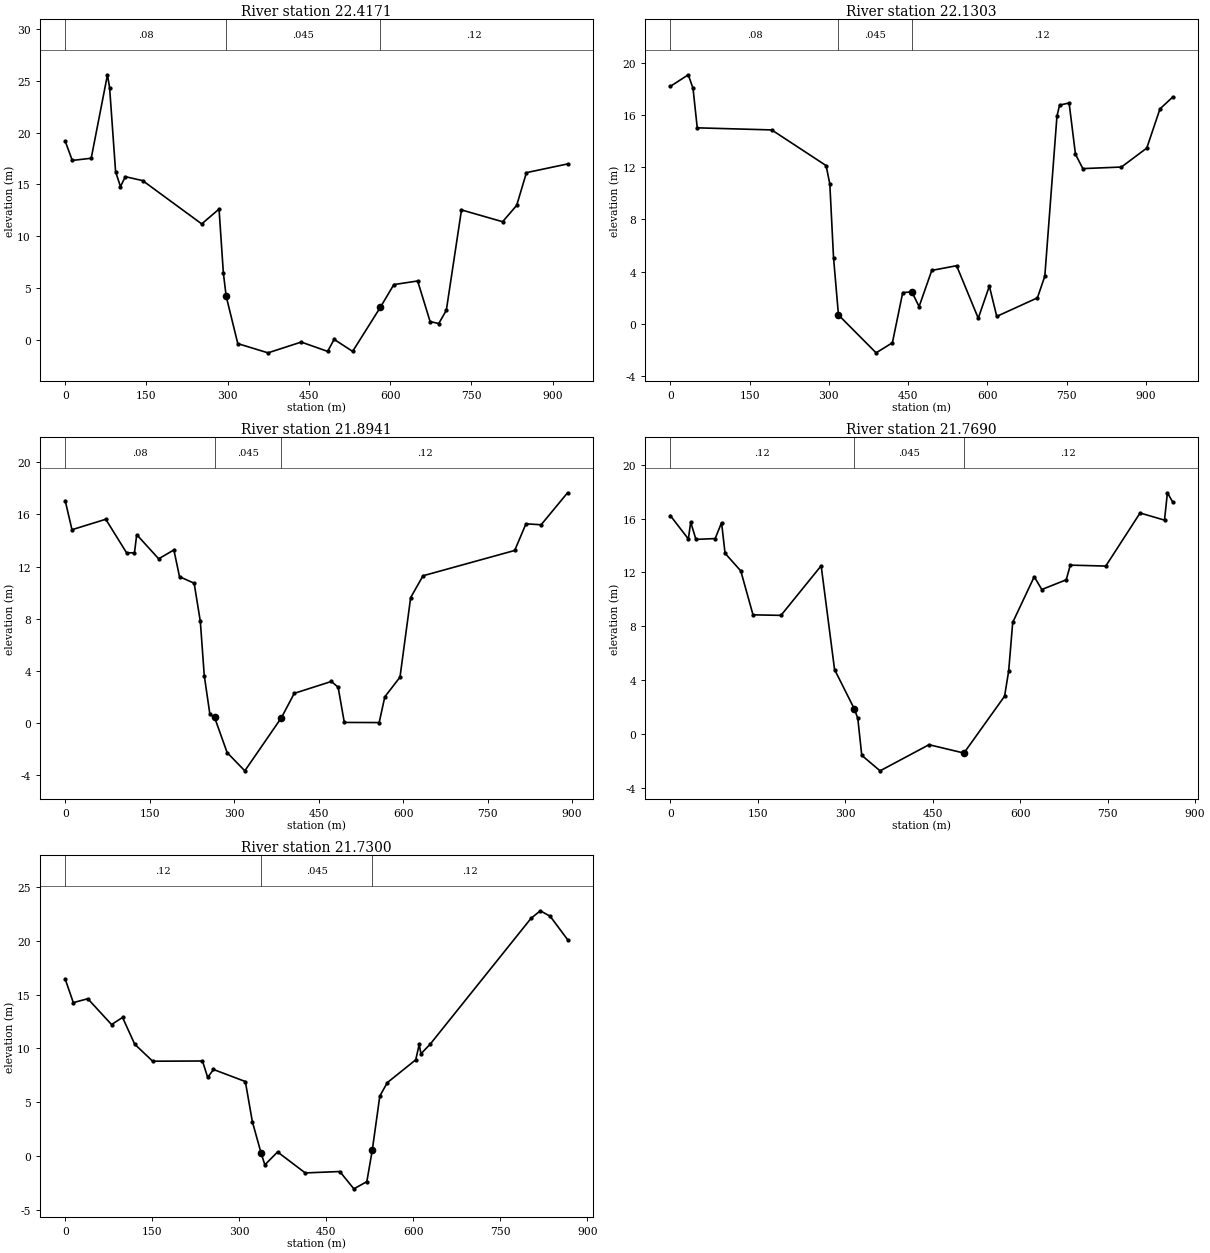
Type RM Length L Ch R = 1 ,22.4171 ,289.91,286.85,309.42
BEGIN DESCRIPTION:
RB04A (SEM 2019)
END DESCRIPTION:
XS GIS Cut Line= 4
612643.6500035985431163.77218309612811.0750035985430907.63798309
612947.0970035985430687.52098309613113.5509035985430365.25808309
#Sta/Elev= 30
       0   19.17      13   17.31      48   17.52      78   25.58      82   24.31
      93   16.22     102   14.78     111   15.74     143   15.36     252   11.18
     284   12.61     292    6.42  297.19    4.19  318.61    -.38  374.38   -1.27
  435.76    -.23  484.46   -1.13  496.51     .03  530.61   -1.13  581.74    3.12
  606.72    5.32  650.69    5.67  673.67    1.75  689.66    1.56  703.64    2.84
  731.62   12.53  807.56   11.39  833.54   12.97  851.53   16.13  927.47   16.97
#Mann= 3 , 0 , 0
       0     .08       0  297.19    .045       0  581.74     .12       0
Bank Sta=297.19,581.74
XS Rating Curve= 0 ,0
Exp/Cntr=0.3,0.1

Type RM Length L Ch R = 1 ,22.1303 ,249.37,236.19,233.26
BEGIN DESCRIPTION:
RB05 (RIS 2012)
END DESCRIPTION:
XS GIS Cut Line= 2
612873.2338035985431333.68718309613382.2572035995430530.82688309
#Sta/Elev= 30
       0   18.18   33.99   19.07   42.98   18.03   50.98   15.01  191.92   14.85
  294.88   12.12  301.88    10.7  308.88    5.08  318.22     .69  389.45  -2.208
  420.27  -1.438  439.83     2.4  457.07    2.46  470.81    1.33   494.8     4.1
  541.78    4.46  582.77     .44  603.76     2.9  617.76     .58  694.73       2
  708.72    3.66  731.71   15.91  736.71   16.75   754.7   16.91   766.7   12.99
  780.69   11.89  853.67   12.01  901.65   13.46  926.64   16.46  950.63   17.36
#Mann= 3 , 0 , 0
       0     .08       0  318.22    .045       0  457.07     .12       0
Bank Sta=318.22,457.07
XS Rating Curve= 0 ,0
Exp/Cntr=0.3,0.1

Type RM Length L Ch R = 1 ,21.8941 ,105.81,125.11,172.27
BEGIN DESCRIPTION:
RB06 (RIS 2012)
END DESCRIPTION:
XS GIS Cut Line= 3
613135.5643035985431390.40198309613267.5307035995431172.33648309
613498.9161035995430578.80078309
#Sta/Elev= 30
       0   17.04   11.99   14.82   71.97   15.62  108.95   13.05  122.95   13.05
  126.94   14.44  165.93   12.59  192.92   13.27  202.91   11.22   228.9   10.72
  239.89    7.79  246.89    3.63  256.88     .67  265.21     .43  287.46  -2.259
  318.87  -3.659  383.95     .42  406.66    2.28  472.56    3.19  484.54    2.75
  495.53     .05  557.43     .04  567.42    2.01  594.38    3.52  613.35    9.62
  635.31   11.29  798.07   13.23  818.04   15.27     845    15.2  891.92   17.65
#Mann= 3 , 0 , 0
       0     .08       0  265.21    .045       0  383.95     .12       0
Bank Sta=265.21,383.95
XS Rating Curve= 0 ,0
Exp/Cntr=0.3,0.1

Type RM Length L Ch R = 1 ,21.7690 ,43,38.95,32.98
BEGIN DESCRIPTION:
US of Sir Robert Bond Bridge - RB07A (SEM 2019)
END DESCRIPTION:
XS GIS Cut Line= 4
613170.7010035985431436.82278309613371.7450035985431193.47598309
613518.3642035985430993.90938309613648.5395035995430725.62128309
#Sta/Elev= 30
       0   16.22   30.97   14.48   34.96   15.73   43.95   14.45   76.92   14.51
    87.9   15.69    93.9   13.42  120.87   12.11  141.84    8.85  189.79    8.81
  258.71   12.49  281.69    4.79  315.31    1.89  321.52    1.17  328.33   -1.58
  359.76   -2.73  443.69    -.79  503.57   -1.41  573.26    2.81  580.25    4.67
  587.23    8.29  624.13   11.68  637.09   10.73  678.98   11.45  685.96   12.54
   746.8   12.47  805.64   16.41  847.53   15.88  852.52   17.91   861.5   17.23
#Mann= 3 , 0 , 0
       0     .12       0  315.31    .045       0  503.57     .12       0
Bank Sta=315.31,503.57
XS Rating Curve= 0 ,0
Exp/Cntr=0.3,0.1

Type RM Length L Ch R = 1 ,21.7300 ,78.07,78.87,72.36
BEGIN DESCRIPTION:
RB07 (RIS 2012)
END DESCRIPTION:
XS GIS Cut Line= 3
613200.4134035995431462.32998309613364.2310035985431277.97318309
613701.7815035985430758.58108309
#Sta/Elev= 30
       0   16.43   13.98   14.25   38.94   14.61   79.88   12.21   98.85   12.87
  119.82   10.38  150.77     8.8  236.64    8.82  245.63    7.29  255.62    8.03
  310.57    6.91  322.56    3.19  337.55     .28  344.16   -.839  366.11    .361
  413.81  -1.589  473.36  -1.459  497.66  -3.069     520  -2.399  529.37     .52
  542.36    5.56  555.35    6.81   604.3    8.93   610.3   10.36   613.3    9.49
  629.28   10.39  803.13   22.09  819.11   22.79   836.1   22.28  866.07   20.11
#Mann= 3 , 0 , 0
       0     .12       0  337.55    .045       0  529.37     .12       0
Bank Sta=337.55,529.37
XS Rating Curve= 0 ,0
Exp/Cntr=0.3,0.1