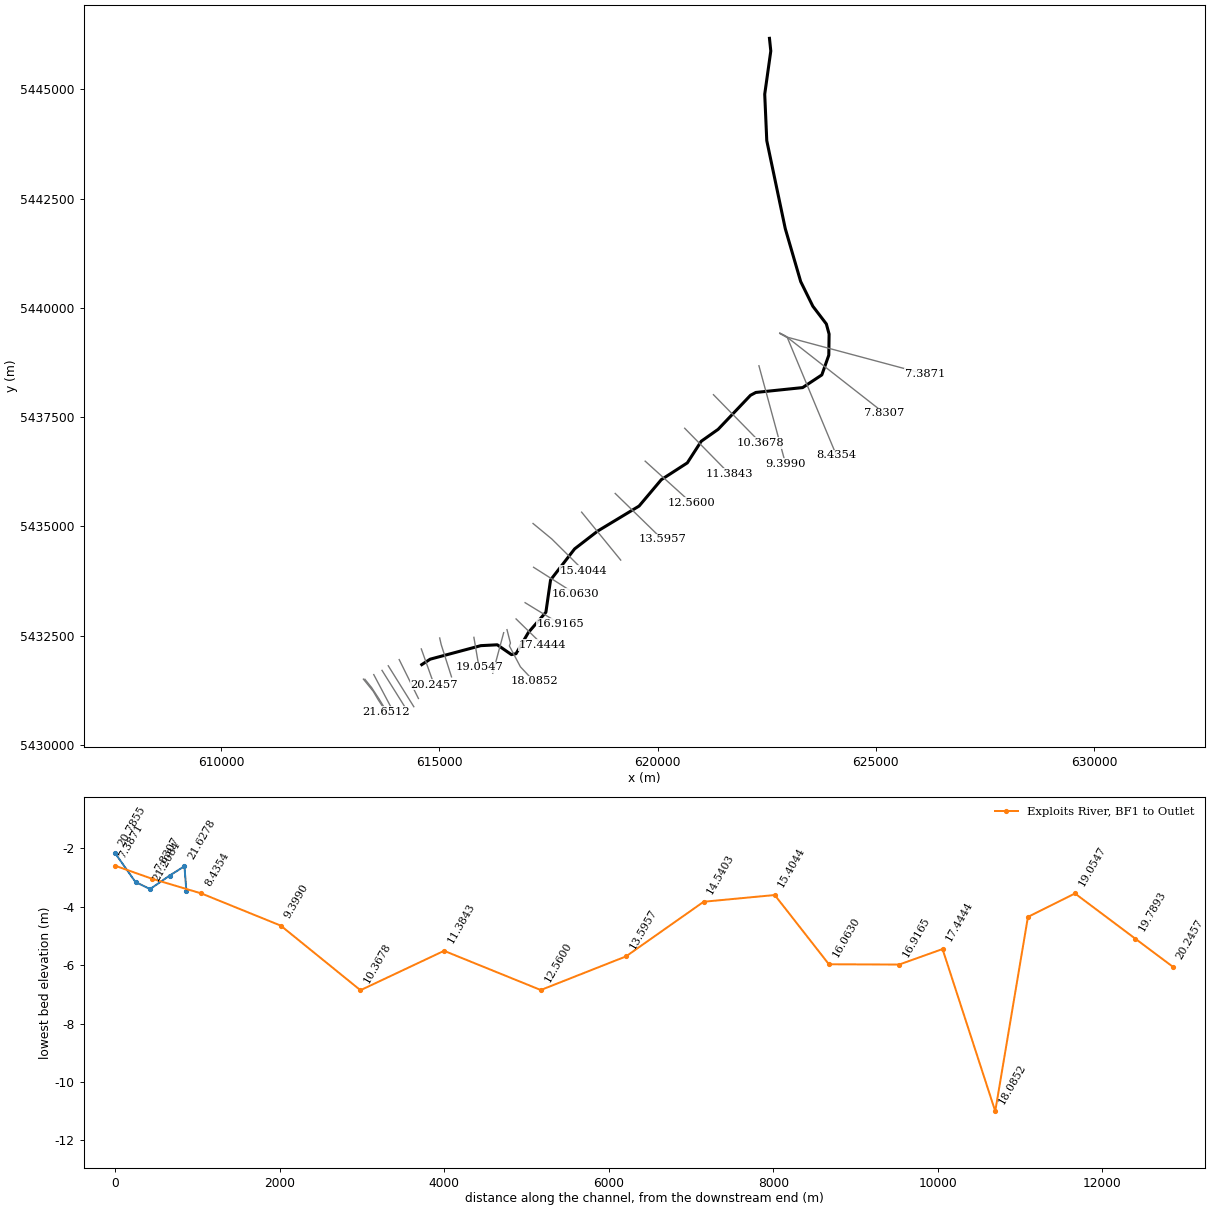
HEC-RAS study Exploits_FMM.prj: Exploits_FMM

--- Exploits_FMM.g01 (geometry) --- (continued)

Type RM Length L Ch R = 3 ,21.69   ,,,
Node Photo=.\Photos\E-CR-1.JPG
BEGIN DESCRIPTION:
Sir Robert Bond Bridge
END DESCRIPTION:
Node Name=E-CR-1
Bridge Culvert--1,0,-1,-1, 0
Deck Dist Width WeirC Skew NumUp NumDn MinLoCord MaxHiCord MaxSubmerge Is_Ogee
38,11.6,1.4,0, 300, 300, , , 0.98, 0, 3,3,,
      1012.9805917.9482518.9417821.92237 25.896526.8900330.8641531.8576935.83181
40.7994742.7865346.7606547.7541850.73478 57.689560.6700964.6442166.6312871.59893
72.5924674.5795275.5730576.5665878.55365 83.521386.5018988.4889693.45661100.4113
106.3725109.3531113.3272123.2673126.2622127.2605135.2469139.2401 142.235143.2333
146.2281 149.223150.2213154.2145157.2094 159.206160.2043168.1907173.1822185.1617
187.1583188.1566192.1498193.1481201.1345207.1243211.1175218.1056221.1004225.0936
231.0834235.0766239.0698242.0647246.0579251.0494 253.046257.0392260.0341264.0272
269.0187277.0028278.9949284.9709 288.955290.9471296.9232300.9072304.8913307.8793
308.8753311.8634314.8514316.8435318.8355319.8315320.8275324.8116326.8085327.8069
328.8053329.8038330.8022331.8006 332.799333.7975335.7943336.7928337.7912338.7896
339.7881340.7865341.7849342.7834343.7818344.7802346.7771347.7755 348.774350.7708
353.7661 355.763357.7599358.7583359.7567361.7536 362.752363.7504365.7473366.7457
371.7379372.7363375.7316378.7269379.7253380.7238383.7191385.7159387.7128389.7097
391.7065396.6987 399.694401.6908402.6893404.6861 406.683408.6799409.6783410.6767
411.6751414.6704417.6657419.6626422.6579424.6548426.6516427.6501430.6454432.6422
435.6375437.6344438.6328440.6297 443.625444.6234445.6218446.6203447.6187449.6156
 450.614451.6124452.6108454.6077456.6046458.6014460.5983463.5936465.5905469.5842
470.5826471.5811476.5732477.5717480.5669482.5638484.5607 487.556489.5528492.5481
495.5434496.5418499.5371500.5356502.5324504.5293507.5246 508.523510.5199514.5136
518.5074522.5011524.4979526.4948528.4916530.4885531.4869534.4822535.4807536.4791
537.4775 538.476539.4744540.4728541.4713542.4697543.4681544.4666 545.465546.4634
547.4619548.4603550.4572551.4556 552.454557.4462558.4446559.4431562.4384565.4337
570.4258580.4101583.4054588.3976 589.396599.3803 602.376606.3702608.3673612.3615
  613.36617.3542624.3441626.3412632.3326636.3268645.3137 649.308651.3051653.3022
654.3007659.2935660.2921664.2863670.2776675.2703680.2631681.2617 687.253688.2515
692.2457704.2284 707.224709.2211712.2168714.2139 716.211719.2067723.2009 725.198
730.1907733.1864734.1849738.1791739.1777 745.169747.1661750.1618753.1575757.1517
759.1488761.1459 763.143771.1314775.1256776.1241783.1141784.1126789.1053 792.101
793.0995796.0952800.0894803.0552805.0323808.9866810.9637820.8494826.7808830.7351
838.6437839.6323 842.598849.5179851.4951857.4265862.3694866.3237874.2322878.1865
 16.4143 16.2966  16.032 15.9704 15.8349 15.6115 15.5749  15.339 15.2986 15.0884
  14.859 14.7395 14.5567  14.501 14.3788 14.0437 13.8853 13.7072 13.6007 13.3853
 13.3297   13.26 13.1923 13.1678 13.0786 12.8918 12.7671  12.671  12.468 12.2162
 12.0159 11.9252 11.7835 11.4764 11.3598 11.3336 11.0557 10.9298 10.8531 10.8154
 10.7398 10.6486 10.6051 10.4892 10.3808 10.3452 10.3094 10.0919  9.9652  9.7009
  9.6686  9.6349  9.5753  9.5437  9.4397  9.3392  9.2963  9.1792  9.1438  9.0813
  9.0465  9.0295   9.028  9.0169  9.0187  8.9968       9  8.9871  9.0075  9.0131
  9.0384   9.049   9.034  9.0378  9.0616  9.0548  9.0957  9.1056  9.1042  9.1145
  9.1307  9.1329  9.1679  9.1722  9.2027  9.1271   9.321   9.321   9.321   9.321
   9.321   9.321   9.3219.3259769.3309539.3359299.3458819.3508589.355834 9.36081
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                                                       0           6.505   6.505
   6.505   6.505   6.5056.5099766.5149526.5199296.5298816.5348586.539834 6.54481
6.5497876.5547636.5597396.5647166.5696926.5746686.5846216.5895976.5945736.604526
6.6194556.629407 6.639366.6443376.6493126.6592666.6642426.6692186.6791716.684147
6.7090286.7140056.7289336.7438636.7488386.7538156.7687446.7786976.7886496.798602
6.8085546.8334366.8483656.8583176.8632946.8732466.8831996.8931526.8981286.903104
 6.908086.9230096.9379386.947891 6.962826.9727736.9827256.987701 7.002637.012583
7.0275127.037465 7.042447.0523937.0673227.0722997.0772757.0822517.087227 7.09718
7.1021567.1071327.1121097.1220617.1320147.1419667.1519197.1668487.1768017.196706
7.2016827.206659 7.231547.2365177.2514457.2613987.271351 7.286287.2962327.311161
 7.326097.3310667.3459957.3509727.3609247.3708777.3858067.3907827.400734 7.42064
7.440545 7.460457.4704037.4803557.490308 7.500267.5052377.5201657.5251427.530118
7.5350947.5400717.5450477.550024   7.555   7.555   7.555   7.555   7.555
      4042.9805947.9482548.9417851.92237 55.896556.8900360.8641561.8576965.83181
70.7994772.7865376.7606577.7541880.73478 87.689590.6700994.6442196.63128101.5989
102.5925104.5795105.5731106.5666108.5536113.5213116.5019 118.489123.4566130.4113
136.3725139.3531143.3272153.2673156.2622157.2605165.2469169.2401 172.235173.2333
176.2281 179.223180.2213184.2145187.2094 189.206190.2043198.1907203.1822215.1617
217.1583218.1566222.1498223.1481231.1345237.1243241.1175248.1056251.1004255.0936
261.0834265.0766269.0698272.0647276.0579281.0494 283.046287.0392290.0341294.0272
299.0187307.0028308.9949314.9709 318.955320.9471326.9232330.9072334.8913337.8793
338.8753341.8634344.8514346.8435348.8355349.8315350.8275354.8116356.8085357.8069
358.8053359.8038360.8022361.8006 362.799363.7975365.7943366.7928367.7912368.7896
369.7881370.7865371.7849372.7834373.7818374.7802376.7771377.7755 378.774380.7708
383.7661 385.763387.7599388.7583389.7567391.7536 392.752393.7504395.7473396.7457
401.7379402.7363405.7316408.7269409.7253410.7238413.7191415.7159417.7128419.7097
421.7065426.6987 429.694431.6908432.6893434.6861 436.683438.6799439.6783440.6767
441.6751444.6704447.6657449.6626452.6579454.6548456.6516457.6501460.6454462.6422
465.6375467.6344468.6328470.6297 473.625474.6234475.6218476.6203477.6187479.6156
 480.614481.6124482.6108484.6077486.6046488.6014490.5983493.5936495.5905499.5842
500.5826501.5811506.5732507.5717510.5669512.5638514.5607 517.556519.5528522.5481
525.5434526.5418529.5371530.5356532.5324534.5293537.5246 538.523540.5199544.5136
548.5074552.5011554.4979556.4948558.4916560.4885561.4869564.4822565.4807566.4791
567.4775 568.476569.4744570.4728571.4713572.4697573.4681574.4666 575.465576.4634
577.4619578.4603580.4572581.4556 582.454587.4462588.4446589.4431592.4384595.4337
600.4258610.4101613.4054618.3976 619.396629.3803 632.376636.3702638.3673642.3615
  643.36647.3542654.3441656.3412662.3326666.3268675.3137 679.308681.3051683.3022
684.3007689.2935690.2921694.2863700.2776705.2703710.2631711.2617 717.253718.2515
722.2457734.2284 737.224739.2211742.2168744.2139 746.211749.2067753.2009 755.198
760.1907763.1864764.1849768.1791769.1777 775.169777.1661780.1618783.1575787.1517
789.1488791.1459 793.143801.1314805.1256806.1241813.1141814.1126819.1053 822.101
823.0995826.0952830.0894833.0552835.0323838.9866840.9637850.8494856.7808860.7351
868.6437869.6323 872.598879.5179881.4951887.4265892.3694896.3237904.2322908.1865
 16.4143 16.2966  16.032 15.9704 15.8349 15.6115 15.5749  15.339 15.2986 15.0884
  14.859 14.7395 14.5567  14.501 14.3788 14.0437 13.8853 13.7072 13.6007 13.3853
 13.3297   13.26 13.1923 13.1678 13.0786 12.8918 12.7671  12.671  12.468 12.2162
 12.0159 11.9252 11.7835 11.4764 11.3598 11.3336 11.0557 10.9298 10.8531 10.8154
 10.7398 10.6486 10.6051 10.4892 10.3808 10.3452 10.3094 10.0919  9.9652  9.7009
  9.6686  9.6349  9.5753  9.5437  9.4397  9.3392  9.2963  9.1792  9.1438  9.0813
  9.0465  9.0295   9.028  9.0169  9.0187  8.9968       9  8.9871  9.0075  9.0131
  9.0384   9.049   9.034  9.0378  9.0616  9.0548  9.0957  9.1056  9.1042  9.1145
  9.1307  9.1329  9.1679  9.1722  9.2027  9.1271   9.321   9.321   9.321   9.321
   9.321   9.321   9.3219.3259769.3309539.3359299.3458819.3508589.355834 9.36081
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                                                       0           6.505   6.505
   6.505   6.505   6.5056.5099766.5149526.5199296.5298816.5348586.539834 6.54481
6.5497876.5547636.5597396.5647166.5696926.5746686.5846216.5895976.5945736.604526
6.6194556.629407 6.639366.6443376.6493126.6592666.6642426.6692186.6791716.684147
6.7090286.7140056.7289336.7438636.7488386.7538156.7687446.7786976.7886496.798602
6.8085546.8334366.8483656.8583176.8632946.8732466.8831996.8931526.8981286.903104
 6.908086.9230096.9379386.947891 6.962826.9727736.9827256.987701 7.002637.012583
7.0275127.037465 7.042447.0523937.0673227.0722997.0772757.0822517.087227 7.09718
7.1021567.1071327.1121097.1220617.1320147.1419667.1519197.1668487.1768017.196706
7.2016827.206659 7.231547.2365177.2514457.2613987.271351 7.286287.2962327.311161
 7.326097.3310667.3459957.3509727.3609247.3708777.3858067.3907827.400734 7.42064
7.440545 7.460457.4704037.4803557.490308 7.500267.5052377.5201657.5251427.530118
7.5350947.5400717.5450477.550024   7.555   7.555   7.555   7.555   7.555
Pier Skew, UpSta & Num, DnSta & Num=  ,393.8, 2 ,423.8, 2 , 0 , 0 , 0 ,,
     2.5     2.5
      -5      10
     2.5     2.5
      -5      10
Pier Skew, UpSta & Num, DnSta & Num=  ,477.8, 2 ,507.8, 2 , 0 , 0 , 0 ,,
     2.5     2.5
      -5      10
     2.5     2.5
      -5      10
BR Coef=-1 , 0 , 0 ,, 0 ,,,0.8,-1,,0,
WSPro=,,,, 1 ,,,, 0 ,,,, 0 ,,,,-1 ,-1 ,-1 , 0 , 0 , 0 , 0 , 0
BC Design=,, 0 ,, 0 ,,,,,,
BC HTab HWMax=15
BC Use User HTab Curves=0
BC User HTab FreeFlow(D)= 0

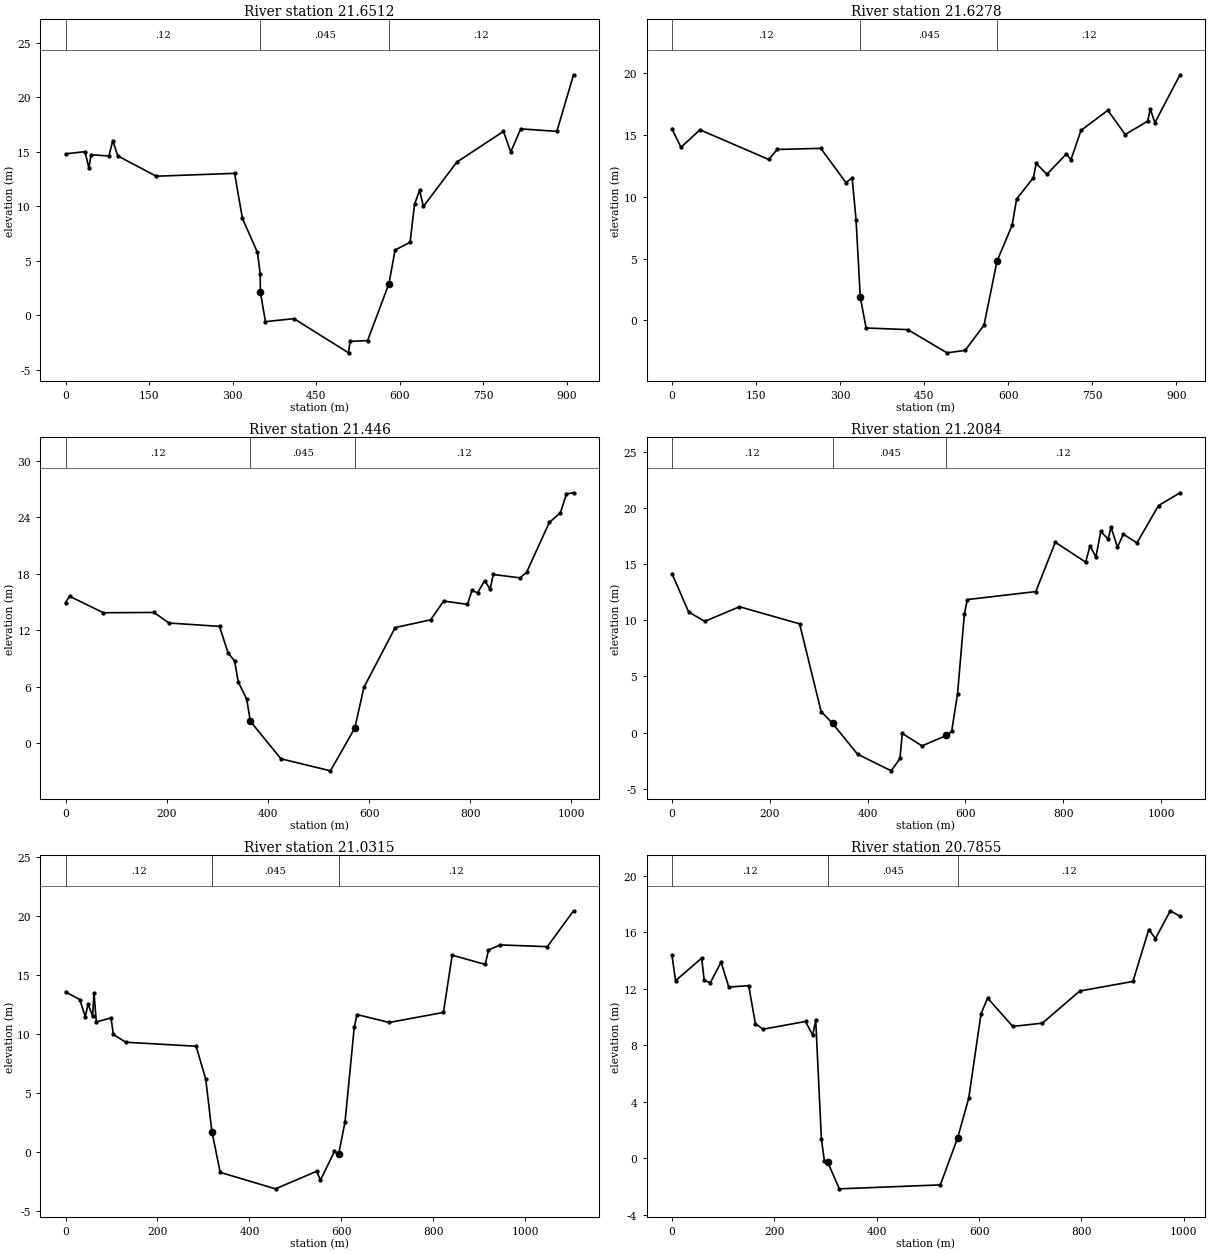
Type RM Length L Ch R = 1 ,21.6512 ,16.66,23.41,27.22
BEGIN DESCRIPTION:
RB08A-1 (SEM 2019 and RIS 2012)
END DESCRIPTION:
XS GIS Cut Line= 4
613261.6170035985431501.61708309613485.5193035985431225.37658309
613597.9675035985431034.87618309613782.0726035985430754.46888309
#Sta/Elev= 30
       0    14.8   34.96      15   41.95   13.51   45.95   14.72   77.91    14.6
    84.9   16.01   93.89   14.61  162.81   12.75  303.65   13.01  317.63    8.88
   344.6    5.77  349.59    3.81     350  2.1118358.9584  -.5877410.1924  -.3154
508.2316 -3.4499510.9328  -2.399542.3898 -2.3274  580.79     2.9  591.77    5.98
  618.73    6.69  626.72   10.16   635.7   11.45  642.69    9.98  702.59   14.04
  786.45   16.86  799.43   14.97   817.4   17.09  882.29   16.86  912.24   22.05
#Mann= 3 , 0 , 0
       0     .12       0     350    .045       0  580.79     .12       0
Bank Sta=350,580.79
XS Rating Curve= 0 ,0
Exp/Cntr=0.3,0.1

Type RM Length L Ch R = 1 ,21.6278 ,187,181,169
BEGIN DESCRIPTION:
RB08A-2 (SEM 2019 and RIS 2012)
END DESCRIPTION:
XS GIS Cut Line= 4
  613295.3883036 5431498.2668831  613448.8469036 5431309.0893831
  613619.5035036 5431048.4742831  613802.0664036 5430748.1715831
#Sta/Elev= 30
       0   15.51   15.97      14   49.92   15.42  172.71   13.02  187.69   13.83
  265.56   13.92  310.49   11.15  321.47   11.53  328.46    8.16     336  1.9016
346.3911  -.6066420.7803  -.7397490.7531 -2.6166523.1646 -2.4186556.8192  -.3754
  580.07    4.81  607.03    7.71  615.02    9.83  644.97   11.55  649.96   12.71
  668.93   11.82  703.88   13.47  711.86   12.99  729.84   15.37  777.76      17
  808.71   15.04  848.65   16.11  853.64   17.09  861.63   15.99  906.55   19.87
#Mann= 3 , 0 , 0
       0     .12       0     336    .045       0  580.07     .12       0
Bank Sta=336,580.07
XS Rating Curve= 0 ,0
Exp/Cntr=0.3,0.1

Type RM Length L Ch R = 1 ,21.446  ,246,237,243
BEGIN DESCRIPTION:
RB09 (RIS 2012)
END DESCRIPTION:
XS GIS Cut Line= 2
      613498.937     5431604.995      613968.811     5430717.832
#Sta/Elev= 30
       0 14.92347.983438 15.591774.84473 13.8407174.6377 13.8715204.5756 12.7504
304.3686 12.3962321.3334  9.5776334.3065  8.7119 341.292  6.5208358.2566  4.6434
365.2419  2.3296   425.7   -1.66  523.64   -2.94571.8054  1.5971589.7674  5.9177
651.6743 12.2702721.5691 13.0853  747.53 15.0814794.4594  14.731803.4459 16.2133
814.4294 15.9548828.4083 17.2501839.3918 16.3598845.3828 17.9022898.3032 17.5443
911.2836 18.1267956.2161 23.4223 978.183 24.4555 990.165  26.4641004.144 26.5752
#Mann= 3 , 0 , 0
       0     .12       0365.2419    .045       0571.8054     .12       0
Bank Sta=365.2419,571.8054
XS Rating Curve= 0 ,0
Exp/Cntr=0.3,0.1

Type RM Length L Ch R = 1 ,21.2084 ,182.43,176.82,180.43
BEGIN DESCRIPTION:
RB10 (RIS 2012)
END DESCRIPTION:
XS GIS Cut Line= 2
613687.8244035985431702.24668309614239.1337035985430822.15858309
#Sta/Elev= 30
       0   14.15   33.98   10.74   66.97     9.9  137.93    11.2  260.88    9.68
  304.85    1.88  328.31     .82  379.34  -1.919  448.29  -3.399  466.03  -2.299
  470.78    -.07  511.08  -1.179  561.16    -.25  571.73     .11  583.72    3.46
  597.71   10.55  603.71   11.84  743.65   12.55  783.63   16.94   845.6   15.17
  854.59   16.62  866.59   15.63  876.58    17.9  891.57   17.21  897.57   18.28
  910.57   16.49  922.56   17.65  950.55   16.89  994.53    20.2  1038.5   21.34
#Mann= 3 , 0 , 0
       0     .12       0  328.31    .045       0  561.16     .12       0
Bank Sta=328.31,561.16
XS Rating Curve= 0 ,0
Exp/Cntr=0.3,0.1

Type RM Length L Ch R = 1 ,21.0315 ,257.5,245.99,235.31
BEGIN DESCRIPTION:
RB11 (RIS 2012)
END DESCRIPTION:
XS GIS Cut Line= 2
613830.8889035985431807.30468309614416.2832035985430870.52988309
#Sta/Elev= 30
       0   13.57   30.99   12.93   42.99   11.47   48.98   12.54   58.98   11.52
   61.98    13.5   66.98   11.02   98.97   11.37  103.97    9.96  130.96     9.3
  283.91    8.96   304.9    6.17  318.36     1.7  336.39  -1.759  456.61  -3.159
  546.03  -1.669  554.37  -2.419  584.81     .02   593.7    -.23   607.8    2.53
   627.8   10.56   633.8   11.65  703.77   10.98  821.74   11.83  840.73    16.7
  912.71   15.91  919.71   17.14   945.7   17.57 1047.67   17.42 1104.65   20.47
#Mann= 3 , 0 , 0
       0     .12       0  318.36    .045       0   593.7     .12       0
Bank Sta=318.36,593.7
XS Rating Curve= 0 ,0
Exp/Cntr=0.3,0.1

Type RM Length L Ch R = 1 ,20.7855 ,545.23,539.81,536.88
BEGIN DESCRIPTION:
RB12 (RIS 2012)
END DESCRIPTION:
XS GIS Cut Line= 2
614081.4162035985431948.71658309614521.7383035985431059.23598309
#Sta/Elev= 30
       0   14.38       7   12.58   57.97   14.18   62.97   12.61   74.96   12.44
   95.95    13.9  110.94   12.13  149.92   12.23  162.92    9.53  177.91    9.14
  260.87    9.69  274.86    8.72  280.86    9.77  291.85    1.37  297.85    -.22
  303.91    -.26  326.89  -2.179  524.29  -1.899  557.93    1.42  579.71    4.24
   603.7   10.23  616.69   11.35  665.67    9.34  723.64    9.57   796.6   11.85
  900.55   12.53  931.53   16.21  944.53   15.57  973.51   17.54   992.5   17.15
#Mann= 3 , 0 , 0
       0     .12       0  303.91    .045       0  557.93     .12       0
Bank Sta=303.91,557.93
XS Rating Curve= 0 ,0
Exp/Cntr=0.3,0.1

River Reach=Exploits River  ,BF1 to Outlet
Reach XY= 30
  614598.8519133  5431833.881883     614791.4881    5431958.2861
     615951.4954    5432267.7654     616327.9781     5432287.547
     616652.6424    5432063.2425     616758.1957    5432083.6825
     617041.7554    5432569.9871     617442.0314    5433032.4325
     617548.7145    5433770.3891     618100.2081    5434482.4732
     618630.2879    5434891.5962      619577.313    5435462.8482
     620085.7903     5436066.416     620681.8102    5436451.0233
     621001.2279     5436946.276     621387.0893    5437218.0493
      622129.673    5437998.1886      622251.224    5438062.7584
     623324.0339    5438173.9955     623763.3601    5438464.2052
     623922.7592    5438916.0728     623929.6066     5439399.006
     623867.0363    5439629.6774     623557.4262    5440035.6788
      623278.784    5440600.8193      622925.463    5441813.1761
     622502.0499    5443824.9191     622454.9299    5444889.1844
     622594.0228    5445876.5334     622563.7261    5446167.1662

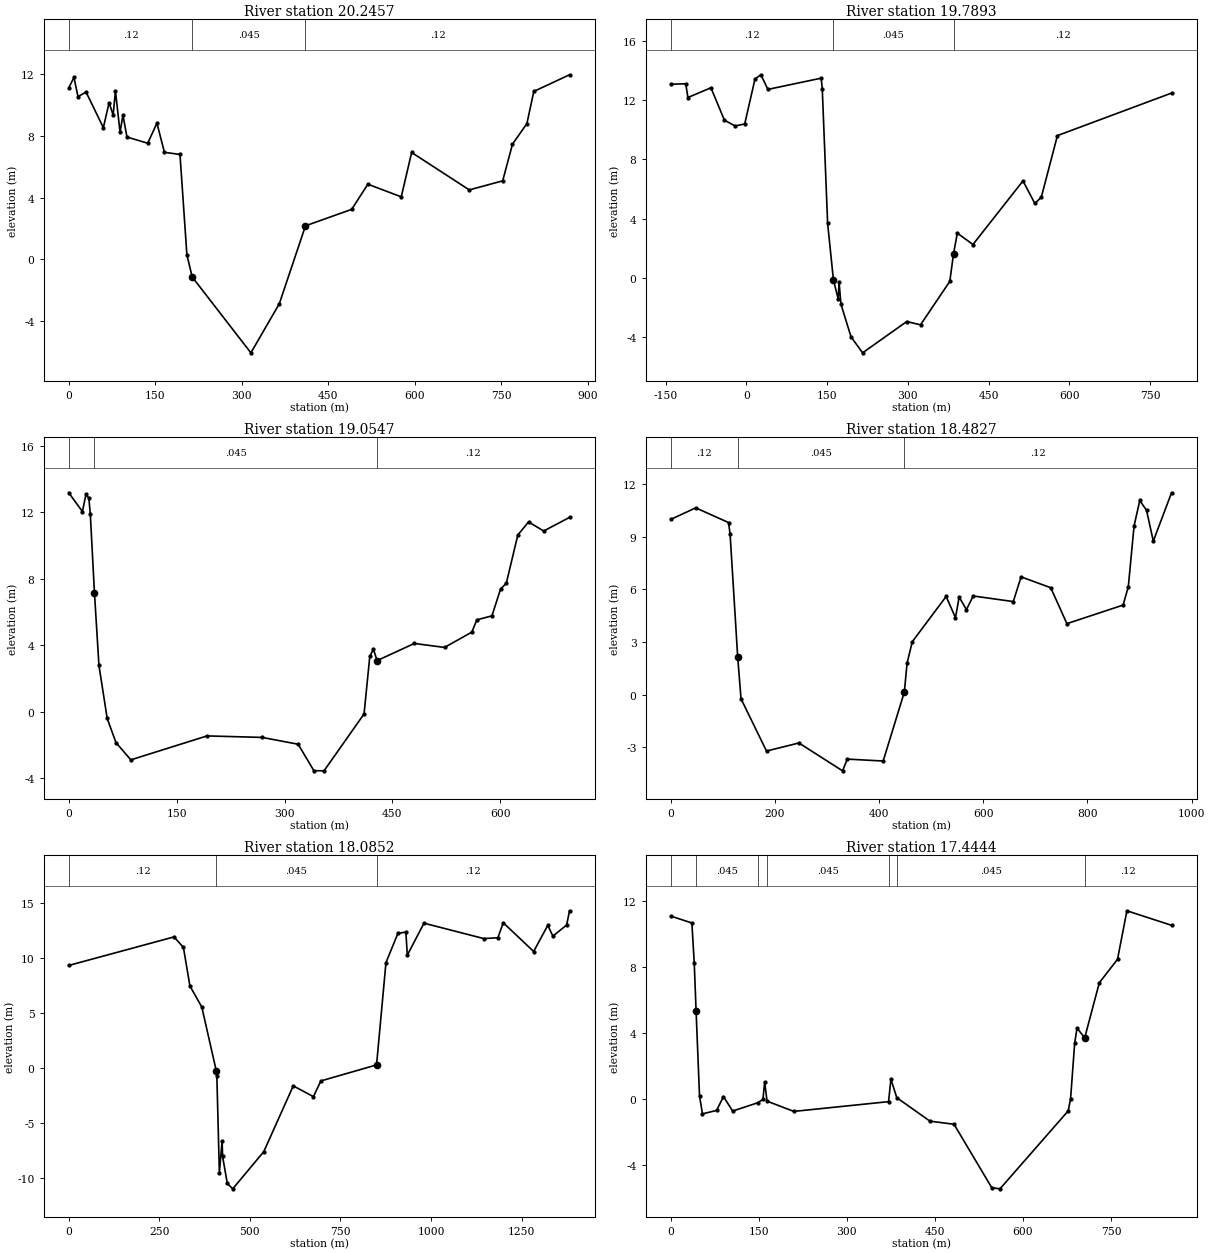
Type RM Length L Ch R = 1 ,20.2457 ,458.18,456.43,465.88
BEGIN DESCRIPTION:
RB12A (SEM 2019)
END DESCRIPTION:
XS GIS Cut Line= 2
614588.1294035995432192.95828309614880.6656035995431375.34388309
#Sta/Elev= 30
       0   11.13    8.99   11.81   15.99   10.56   29.98   10.86   59.96    8.55
   69.95   10.17   76.94    9.37   80.94   10.93   88.94    8.25   93.93    9.36
  100.93    7.94   136.9    7.54  152.89    8.84  165.88    6.95  192.86    6.81
  204.85      .3  214.07   -1.14  315.83   -6.06  365.16   -2.87  410.48    2.18
  490.65    3.25  518.63    4.88  576.58    4.06  594.57    6.94   694.5    4.51
  752.45     5.1  769.44    7.48  794.42    8.81  806.41    10.9  868.37   11.98
#Mann= 3 , 0 , 0
       0     .12       0  214.07    .045       0  410.48     .12       0
Bank Sta=214.07,410.48
XS Rating Curve= 0 ,0
Exp/Cntr=0.3,0.1

Type RM Length L Ch R = 1 ,19.7893 ,785.36,734.63,757.01
BEGIN DESCRIPTION:
R32 (RIS 2013)
END DESCRIPTION:
XS GIS Cut Line= 3
  615009.2104036 5432443.4511831  615044.0792036 5432291.0435831
  615279.8032036 5431553.9020831
#Sta/Elev= 30
  -140.5    13.1 -112.62   13.13 -108.63    12.2  -65.81   12.86  -40.92   10.67
     -21   10.27   -3.08   10.41      16   13.45      27   13.74      40   12.75
  138.99   13.51  140.99   12.81  150.99    3.67  161.78    -.17  170.64   -1.45
  172.22     -.3  175.78   -1.81  194.48   -4.02  215.97    -5.1  297.95   -2.98
   323.6    -3.2  377.98    -.26  384.95    1.63  391.98    3.01  420.98    2.24
  513.97    6.55  535.97    5.02  547.97    5.44  577.97    9.62  789.96    12.5
#Mann= 3 , 0 , 0
  -140.5     .12       0  161.78    .045       0  384.95     .12       0
Bank Sta=161.78,384.95
XS Rating Curve= 0 ,0
Exp/Cntr=0.3,0.1

Type RM Length L Ch R = 1 ,19.0547 ,647.22,571.99,516.76
BEGIN DESCRIPTION:
R33 (RIS 2013)
END DESCRIPTION:
XS GIS Cut Line= 2
615792.7878035995432458.06978309615909.7769035995431771.74048309
#Sta/Elev= 30
       0   13.17   18.98   12.04   23.97   13.09   27.97   12.84   29.97   11.87
   35.69    7.17   41.95    2.79   53.43     -.4   65.62   -1.85   86.28   -2.89
  192.27   -1.45  268.74   -1.54  318.95   -1.95  340.74   -3.54  354.86   -3.55
  410.55    -.13  418.54    3.34  423.53    3.76  428.74    3.08  480.47    4.11
  522.42    3.87  560.38    4.79  567.37    5.53  588.35    5.77  600.34    7.38
  608.33    7.73  624.31   10.63  639.29   11.42  660.27   10.87  696.23   11.69
#Mann= 3 , 0 , 0
       0     .12       0   35.69    .045       0  428.74     .12       0
Bank Sta=35.69,428.74
XS Rating Curve= 0 ,0
Exp/Cntr=0.3,0.1

Type RM Length L Ch R = 1 ,18.4827 ,245.29,397.53,532.43
BEGIN DESCRIPTION:
R34 (RIS 2013)
END DESCRIPTION:
XS GIS Cut Line= 2
616475.0278035985432564.42628309616224.8114035995431636.20268309
#Sta/Elev= 30
       0      10   47.97   10.66  110.93    9.82  113.92    9.16  128.56    2.12
  134.91    -.24  183.81  -3.221  246.03  -2.761  329.79  -4.351  338.91  -3.681
  407.82  -3.791  448.43     .15  453.69     1.8  463.69    3.02  528.64     5.6
  546.63    4.39  553.63    5.57  567.62    4.85  580.61    5.63  657.56    5.31
  672.55    6.72  729.51     6.1  760.49    4.05  868.41    5.11  878.41    6.16
   889.4    9.62  900.39   11.08  913.38   10.52  926.37    8.76  961.35   11.52
#Mann= 3 , 0 , 0
       0     .12       0  128.56    .045       0  448.43     .12       0
Bank Sta=128.56,448.43
XS Rating Curve= 0 ,0
Exp/Cntr=0.3,0.1

Type RM Length L Ch R = 1 ,18.0852 ,647.41,640.75,696.96
BEGIN DESCRIPTION:
Jumpers Brook - R35 (RIS 2013)
END DESCRIPTION:
XS GIS Cut Line= 5
  616550.8643036 5432633.4600831  616629.3533036 5432326.8587831
  616606.0038036 5432261.3738831  616858.1945036 5431783.3442831
  617170.9606036 5431451.9167831
#Sta/Elev= 30
       0    9.35  290.53   11.95  316.49   10.99  334.36    7.48  367.14    5.57
  407.01    -.23  408.77    -.76   415.7   -9.53  423.24   -6.64  424.58   -8.05
  437.59   -10.5   452.5     -11   538.3   -7.61  619.67   -1.62  675.28    -2.6
  695.85   -1.17  849.56     .29  875.53    9.61   908.5   12.27  930.48   12.39
  934.48   10.29  980.45    13.2 1145.34    11.8 1184.32   11.87 1199.31   13.24
 1283.26   10.62 1322.23   13.01 1336.23   12.02  1374.2   13.03  1382.2   14.33
#Mann= 3 , 0 , 0
       0     .12       0  407.01    .045       0  849.56     .12       0
Bank Sta=407.01,849.56
XS Rating Curve= 0 ,0
Exp/Cntr=0.3,0.1

Type RM Length L Ch R = 1 ,17.4444 ,523.43,527.87,620.32
BEGIN DESCRIPTION:
R36 (RIS 2013)
END DESCRIPTION:
XS GIS Cut Line= 2
616758.7171035995432879.29438309617369.7712035985432284.14078309
#Sta/Elev= 30
       0   11.07      36   10.65      40    8.22   43.12    5.34      49     .18
   54.03   -.911   78.09   -.701   89.79    .139  105.42   -.741     148    -.24
     157    -.03     160    1.02     164    -.14  209.67   -.761     371    -.17
     375    1.19     385     .07  441.52  -1.351  482.53  -1.541  546.77  -5.381
  560.78  -5.451  676.99    -.73  680.99    -.02  687.99    3.36  691.99    4.28
  705.12     3.7  729.99    7.03  760.99    8.45  776.99   11.39  852.99   10.51
#Mann= 7 ,-1 , 0
       0     .12       0   43.12    .045       0     148     .12       0
     164    .045       0     371     .12       0     385    .045       0
  705.12     .12       0
Bank Sta=43.12,705.12
XS Rating Curve= 0 ,0
Exp/Cntr=0.3,0.1

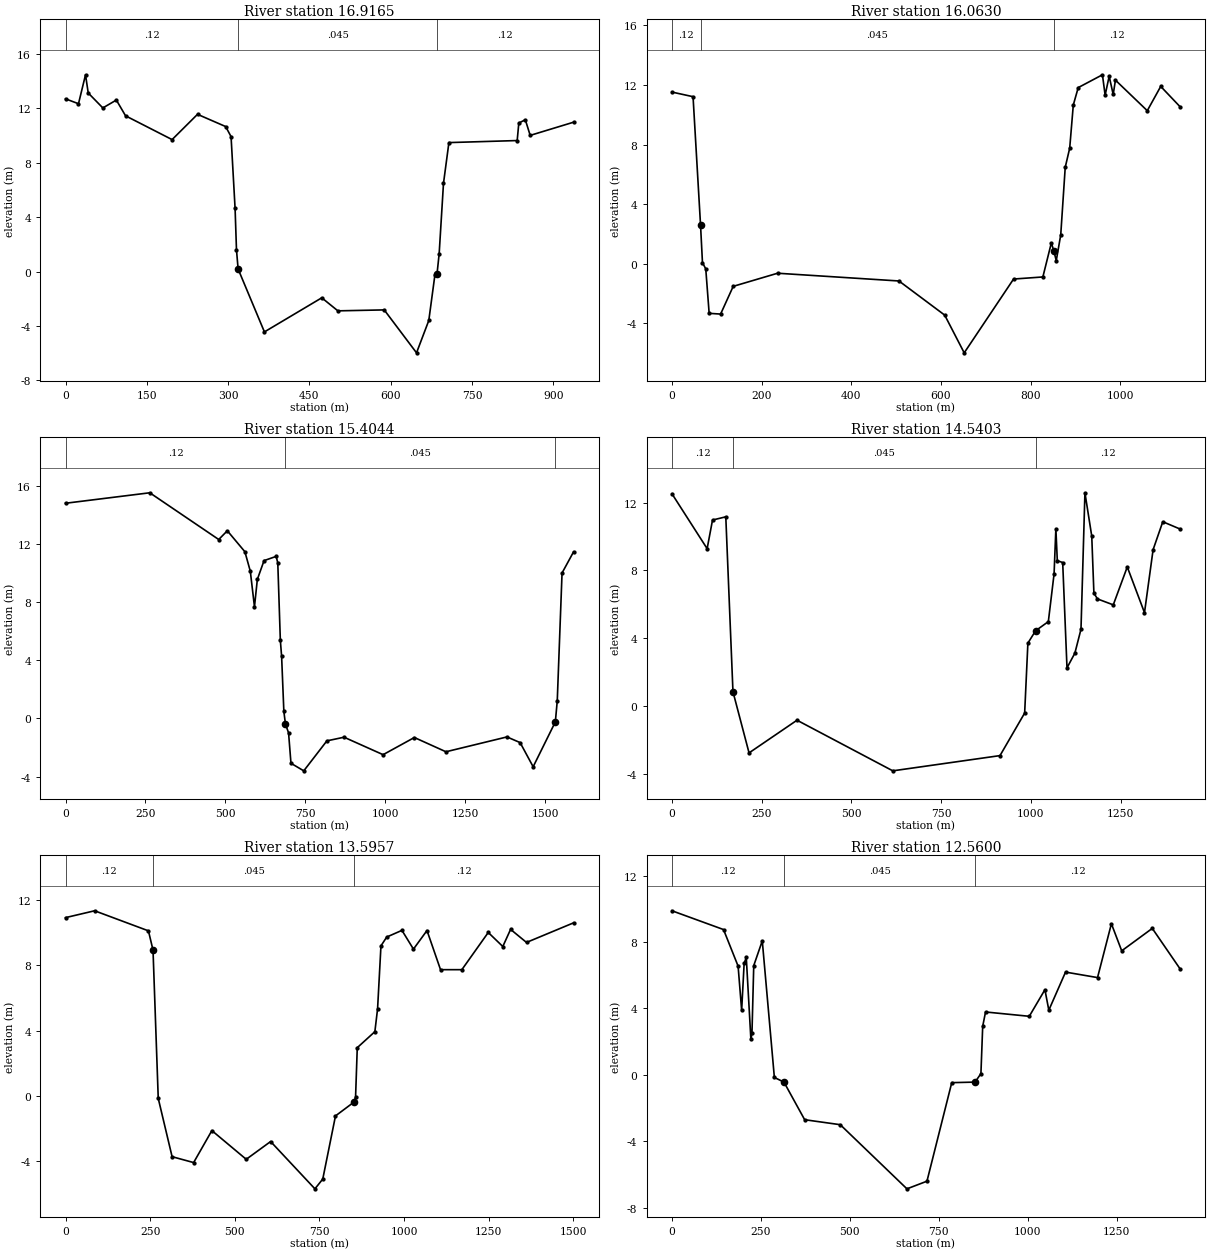
Type RM Length L Ch R = 1 ,16.9165 ,1014.1,853.51,802.13
BEGIN DESCRIPTION:
R37 (RIS 2013)
END DESCRIPTION:
XS GIS Cut Line= 3
  616965.9082036 5433251.0869831  617228.0941036 5433090.5394831
  617767.6872036 5432765.6038831
#Sta/Elev= 30
       0   12.71   23.96   12.35   36.93   14.48   41.92   13.14   68.87   12.04
   93.83   12.62   110.8   11.46  196.64    9.71  243.55   11.57  295.46   10.67
  305.44    9.93  312.87    4.64  315.43    1.61  318.43     .19  366.98  -4.442
   472.8  -1.932  502.52  -2.892     588  -2.822  647.62  -5.982  670.25  -3.602
  681.59   -.232  685.36     -.2  689.36     1.3  697.36    6.49  707.35    9.49
  833.33    9.64  836.33   10.93  848.33   11.17  857.32   10.02  937.31   10.99
#Mann= 3 , 0 , 0
       0     .12       0  318.43    .045       0  685.36     .12       0
Bank Sta=318.43,685.36
XS Rating Curve= 0 ,0
Exp/Cntr=0.3,0.1

Type RM Length L Ch R = 1 ,16.0630 ,751.89,658.58,575.09
BEGIN DESCRIPTION:
R38 (RIS 2013)
END DESCRIPTION:
XS GIS Cut Line= 2
617160.0942035985434061.37518309618116.3002035985433453.83388309
#Sta/Elev= 30
       0   11.52      47   11.21   63.65    2.63   67.99     .08   75.36   -.342
    82.9  -3.322  108.46  -3.372  136.54  -1.512  235.51   -.632  506.19  -1.152
  608.19  -3.442  651.65  -5.972  761.73  -1.022  827.07   -.882  845.92     1.4
  851.82     .84  856.91     .21  866.91    1.94  876.91    6.47  886.91    7.76
  894.91   10.65  905.91   11.82   959.9   12.68   965.9   11.31   974.9   12.58
   983.9   11.36   988.9   12.32 1059.89   10.27 1089.89    11.9 1132.89   10.54
#Mann= 3 , 0 , 0
       0     .12       0   63.65    .045       0  851.82     .12       0
Bank Sta=63.65,851.82
XS Rating Curve= 0 ,0
Exp/Cntr=0.3,0.1

Type RM Length L Ch R = 1 ,15.4044 ,907.64,864.13,870.73
BEGIN DESCRIPTION:
R39 (RIS 2013)
END DESCRIPTION:
XS GIS Cut Line= 3
  617147.8096036 5435063.4864831  617579.2289036 5434707.7550831
  618310.3579036 5433982.0282831
#Sta/Elev= 30
       0   14.78  263.61    15.5  479.29   12.29  506.25   12.89  561.17   11.45
  578.15   10.11  591.14    7.67  600.13    9.55  621.12   10.84  659.08   11.13
  664.08   10.68  672.07    5.37  676.07    4.26  683.06     .48  688.06    -.39
  697.81   -.993   705.3  -3.083  745.35  -3.603  817.71  -1.543  871.38  -1.293
  993.54  -2.493 1091.36  -1.313 1190.16  -2.293 1381.04  -1.273 1422.18  -1.663
 1462.98  -3.323 1532.38    -.24 1538.38    1.21 1553.36    9.99 1589.33   11.44
#Mann= 3 , 0 , 0
       0     .12       0  688.06    .045       0 1532.38     .12       0
Bank Sta=688.06,1532.38
XS Rating Curve= 0 ,0
Exp/Cntr=0.3,0.1

Type RM Length L Ch R = 1 ,14.5403 ,930.8,944.63,980.79
BEGIN DESCRIPTION:
R40 (RIS 2013)
END DESCRIPTION:
XS GIS Cut Line= 2
618260.4525035985435323.05038309619155.9164035985434226.32078309
#Sta/Elev= 30
       0   12.53   97.99    9.29  112.99   10.98  149.99   11.17  169.98     .84
  214.81  -2.773  348.47   -.843  615.41  -3.833  914.18  -2.933   982.9    -.42
   991.9    3.71 1013.35    4.44 1048.89    4.98 1064.89     7.8 1069.89   10.47
 1073.89    8.58 1088.89    8.47 1100.89    2.25 1122.88    3.12 1139.88    4.53
 1150.88   12.59 1169.88   10.03 1175.88    6.66 1185.88    6.32 1229.87    5.97
 1268.87    8.21 1316.86    5.51 1340.86    9.23 1367.86   10.88 1415.86   10.45
#Mann= 3 , 0 , 0
       0     .12       0  169.98    .045       0 1013.35     .12       0
Bank Sta=169.98,1013.35
XS Rating Curve= 0 ,0
Exp/Cntr=0.3,0.1

Type RM Length L Ch R = 1 ,13.5957 ,1026.18,1035.67,1099.38
BEGIN DESCRIPTION:
R41 (RIS 2013)
END DESCRIPTION:
XS GIS Cut Line= 2
619029.9852035995435751.21118309620104.7006035985434704.47138309
#Sta/Elev= 30
       0   10.92   85.96   11.34  244.87   10.11  258.41    8.93  273.86    -.16
  314.76  -3.733  378.34  -4.093  432.23  -2.133  533.66  -3.893  605.71  -2.803
  736.52  -5.703  759.68  -5.103  797.25  -1.233   852.2    -.38  856.56    -.07
  861.56    2.95  913.53    3.93  921.53    5.33  931.52    9.19  948.51    9.73
  993.49   10.14 1027.47    8.99 1067.45   10.13 1107.43    7.73  1170.4    7.73
 1248.35   10.01 1291.33    9.15 1314.32    10.2 1361.29     9.4 1500.22    10.6
#Mann= 3 , 0 , 0
       0     .12       0  258.41    .045       0   852.2     .12       0
Bank Sta=258.41,852.2
XS Rating Curve= 0 ,0
Exp/Cntr=0.3,0.1

Type RM Length L Ch R = 1 ,12.5600 ,1171.27,1175.67,1176.86
BEGIN DESCRIPTION:
R42 (RIS 2013)
END DESCRIPTION:
XS GIS Cut Line= 2
619716.0507035985436490.46238309620776.3559035985435533.48708309
#Sta/Elev= 30
       0    9.88  144.93    8.75  185.91    6.55   195.9    3.89   202.9    6.72
   208.9    7.07  221.89    2.14  224.89    2.51  229.89    6.58  253.88    8.07
  287.86    -.15  314.85    -.43  373.03  -2.693  473.12  -2.993   660.6  -6.853
  716.86  -6.393  786.56   -.463  852.06    -.43  868.57     .08  873.57    2.93
  881.56    3.79  1004.5    3.53 1048.48    5.13 1059.48     3.9 1106.45    6.19
 1196.41    5.86 1235.39     9.1 1264.37    7.47 1350.33    8.82 1428.29    6.39
#Mann= 3 , 0 , 0
       0     .12       0  314.85    .045       0  852.06     .12       0
Bank Sta=314.85,852.06
XS Rating Curve= 0 ,0
Exp/Cntr=0.3,0.1

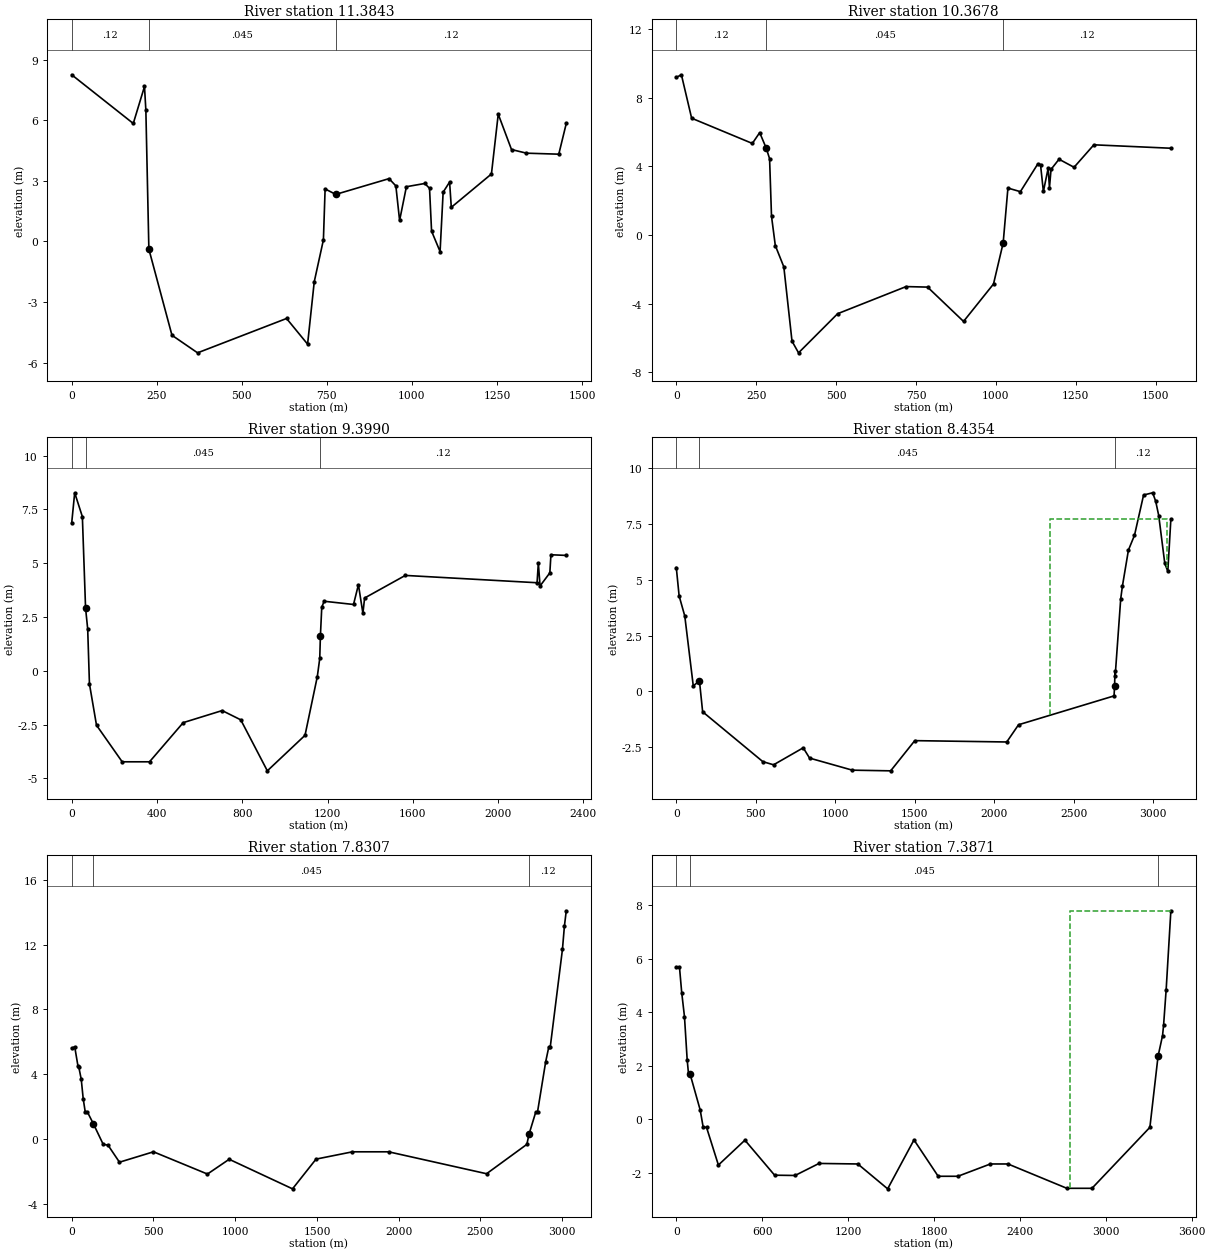
Type RM Length L Ch R = 1 ,11.3843 ,1031.75,1016.52,1068.63
BEGIN DESCRIPTION:
R43 (RIS 2013)
END DESCRIPTION:
XS GIS Cut Line= 2
620621.5247035995437243.18888309621640.5493035985436206.30378309
#Sta/Elev= 30
       0    8.25  180.98    5.84  213.97    7.67  217.97     6.5  226.83    -.38
  294.73  -4.642  369.99  -5.512  631.54  -3.812  693.39  -5.082  712.99  -1.992
   739.9     .08   744.9     2.6  776.19    2.33  932.87    3.11  952.87    2.75
  963.87    1.04  983.86    2.71 1037.86    2.87 1051.85    2.63 1057.85     .51
 1082.85     -.5 1091.85    2.44 1110.84    2.94 1115.84    1.69 1233.82    3.34
 1253.82     6.3 1292.81    4.55 1336.81    4.37 1431.79    4.32 1453.79    5.84
#Mann= 3 , 0 , 0
       0     .12       0  226.83    .045       0  776.19     .12       0
Bank Sta=226.83,776.19
XS Rating Curve= 0 ,0
Exp/Cntr=0.3,0.1

Type RM Length L Ch R = 1 ,10.3678 ,1291.42,968.8,733.55
BEGIN DESCRIPTION:
R43A (SEM 2019)
END DESCRIPTION:
XS GIS Cut Line= 2
621280.7425035985438011.19808309622364.1722035995436906.36678309
#Sta/Elev= 30
       0    9.19   15.99    9.34   47.98    6.81  237.91    5.34   260.9    5.97
  281.53    5.06  291.89    4.45  297.89     1.1   309.8    -.61  336.42   -1.85
  362.03   -6.18  382.47   -6.86  504.83   -4.58  719.03      -3  786.19   -3.03
  898.77   -5.03  992.49   -2.85 1022.72    -.46 1037.61    2.74  1076.6    2.53
 1130.58    4.13 1139.57    4.11 1148.57    2.54 1163.56     3.9 1167.56    2.76
 1172.56    3.83 1197.55    4.42 1244.53    3.95 1306.51    5.26 1547.42    5.06
#Mann= 3 , 0 , 0
       0     .12       0  281.53    .045       0 1022.72     .12       0
Bank Sta=281.53,1022.72
XS Rating Curve= 0 ,0
Exp/Cntr=0.3,0.1

Type RM Length L Ch R = 1 ,9.3990  ,991.28,963.65,1694.22
BEGIN DESCRIPTION:
Beatons Point - R43B (SEM 2019)
END DESCRIPTION:
XS GIS Cut Line= 2
622322.3468035985438673.13068309622931.2769035995436434.97468309
#Sta/Elev= 30
       0    6.87      14    8.27   49.99    7.16   64.99    2.91   74.98    1.94
    83.2    -.61  116.28   -2.53  236.71   -4.23  365.03   -4.23     523   -2.41
  705.63   -1.85  792.85   -2.28   917.5   -4.65  1094.2      -3  1151.9    -.27
 1163.29     .57 1166.44    1.63 1172.75    2.95 1183.75    3.23 1321.72    3.08
 1344.71       4 1365.71    2.67 1373.71    3.38 1564.66    4.43 2182.53    4.09
 2188.52    5.01 2196.52    3.94 2242.51    4.55 2247.51    5.39 2319.49    5.36
#Mann= 3 , 0 , 0
       0     .12       0   64.99    .045       0 1166.44     .12       0
Bank Sta=64.99,1166.44
XS Rating Curve= 0 ,0
Exp/Cntr=0.3,0.1

Type RM Length L Ch R = 1 ,8.4354  ,6.88,604.64,1333.08
BEGIN DESCRIPTION:
Rattling Brook - R43C (SEM 2019)
END DESCRIPTION:
XS GIS Cut Line= 3
     622801.7995    5439411.2536     622973.3818    5439317.1031
      624096.175    5436625.8682
#Sta/Elev= 30
       0   5.537   17.79    4.27   53.38    3.37  106.75     .25  145.67     .47
  165.74    -.91   544.7   -3.14  612.15   -3.28  798.68   -2.52  838.52   -2.98
  1107.6   -3.52 1348.87   -3.55 1500.56    -2.2 2079.24   -2.26 2153.45   -1.49
 2754.48     -.2 2757.73     .26 2760.41     .91 2761.33     .68 2796.32    4.14
 2806.83     4.7 2844.94    6.32 2883.06    6.98 2940.24    8.78 2997.42    8.88
 3016.48     8.5 3035.54    7.86 3073.66    5.72 3092.72    5.37 3111.84   7.697
#Mann= 3 , 0 , 0
       0      .1       0  145.67    .045       0 2757.73     .12       0
#XS Ineff= 1 ,-1
 2350.253087.929   7.697
Permanent Ineff=
       F
Bank Sta=145.67,2757.73
XS Rating Curve= 0 ,0
Exp/Cntr=0.3,0.1

Type RM Length L Ch R = 1 ,7.8307  ,6.81,443.64,1256.91
XS GIS Cut Line= 4
      622800.583    5439417.0572     622897.9524    5439369.6848
     622994.6865    5439306.8048     625201.4618    5437581.8264
#Sta/Elev= 30
       0   5.617   18.48   5.697   38.46   4.507   43.16   4.467   58.41   3.697
   70.28   2.507   82.62   1.697    95.5   1.697  132.28    .967  192.59   -.303
     222   -.353  292.07  -1.403  500.16   -.763  830.18  -2.133  963.03  -1.223
 1350.48  -3.043 1494.29  -1.213 1717.19   -.763 1938.18   -.763 2537.25  -2.113
 2783.76   -.303 2796.44    .307 2838.37   1.697 2848.94   1.6972898.679   4.777
 2917.83   5.697 2926.76   5.697 3001.22  11.697 3013.22  13.127 3024.62  14.077
#Mann= 3 , 0 , 0
       0      .1       0  132.28    .045       0 2796.44     .12       0
Bank Sta=132.28,2796.44
XS Rating Curve= 0 ,0
Exp/Cntr=0.3,0.1

Type RM Length L Ch R = 1 ,7.3871  ,10.05,431.1,1773.96
BEGIN DESCRIPTION:
Norris Arm
END DESCRIPTION:
XS GIS Cut Line= 3
     622802.6863    5439421.3447     622990.5081    5439322.6188
     626122.7197    5438484.0725
#Sta/Elev= 30
       0   5.698   22.11   5.698    37.8   4.738   57.12   3.838   75.95   2.228
   85.37   1.698   95.91   1.698  166.88    .348  187.96   -.302  211.16   -.302
  294.09  -1.712  479.31   -.782  686.77  -2.092  829.84  -2.102  996.93  -1.652
 1267.92  -1.672  1476.4  -2.602 1660.35   -.772 1829.41  -2.132 1967.22  -2.132
  2193.9  -1.672 2316.96  -1.672 2728.21  -2.582 2903.69  -2.5823308.159   -.302
 3365.26   2.3583396.621   3.1283403.741   3.508 3421.91   4.848 3454.71   7.798
#Mann= 3 , 0 , 0
       0      .1       0   95.91    .045       0 3365.26     .12       0
#XS Ineff= 2 , 0
                         2748.79           7.794
Permanent Ineff=
       F       F
Bank Sta=95.91,3365.26
XS Rating Curve= 0 ,0
Exp/Cntr=0.3,0.1