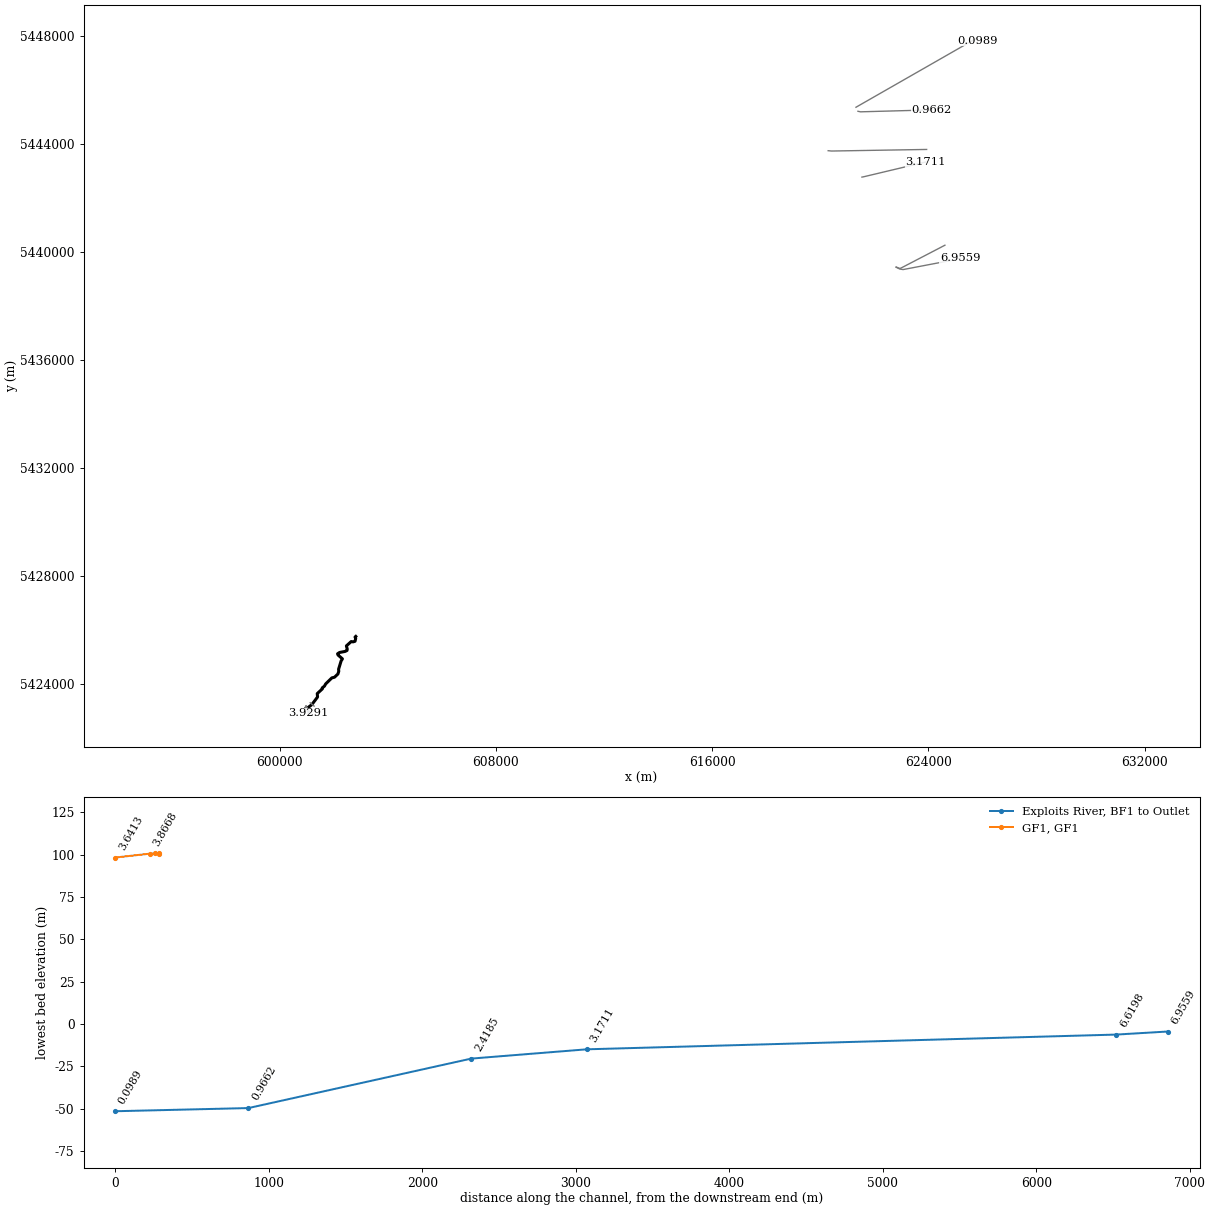
HEC-RAS study Exploits_FMM.prj: Exploits_FMM

--- Exploits_FMM.g01 (geometry) --- (continued)

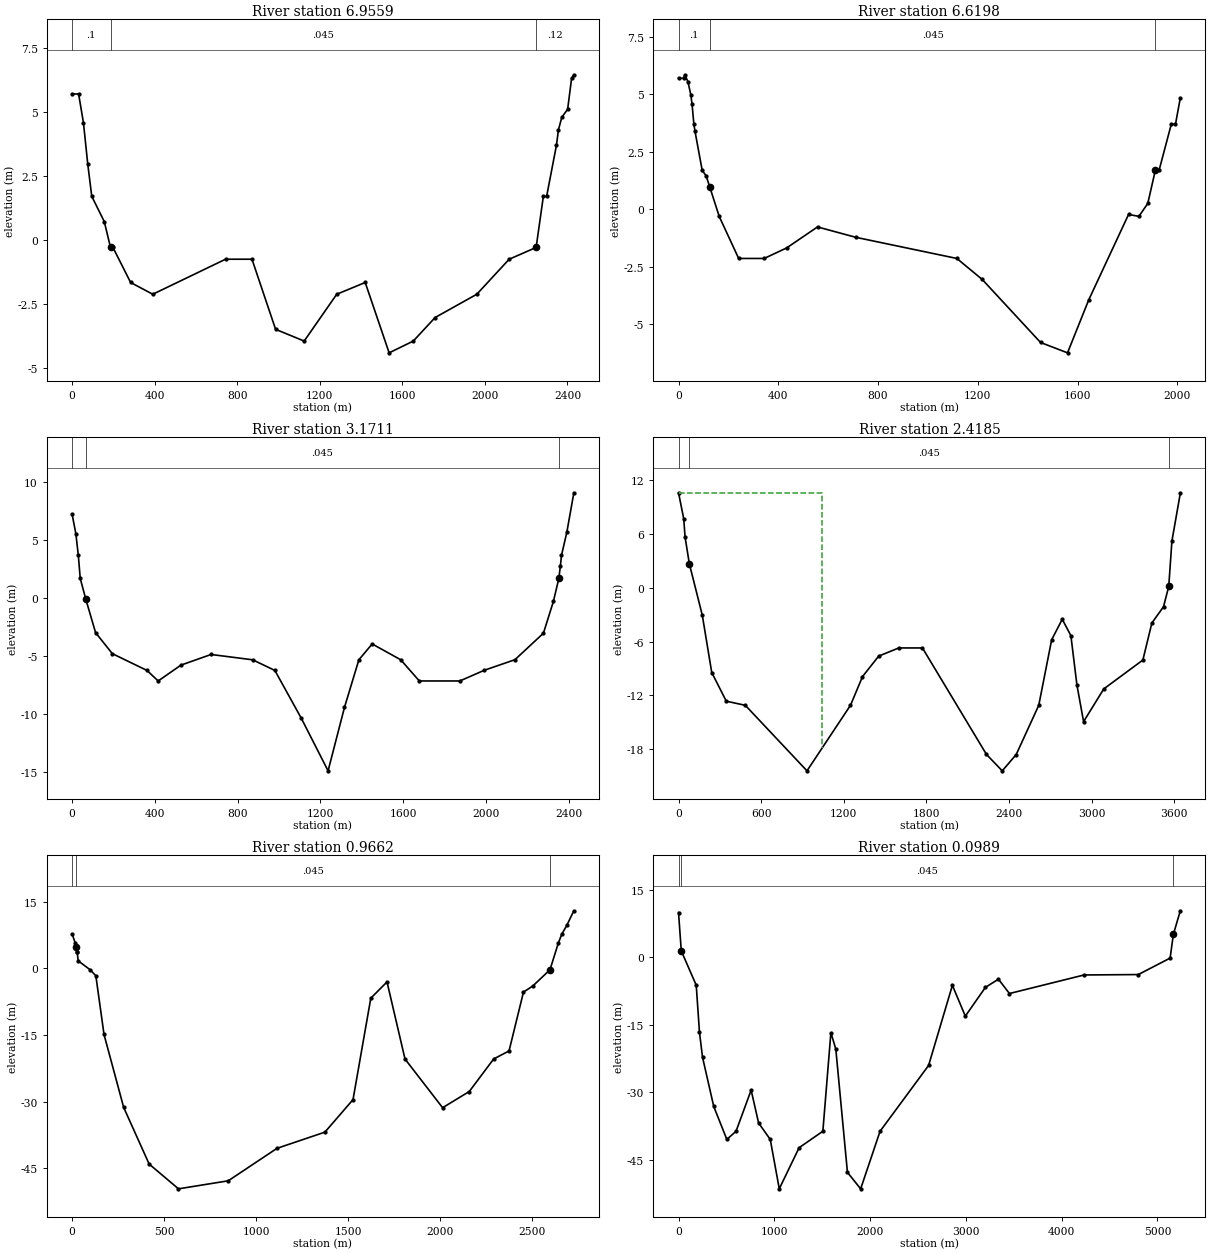
Type RM Length L Ch R = 1 ,6.9559  ,29.88,336.16,697.08
XS GIS Cut Line= 5
     622800.7667     5439428.139     622942.1973    5439356.9893
     623066.2609    5439337.9875     624867.5565    5439681.5371
     625173.0415    5439751.8944
#Sta/Elev= 30
       0   5.698   31.73   5.698   55.36   4.558   75.66   2.978   95.35   1.698
  156.02    .708   186.3   -.302  198.03   -.302  283.75  -1.672  390.98  -2.132
  743.58   -.762  871.59   -.762  985.99  -3.502 1124.49  -3.962 1282.15  -2.132
 1420.21  -1.672 1536.08  -4.422 1653.16  -3.962 1758.73  -3.042 1960.77  -2.132
 2117.71   -.762 2248.27   -.302 2283.28   1.698 2299.17   1.698 2346.82   3.698
  2356.4   4.298 2372.74   4.788 2400.88   5.098  2420.2   6.318 2431.03   6.448
#Mann= 3 , 0 , 0
       0      .1       0   186.3    .045       0 2248.27     .12       0
Bank Sta=186.3,2248.27
XS Rating Curve= 0 ,0
Exp/Cntr=0.3,0.1

Type RM Length L Ch R = 1 ,6.6198  ,4100.58,3448.62,3290.4
BEGIN DESCRIPTION:
Wigwam Point
END DESCRIPTION:
XS GIS Cut Line= 4
     622817.1442     5439429.015     622926.7432    5439383.8938
     622971.1688      5439385.55     624611.4961    5440239.6075
#Sta/Elev= 30
       0   5.698    20.4   5.698   25.28   5.848   37.76   5.548   49.02   4.988
   54.05   4.588   61.57   3.698   65.61   3.418   94.83   1.698  110.61   1.458
  125.11    .978     163   -.302  241.14  -2.132  343.44  -2.132  433.91  -1.672
  557.33   -.762  710.43  -1.212 1116.18  -2.132 1217.71  -3.042 1451.86  -5.782
 1559.95  -6.232 1644.98  -3.932  1804.7   -.222 1846.26   -.302 1881.81    .258
 1912.08   1.698 1927.15   1.698    1976   3.698  1992.9   3.698 2012.33   4.848
#Mann= 3 , 0 , 0
       0      .1       0  125.11    .045       0 1912.08     .12       0
Bank Sta=125.11,1912.08
XS Rating Curve= 0 ,0
Exp/Cntr=0.3,0.1

Type RM Length L Ch R = 1 ,3.1711  ,1686.56,752.56,484.08
BEGIN DESCRIPTION:
Peterview
END DESCRIPTION:
XS GIS Cut Line= 3
     621541.6013    5442763.4222     621610.2179    5442776.2373
      623902.104    5443322.4026
#Sta/Elev= 30
       0   7.268   18.36   5.568   30.18   3.698   39.53   1.698   66.12   -.072
  113.56  -2.982  194.76  -4.802  362.16  -6.252  416.28  -7.162   526.4  -5.792
  671.96  -4.872  873.04  -5.332  980.33  -6.252  1107.5 -10.362 1237.65 -14.932
 1316.85  -9.452 1386.46  -5.332  1450.9  -3.962 1589.02  -5.332 1678.84  -7.162
 1874.72  -7.162 1992.07  -6.242 2141.14  -5.322 2278.77  -3.032 2326.97   -.282
 2353.18   1.698 2360.87   2.808 2366.08   3.698 2391.89   5.698 2425.85   9.108
#Mann= 3 , 0 , 0
       0      .1       0   66.12    .045       0 2353.18     .12       0
Bank Sta=66.12,2353.18
XS Rating Curve= 0 ,0
Exp/Cntr=0.3,0.1

Type RM Length L Ch R = 1 ,2.4185  ,2000.72,1452.32,1476
BEGIN DESCRIPTION:
Peters Arm
END DESCRIPTION:
XS GIS Cut Line= 3
     620293.4317    5443741.0135     620423.0615    5443729.0557
     623935.6074    5443787.8188
#Sta/Elev= 30
       0  10.608   37.79   7.698   47.26   5.698   78.44   2.688  172.36  -3.042
  241.13  -9.442  346.74 -12.642  484.88 -13.102  932.59 -20.412 1248.43 -13.102
 1335.68  -9.902 1453.13  -7.612 1599.28  -6.702 1770.81  -6.702 2235.89 -18.582
 2350.21 -20.412 2451.78 -18.592  2615.4 -13.102 2709.03  -5.792 2785.96  -3.502
  2848.7  -5.332 2892.29 -10.812 2940.83 -14.9223087.569 -11.2723371.329  -8.052
 3436.62  -3.9223521.129  -2.102 3559.18    .1583582.241   5.228 3643.28  10.568
#Mann= 3 , 0 , 0
       0      .1       0   78.44    .045       0 3559.18     .12       0
#XS Ineff= 2 , 0
         1043.37  10.607
Permanent Ineff=
       F       F
Bank Sta=78.44,3559.18
XS Rating Curve= 0 ,0
Exp/Cntr=0.3,0.1

Type RM Length L Ch R = 1 ,0.9662  ,218.7,867.35,3368.7
BEGIN DESCRIPTION:
Botwood
END DESCRIPTION:
XS GIS Cut Line= 3
     621395.0795      5445201.46     621491.9061    5445181.5799
     624116.8066    5445253.2794
#Sta/Elev= 30
       0   7.779   17.43   5.699   21.51   4.739    26.1   3.699   27.44   3.699
   33.38   1.699   97.66   -.291  129.15  -1.661  173.51 -14.881   280.1 -31.291
  418.54 -44.061  577.92 -49.641  848.05 -47.831 1112.65 -40.521 1372.96 -36.871
 1525.54 -29.551 1622.15  -6.701 1710.17  -3.041 1807.93 -20.411 2012.06 -31.371
  2156.9 -27.721 2289.15 -20.401 2372.86 -18.581 2451.13  -5.331 2501.92  -3.961
 2595.18   -.301 2640.26   5.699 2659.15   7.699 2686.44   9.699 2724.76  12.979
#Mann= 3 , 0 , 0
       0      .1       0   21.51    .045       0 2595.18     .12       0
Bank Sta=21.51,2595.18
XS Rating Curve= 0 ,0
Exp/Cntr=0.3,0.1

Type RM Length L Ch R = 1 ,0.0989  ,99.07,98.93,174.17
BEGIN DESCRIPTION:
Mill Point
END DESCRIPTION:
XS GIS Cut Line= 4
     621321.3996    5445350.9679     621353.5718    5445369.5816
     625777.0176    5447903.8337     625825.8527    5447812.4137
#Sta/Elev= 30
       0   9.959   28.56   1.429  184.74  -6.211  218.54 -16.691   250.4 -22.231
  367.65 -33.191  504.33 -40.521  600.51 -38.691  757.96 -29.551  835.88 -36.861
  957.58 -40.521 1051.74 -51.501 1258.79 -42.361 1506.77 -38.701 1590.62 -16.761
 1641.97 -20.421 1763.47 -47.851 1901.34 -51.511 2104.07 -38.701 2610.64 -24.061
 2859.05  -6.241 2994.15 -13.0913203.881  -6.691 3339.87  -4.8713454.689  -8.061
4233.849  -3.931 4799.78  -3.841 5132.14   -.181 5166.14   5.109 5238.79  10.349
#Mann= 3 , 0 , 0
       0      .1       0   28.56    .045       0 5166.14     .12       0
Bank Sta=28.56,5166.14
XS Rating Curve= 0 ,0
Exp/Cntr=0.3,0.1

River Reach=GF1             ,GF1
Reach XY= 30
     600981.8176    5423094.7514     601006.9531    5423112.0816
     601021.2612    5423090.0247     601191.4213     5423221.276
     601402.8768      5423504.19     601392.1876     5423630.767
     601580.7036      5423805.26     601576.4702     5423842.302
     601657.9621     5423905.802      601701.883     5423987.294
     601931.5418     5424211.397     602030.2977     5424236.863
     602156.5042     5424356.719     602187.1959     5424455.409
     602181.3751     5424532.932     602274.9214     5424841.118
     602323.7371     5424915.889     602163.3763     5425057.231
      602141.945     5425104.591     602218.6744     5425153.539
     602422.0512     5425192.204     602491.9013     5425227.129
     602501.4263     5425276.341     602469.6762     5425396.992
     602647.4766     5425557.329     602715.7392     5425546.217
     602789.2936     5425568.177     602814.2967     5425675.334
     602789.2936     5425724.546      602816.678     5425748.359

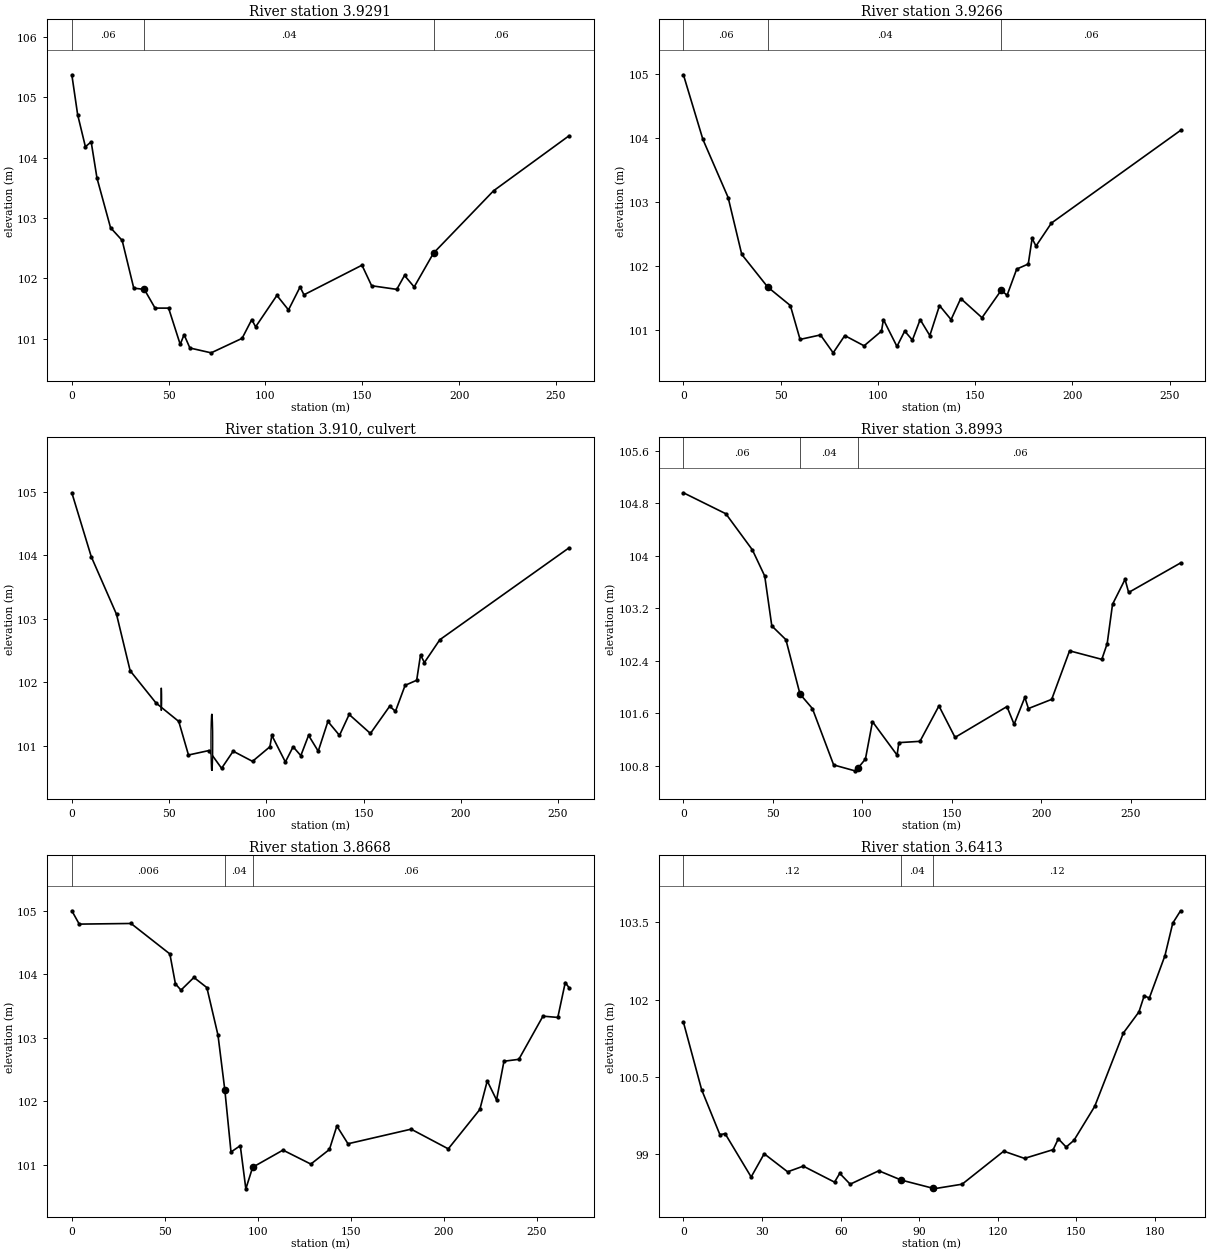
Type RM Length L Ch R = 1 ,3.9291  ,2.57,2.48,2.43
BEGIN DESCRIPTION:
n/a
END DESCRIPTION:
XS GIS Cut Line= 5
     600956.4629    5423125.0161     600994.2984    5423081.0952
     600999.5901    5423072.6285     601041.3944    5422969.9699
     601068.6465    5422896.9448
#Sta/Elev= 30
       0  105.37       3  104.71       7  104.18    9.99  104.26   12.99  103.66
   19.99  102.84   25.99  102.63   31.98  101.84   37.43  101.82   42.98  101.51
   49.97  101.51   55.97  100.91   57.97  101.07   60.97  100.85   71.95  100.77
   87.93  101.01   92.92  101.32   94.92   101.2   105.9  101.72  111.89  101.48
  117.88  101.86  119.88  101.73  149.84  102.22  154.83  101.88  167.81  101.82
  171.81  102.05   176.8  101.86  186.79  102.42  217.77  103.45  256.74  104.36
#Mann= 3 , 0 , 0
       0     .06       0   37.43     .04       0  186.79     .06       0
Bank Sta=37.43,186.79
XS Rating Curve= 0 ,0
Exp/Cntr=0.3,0.1

Type RM Length L Ch R = 1 ,3.9266  ,27.43,27.3,54.33
BEGIN DESCRIPTION:
US of Hardy Avenue Culvert - n/a
END DESCRIPTION:
XS GIS Cut Line= 5
     600955.6691    5423131.3661     600995.6213    5423082.6826
     601003.0296    5423070.7764      601035.838    5423003.8366
     601068.1173    5422904.8823
#Sta/Elev= 30
       0  104.99      10  103.98   22.99  103.07   29.99  102.18   43.32  101.67
   54.98  101.38   59.98  100.85   70.46  100.92      77  100.64   82.96  100.91
    92.9  100.75  101.85  100.98  102.84  101.16   109.8  100.74  113.78  100.98
  117.75  100.84  121.73  101.16   126.7  100.91  131.67  101.38  137.63  101.16
   142.6  101.49  153.53  101.19  163.44  101.62  166.42  101.54  171.37  101.95
  177.32  102.03   179.3  102.43  181.29  102.31  189.22  102.67  255.63  104.12
#Mann= 3 , 0 , 0
       0     .06       0   43.32     .04       0  163.44     .06       0
Bank Sta=43.32,163.44
XS Rating Curve= 0 ,0
Exp/Cntr=0.3,0.1

Type RM Length L Ch R = 2 ,3.910   ,,,
Node Photo=.\Photos\GF-CR-2.JPG
BEGIN DESCRIPTION:
Hardy Avenue Culvert
END DESCRIPTION:
Node Name=GF-CR-2
Bridge Culvert--1,0,-1,-1, 0
Deck Dist Width WeirC Skew NumUp NumDn MinLoCord MaxHiCord MaxSubmerge Is_Ogee
7,19,1.4,0, 278, 278, , , 0.98, 0, 3,3,,
     -15-14.0067-13.0135-12.0202 -11.027-10.0338-9.04055-8.04731-7.05407-6.06083
-5.06759-4.07435-3.08111-2.08787-1.09463-.101392.89184771.8850882.8783293.871569
 4.86481 5.858056.8512917.8445318.8377719.83101210.8242511.7883712.7524913.71661
14.6807215.6448416.6089617.57308 18.537219.5013120.4654321.4295522.3936723.35778
 24.321925.2860226.2501427.2142528.1783729.1770230.1756731.1743232.1729733.17161
34.1702635.1689136.1675637.1662138.16485 39.163540.16215 41.160842.1594543.15136
44.1432745.1351846.12709  47.11948.1109249.1028350.0947451.0866552.0785653.07047
54.06239 55.054356.0462157.0381258.0300359.0219460.0138561.0057761.9976862.96282
63.9279764.8931165.8582566.8233967.7885468.7536869.7188370.6839771.6491272.61426
 73.579474.5445575.5096976.4748377.4399878.4051279.3916580.3781781.3646982.35122
83.3377584.3242785.3107986.2973287.2838488.2703789.2568990.2434291.2299492.21647
93.2029994.1895195.1760496.1625797.1490998.1452699.14142100.1376101.1337102.1299
103.1261104.1222105.1184106.1146107.1107108.1069 109.103110.0992111.0954112.0915
113.0877114.0732115.0588116.0443117.0298118.0154119.0009119.9864 120.972121.9575
 122.943123.9286124.9141125.8996126.8852127.8707128.8562129.8418130.8273131.8129
132.7984133.7839134.7642135.7445136.7248 137.705138.6853139.6656140.6459141.6262
142.6065143.5867 144.567145.5473146.5276147.5079148.4882149.4684150.4487 151.429
152.4093153.3896154.3589155.3282156.2975157.2668158.2361159.2054160.1747 161.144
162.1133163.0826164.0519165.0212165.9905166.9598167.9291168.8984169.8678170.8371
171.8064172.7757 173.745174.7143175.6836176.6529177.6255178.5981179.5707180.5433
181.5159182.4885183.4611184.4337185.4063 186.379187.3515188.3242189.2968190.2694
 191.242192.2146193.1872194.1598195.1324 196.105197.0776198.0502199.0228199.9955
200.9681201.9407202.9133203.8859204.8585205.8311206.8037207.7763208.7489209.7215
210.6941 211.666212.6379213.6098214.5817215.5536216.5255217.4974218.4693219.4412
220.4131 221.385222.3569223.3288224.3007225.2726226.2445227.2164228.1883229.1602
230.1321 231.104232.0759233.0478234.0197234.9916235.9635236.9353237.9072238.8792
 239.851240.8229241.7948242.7495243.7041244.6587245.6133246.5679247.5226248.4772
249.4318250.3864251.3411252.2957253.2503254.2049255.1596256.1142
104.8719104.8607104.8493104.8445104.8225104.8041104.7902104.7666104.7372104.7196
104.6931104.6634104.6436104.6149104.6348104.6807104.6984104.6936 104.686104.6488
104.6149104.5837 104.569104.5458 104.512104.4813 104.475104.4524104.4192104.4061
  104.39104.3773104.3812104.3544104.3518104.3287104.2928104.2778104.2562104.2619
104.2211104.2155104.2118104.1939104.1644104.1517104.1376104.1165104.0927 104.081
104.0654104.0529104.0409104.0066103.9999103.9817103.9744103.9765103.9718103.9561
103.9594103.9378103.9375103.9036103.8956103.8847103.8689103.8438103.8291103.8274
103.7994103.7998103.7991103.7937103.7974103.7911103.7898103.7698103.7572103.7521
103.7464 103.736103.7277103.7113103.6897103.6855103.6807103.6625103.6518103.6424
103.6347103.6217103.6117103.6014103.5894103.5982103.5805  103.58103.5735103.5731
  103.57103.5606103.5428103.5355103.5396 103.513103.5176103.4865103.4845103.4699
103.4546103.4504103.4579103.4585103.4556 103.466 103.439103.4417103.4205103.4135
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      1010.9932411.9864812.9797213.97296 14.966215.9594416.9526817.9459218.93917
19.9324120.9256521.9188922.9121323.9053724.8986125.8918526.8850927.8783328.87157
29.8648130.8580531.8512932.8445333.8377734.8310135.8242536.7883737.7524938.71661
39.6807340.6448441.6089642.5730843.5371944.5013145.4654346.4295547.3936748.35778
 49.321950.2860251.2501452.2142653.1783754.1770255.1756756.1743257.1729758.17161
59.1702660.1689161.1675662.1662163.16485 64.163565.16215 66.160867.1594568.15136
69.1432670.1351871.12709  72.11973.1109274.1028375.0947476.0866577.0785678.07047
79.06239 80.054381.0462182.0381283.0300384.0219485.0138586.0057786.9976887.96282
88.9279689.8931190.8582591.8233992.7885493.7536894.7188395.6839796.6491297.61426
 98.579499.54455100.5097101.4748  102.44103.4051104.3916105.3782106.3647107.3512
108.3377109.3243110.3108111.2973112.2838113.2704114.2569115.2434116.2299117.2165
 118.203119.1895 120.176121.1626122.1491123.1453124.1414125.1376126.1337127.1299
128.1261129.1222130.1184131.1145132.1107133.1069 134.103135.0992136.0954137.0915
138.0877139.0732140.0588141.0443142.0298143.0154144.0009144.9864 145.972146.9575
 147.943148.9286149.9141150.8996151.8852152.8707153.8562154.8418155.8273156.8129
157.7984158.7839159.7642160.7445161.7248 162.705163.6853164.6656165.6459166.6262
167.6065168.5867 169.567170.5473171.5276172.5079173.4882174.4684175.4487 176.429
177.4093178.3896179.3589180.3282181.2975182.2668183.2361184.2054185.1747 186.144
187.1133188.0826189.0519190.0212190.9905191.9598192.9291193.8984194.8678195.8371
196.8064197.7757 198.745199.7143200.6836201.6529202.6255203.5981204.5707205.5433
206.5159207.4885208.4611209.4337210.4063 211.379212.3515213.3242214.2968215.2694
 216.242217.2146218.1872219.1598220.1324 221.105222.0776223.0502224.0228224.9955
225.9681226.9407227.9133228.8859229.8585230.8311231.8037232.7763233.7489234.7215
235.6941 236.666237.6379238.6098239.5817240.5536241.5255242.4974243.4693244.4412
245.4131 246.385247.3569248.3288249.3007250.2726251.2445252.2164253.1883254.1602
255.1321 256.104257.0759258.0478259.0197259.9915260.9634261.9354262.9073263.8792
 264.851265.8229266.7948267.7495268.7041269.6587270.6133 271.568272.5226273.4772
274.4318275.3864276.3411277.2957278.2503279.2049280.1595281.1142
104.8719104.8607104.8493104.8445104.8225104.8041104.7902104.7666104.7372104.7196
104.6931104.6634104.6436104.6149104.6348104.6807104.6984104.6936 104.686104.6488
104.6149104.5837 104.569104.5458 104.512104.4813 104.475104.4524104.4192104.4061
  104.39104.3773104.3812104.3544104.3518104.3287104.2928104.2778104.2562104.2619
104.2211104.2155104.2118104.1939104.1644104.1517104.1376104.1165104.0927 104.081
104.0654104.0529104.0409104.0066103.9999103.9817103.9744103.9765103.9718103.9561
103.9594103.9378103.9375103.9036103.8956103.8847103.8689103.8438103.8291103.8274
103.7994103.7998103.7991103.7937103.7974103.7911103.7898103.7698103.7572103.7521
103.7464 103.736103.7277103.7113103.6897103.6855103.6807103.6625103.6518103.6424
103.6347103.6217103.6117103.6014103.5894103.5982103.5805  103.58103.5735103.5731
  103.57103.5606103.5428103.5355103.5396 103.513103.5176103.4865103.4845103.4699
103.4546103.4504103.4579103.4585103.4556 103.466 103.439103.4417103.4205103.4135
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BR Coef=-1 , 0 , 0 ,, 0 ,,,0.8,-1,,0,
WSPro=,,,, 1 ,,,, 0 ,,,, 0 ,,,,-1 ,-1 ,-1 , 0 , 0 , 0 , 0 , 0
Culvert=1,0.36,,23.8,0.011,0.9,1,2,3,101.551,46,101.717,70,Culvert #1  , 0 ,3.4
      46      70
BC Culvert Barrel=1,1,0
Culvert Bottom n=0.011
Culvert=1,0.9,,23.8,0.011,0.9,1,2,3,100.6,72,100.4,95,Culvert #2  , 0 ,3.4
      72      95
BC Culvert Barrel=1,1,0
Culvert Bottom n=0.011
BC Design=,, 0 ,, 0 ,,,,,,
BC Use User HTab Curves=0
BC User HTab FreeFlow(D)= 0

Type RM Length L Ch R = 1 ,3.8993  ,20.24,32.54,6.2
BEGIN DESCRIPTION:
DS of Hardy Avenue Culvert - n/a
END DESCRIPTION:
XS GIS Cut Line= 6
     600974.0577    5423171.5828     600996.0715    5423126.2971
     601006.6945    5423112.0978     601019.6195    5423092.1482
     601045.3631    5423048.0221     601097.2215    5422923.4031
#Sta/Elev= 30
       0  104.96    23.7  104.64   38.51  104.09   45.42  103.69   49.37  102.93
   57.25  102.72   65.13  101.89   72.05  101.67   83.93  100.81   95.79  100.72
   97.75  100.77  101.68   100.9  105.61  101.47  119.36  100.96  120.35  101.15
  132.14  101.17  142.74  101.71  151.74  101.23  180.73   101.7  184.73  101.43
  190.73  101.84  192.73  101.67  205.73  101.81  215.73  102.55  233.73  102.42
  236.73  102.66  239.72  103.26  246.72  103.64  248.72  103.44  277.72  103.89
#Mann= 3 , 0 , 0
       0     .06       0   65.13     .04       0   97.75     .06       0
Bank Sta=65.13,97.75
XS Rating Curve= 0 ,0
Exp/Cntr=0.3,0.1

Type RM Length L Ch R = 1 ,3.8668  ,227.42,225.5,227.17
BEGIN DESCRIPTION:
n/a
END DESCRIPTION:
XS GIS Cut Line= 3
     600980.0109    5423176.4776     601016.5386    5423112.5871
     601102.2486    5422938.8813
#Sta/Elev= 30
       0     105    3.98  104.79   31.82   104.8   52.71  104.32   55.69  103.85
   58.68  103.75   65.64  103.95    72.6  103.79   78.59  103.04   82.29  102.17
   85.58   101.2   90.57   101.3   93.56  100.62   97.22  100.96  113.53  101.23
  128.51  101.01   138.5  101.24  142.49  101.61  148.48  101.33  182.43  101.56
   202.4  101.25  219.37  101.87  223.36  102.32  228.36  102.02  232.35  102.63
  240.34  102.66  253.32  103.34   261.3  103.32   265.3  103.87   267.3  103.79
#Mann= 3 , 0 , 0
       0    .006       0   82.29     .04       0   97.22     .06       0
Bank Sta=82.29,97.22
XS Rating Curve= 0 ,0
Exp/Cntr=0.3,0.1

Type RM Length L Ch R = 1 ,3.6413  ,344.46,343.04,340.83
BEGIN DESCRIPTION:
n/a
END DESCRIPTION:
XS GIS Cut Line= 3
     601131.0275    5423290.8369     601201.6714    5423228.1305
     601275.0934    5423167.4085
#Sta/Elev= 30
       0  101.56    6.96  100.25   13.92   99.38   15.91    99.4   25.85   98.56
   30.82   99.01   39.77   98.66   45.74   98.77   57.67   98.46   59.66   98.63
   63.64   98.42   74.57   98.68   83.13    98.5   95.33   98.34   95.45   98.33
  106.37   98.42  122.25   99.06  130.19   98.92  141.11   99.09  143.09    99.3
  146.07   99.14  149.05   99.27  156.99   99.93   167.9  101.35  173.86  101.76
  175.84  102.07  177.83  102.03  183.78  102.85  186.76  103.48  189.74  103.72
#Mann= 3 , 0 , 0
       0     .12       0   83.13     .04       0   95.33     .12       0
Bank Sta=83.13,95.33
XS Rating Curve= 0 ,0
Exp/Cntr=0.3,0.1