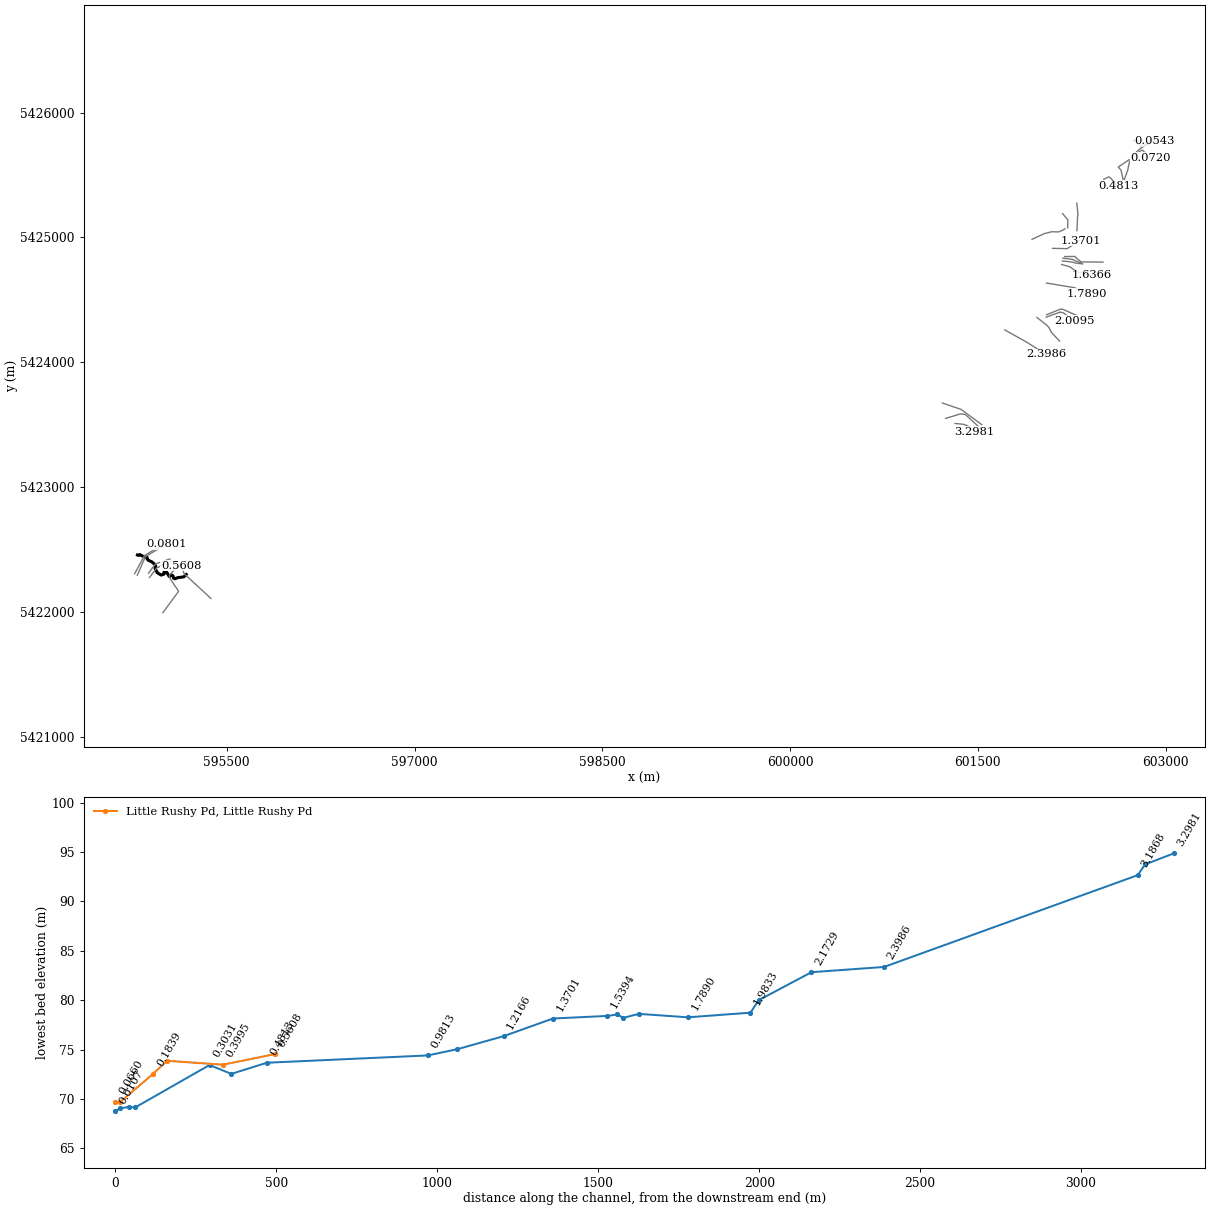
HEC-RAS study Exploits_FMM.prj: Exploits_FMM

--- Exploits_FMM.g01 (geometry) --- (continued)

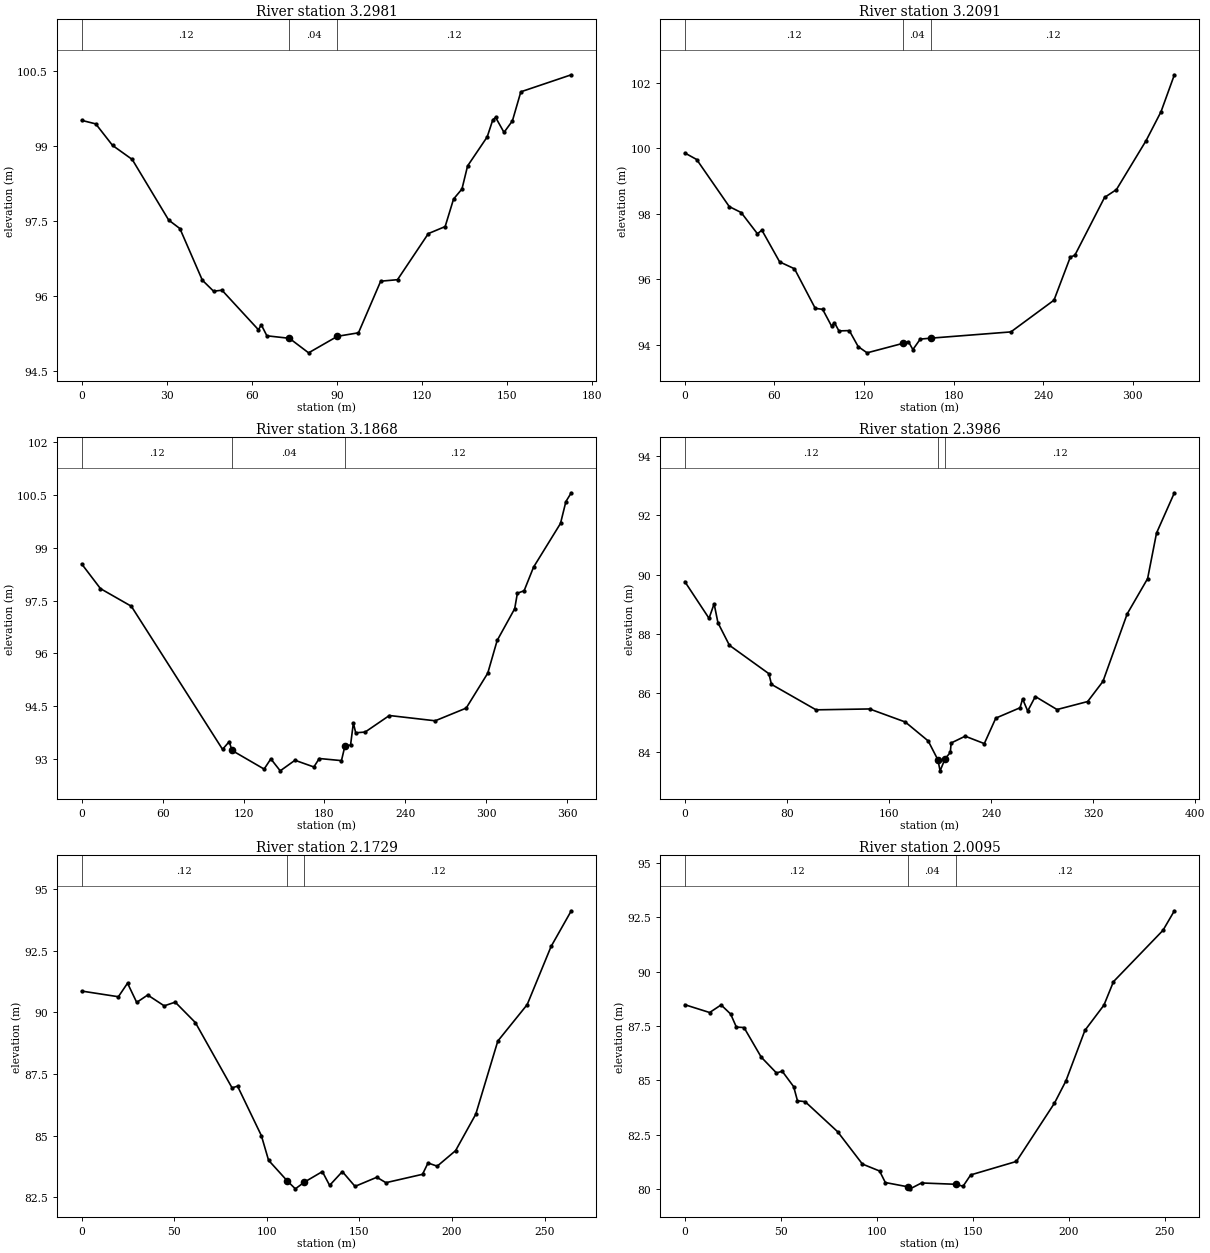
Type RM Length L Ch R = 1 ,3.2981  ,89.71,89.12,88.86
BEGIN DESCRIPTION:
n/a
END DESCRIPTION:
XS GIS Cut Line= 4
     601318.6921    5423511.4098     601388.5422    5423504.0014
     601420.2923    5423491.3014     601471.0924     5423445.793
#Sta/Elev= 30
       0   99.51    4.95   99.44   10.88   99.01   17.81   98.73   30.67   97.52
   34.63   97.35   42.54   96.32    46.5    96.1   49.47   96.12   62.33   95.33
   63.32   95.43    65.3   95.21   73.24   95.16   80.01   94.87   90.17    95.2
    97.6   95.27  105.43    96.3  111.36   96.33  122.23   97.25  128.16   97.39
  131.13   97.94  134.09   98.14  136.07    98.6  142.99   99.18  144.96   99.52
  145.95   99.57  148.92   99.27  151.88    99.5  154.85  100.08  172.64  100.42
#Mann= 3 , 0 , 0
       0     .12       0   73.24     .04       0   90.17     .12       0
Bank Sta=73.24,90.17
XS Rating Curve= 0 ,0
Exp/Cntr=0.3,0.1

Type RM Length L Ch R = 1 ,3.2091  ,25.77,22.25,21.9
BEGIN DESCRIPTION:
n/a
END DESCRIPTION:
XS GIS Cut Line= 4
     601243.5386    5423552.0367     601361.2784    5423587.7555
      601399.643    5423583.7868     601522.0131    5423471.3386
#Sta/Elev= 30
       0   99.86    7.94   99.66   29.77   98.22   37.71   98.04   48.62   97.39
    51.6    97.5    63.5   96.53   73.43   96.32   87.32   95.11   92.28   95.08
   98.23   94.57  100.22   94.67  103.19   94.42  110.14   94.43  116.09   93.94
  122.05   93.75  146.05   94.04  149.74   94.09  152.71   93.85  157.65   94.17
  165.05    94.2  218.33   94.39  247.19   95.36  258.14   96.68  261.12   96.73
  281.03    98.5  288.99   98.74  308.89  100.24  318.84  101.12   327.8  102.25
#Mann= 3 , 0 , 0
       0     .12       0  146.05     .04       0  165.05     .12       0
Bank Sta=146.05,165.05
XS Rating Curve= 0 ,0
Exp/Cntr=0.3,0.1

Type RM Length L Ch R = 1 ,3.1868  ,788.88,788.25,782.61
BEGIN DESCRIPTION:
GF1_19 (SEM 2019)
END DESCRIPTION:
XS GIS Cut Line= 4
601216.5640035985423675.09228309601365.2601035985423624.29218309
601403.3602035995423596.77548309601530.8896035985423502.05448309
#Sta/Elev= 30
       0   98.54   13.92   97.84    36.8   97.34  104.42   93.28   109.4    93.5
  111.39   93.25  135.25   92.72  140.23   93.01  147.19   92.67  158.13   92.97
  172.13   92.78  176.13   93.02  192.59   92.96  195.19   93.38  199.33    93.4
  201.43   94.03  203.13   93.75  210.13   93.77  228.11   94.24  262.08   94.09
  285.06   94.45  301.05   95.44  308.04   96.37  321.03   97.27  323.03   97.71
  328.02   97.78  335.02   98.45     355   99.69  358.99  100.31  362.99  100.56
#Mann= 3 , 0 , 0
       0     .12       0  111.39     .04       0  195.19     .12       0
Bank Sta=111.39,195.19
XS Rating Curve= 0 ,0
Exp/Cntr=0.3,0.1

Type RM Length L Ch R = 1 ,2.3986  ,229.28,225.58,228.32
BEGIN DESCRIPTION:
GF1_18 (SEM 2019)
END DESCRIPTION:
XS GIS Cut Line= 3
601716.0983035985424259.82268309601885.9612035985424164.57248309
602046.2990035985424064.55978309
#Sta/Elev= 30
       0   89.76   18.98   88.52   22.97   89.01   25.97   88.37   34.95   87.61
   65.91   86.65   67.91   86.29  102.87   85.43  144.81   85.46  172.77   85.02
  190.75   84.38  198.38   83.74  200.08   83.37  204.02   83.78  208.08   83.99
  208.74   84.31  219.74   84.54  234.74   84.29  243.74   85.15  262.74    85.5
  264.74    85.8  268.74   85.39  274.73   85.88  291.73   85.44  315.73   85.71
  327.73   86.39  346.72   88.67  362.72   89.86  369.72    91.4  383.72   92.76
#Mann= 3 , 0 , 0
       0     .12       0  198.38     .04       0  204.02     .12       0
Bank Sta=198.38,204.02
XS Rating Curve= 0 ,0
Exp/Cntr=0.3,0.1

Type RM Length L Ch R = 1 ,2.1729  ,157.55,163.55,176.1
BEGIN DESCRIPTION:
n/a
END DESCRIPTION:
XS GIS Cut Line= 5
601972.2142035985424359.66558309602049.4727035985424299.34048309
602066.9352035985424281.34878309602089.6894035985424239.01538309
602153.1896035985424170.75268309
#Sta/Elev= 30
       0   90.87    19.8   90.64   24.75   91.19    29.7   90.41   35.64   90.71
   44.55   90.27    50.5   90.42   61.39   89.59   81.19   86.94   84.16   87.01
   97.03      85  100.91      84  110.92   83.17  115.38   82.84   120.2   83.11
  129.96   83.54  133.88   82.98  140.75   83.54  147.61   82.94  159.38   83.31
  164.29   83.09  184.05   83.43  187.02   83.89  191.98   83.76   201.9   84.39
  212.81   85.87  224.71   88.84  240.58   90.32  253.48   92.68  264.39   94.13
#Mann= 3 , 0 , 0
       0     .12       0  110.92     .04       0   120.2     .12       0
Bank Sta=110.92,120.2
XS Rating Curve= 0 ,0
Exp/Cntr=0.3,0.1

Type RM Length L Ch R = 1 ,2.0095  ,24.74,26.14,26.45
BEGIN DESCRIPTION:
n/a
END DESCRIPTION:
XS GIS Cut Line= 4
     602046.7011    5424361.9236     602157.8263    5424402.6695
     602183.7555    5424396.8486     602272.1265    5424331.2318
#Sta/Elev= 30
       0   88.48   12.93   88.12    18.9   88.47   23.87   88.05   26.85   87.45
   30.83   87.43   39.78   86.07   47.74   85.34   50.73   85.42   56.69   84.71
   58.68   84.06   62.66   84.02   79.57   82.64    92.5   81.15  101.45   80.83
  104.44    80.3  116.37    80.1  117.37   80.01  123.28   80.28     141   80.22
  144.93   80.13   148.9   80.65   172.7   81.27  192.53   83.95  198.48   84.97
   208.4    87.3  218.31   88.46  223.27   89.54  249.05    91.9     255    92.8
#Mann= 3 , 0 , 0
       0     .12       0  116.37     .04       0     141     .12       0
Bank Sta=116.37,141
XS Rating Curve= 0 ,0
Exp/Cntr=0.3,0.1

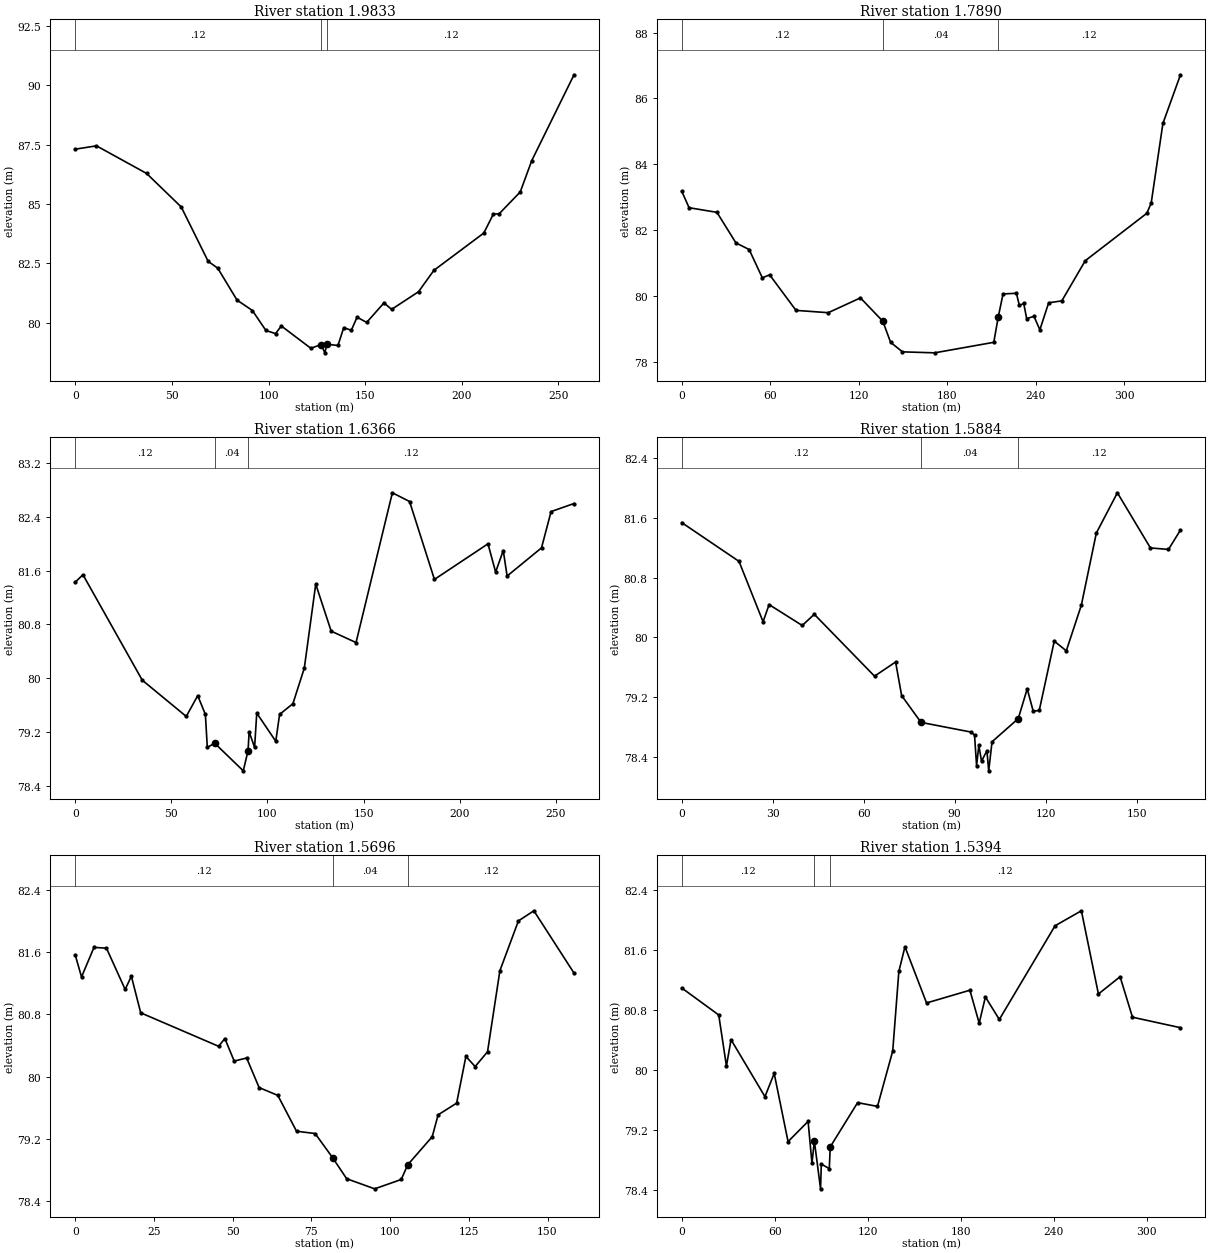
Type RM Length L Ch R = 1 ,1.9833  ,196.52,194.32,204.49
BEGIN DESCRIPTION:
GF1_17 (SEM 2019)
END DESCRIPTION:
XS GIS Cut Line= 4
602050.0032035985424381.53118309602161.6575035985424427.03968309
602181.7659035995424424.39378309602288.6578035985424376.23958309
#Sta/Elev= 30
       0   87.31   10.96   87.45   36.87   86.29   54.81   84.88   68.76   82.59
   73.74    82.3    83.7   80.96   91.67   80.52   98.65   79.68  103.63   79.55
  106.62   79.87  121.93   78.93  127.21   79.09  129.13   78.74  130.22    79.1
  135.93   79.05  138.92    79.8  142.84   79.69  145.82   80.24  150.79   80.02
  159.73   80.84  163.71   80.57  177.62   81.31  185.56   82.21   211.4   83.78
  216.36   84.58  219.34   84.59  230.27   85.51  236.23   86.83  258.09   90.44
#Mann= 3 , 0 , 0
       0     .12       0  127.21     .04       0  130.22     .12       0
Bank Sta=127.21,130.22
XS Rating Curve= 0 ,0
Exp/Cntr=0.3,0.1

Type RM Length L Ch R = 1 ,1.7890  ,160.61,152.38,148.04
BEGIN DESCRIPTION:
GF1_16 (SEM 2019)
END DESCRIPTION:
XS GIS Cut Line= 4
602048.4157035985424635.53168309602173.8284035995424614.36498309
602273.3119035985424597.96078309602372.7955035995424550.33568309
#Sta/Elev= 30
       0   83.18    4.97   82.68   23.85   82.54   36.76   81.61   45.71   81.41
   54.65   80.55   59.62   80.64    77.5   79.56   99.36   79.49  121.22   79.94
  136.38   79.23  141.67   78.59  149.72    78.3  171.56   78.27  211.67   78.59
  214.65   79.35  217.94   80.06  227.01   80.08  229.01   79.71  231.99   79.77
  233.97   79.31  238.94   79.38  242.92   78.97  248.88   79.79  257.82   79.85
  273.72   81.07  315.45   82.51  318.44   82.82  326.38   85.24  338.31   86.72
#Mann= 3 , 0 , 0
       0     .12       0  136.38     .04       0  214.65     .12       0
Bank Sta=136.38,214.65
XS Rating Curve= 0 ,0
Exp/Cntr=0.3,0.1

Type RM Length L Ch R = 1 ,1.6366  ,43.58,48.19,58.16
BEGIN DESCRIPTION:
GF1_15 (SEM 2019)
END DESCRIPTION:
XS GIS Cut Line= 4
  602170.1242036 5424783.6986831  602236.2702036 5424765.1777831
  602286.1261036 5424727.5507831  602411.5063036 5424695.7575831
#Sta/Elev= 30
       0   81.43    3.98   81.54   34.84   79.97   57.74   79.43   63.71   79.74
   67.69   79.46   68.69   78.97   72.58   79.03   87.41   78.62   89.89   78.92
   90.46    79.2    93.3   78.97   94.42   79.48  104.32   79.06   106.3   79.46
  113.23   79.62  119.17   80.15  125.11    81.4  133.14    80.7  146.08   80.53
  164.98   82.76  173.94   82.63  186.87   81.47  214.73      82  218.71   81.58
  222.69    81.9  224.68   81.52  242.59   81.94  247.56   82.48   259.5    82.6
#Mann= 3 , 0 , 0
       0     .12       0   72.58     .04       0   89.89     .12       0
Bank Sta=72.58,89.89
XS Rating Curve= 0 ,0
Exp/Cntr=0.3,0.1

Type RM Length L Ch R = 1 ,1.5884  ,20.68,18.79,24.06
BEGIN DESCRIPTION:
GF1_14 (SEM 2019)
END DESCRIPTION:
XS GIS Cut Line= 4
  602175.9451036 5424812.2737831  602248.9702036 5424803.8070831
  602288.1286036 5424793.7528831  602338.3996036 5424788.4611831
#Sta/Elev= 30
       0   81.54   18.88   81.02   26.82   80.21   28.81   80.44   39.74   80.16
   43.71   80.31   63.58   79.48   70.53   79.67   72.52   79.22   78.91   78.86
   95.42   78.73   96.56   78.69   97.24   78.28   97.98   78.55   98.88   78.34
  100.65   78.48  101.24   78.21  102.34    78.6  110.98   78.91  113.94   79.31
  115.92   79.01  117.91   79.02  122.86   79.95  126.83   79.82  131.78   80.43
  136.74    81.4  143.68   81.94  154.58    81.2  160.53   81.18  164.49   81.44
#Mann= 3 , 0 , 0
       0     .12       0   78.91     .04       0  110.98     .12       0
Bank Sta=78.91,110.98
XS Rating Curve= 0 ,0
Exp/Cntr=0.3,0.1

Type RM Length L Ch R = 1 ,1.5696  ,27.89,30.27,27.14
BEGIN DESCRIPTION:
GF1_13 (SEM 2019)
END DESCRIPTION:
XS GIS Cut Line= 4
602179.1201035995424834.49878309602253.7327035985424824.97378309
602290.2453035985424808.56958309602330.9912035995424794.28208309
#Sta/Elev= 30
       0   81.56    1.98   81.28    5.94   81.66     9.9   81.65   15.84   81.12
   17.81   81.29   20.78   80.82   45.53   80.39   47.51   80.49   50.48    80.2
   54.43   80.24   58.39   79.86   64.33   79.76   70.27    79.3   76.19   79.27
   81.74   78.96    86.2   78.69    95.1   78.56  103.53   78.68  105.62   78.87
  113.39   79.23  115.25   79.51  121.13   79.66  124.08   80.26  127.02   80.13
  130.95   80.32  134.87   81.36  140.76      82  145.67   82.13  158.42   81.33
#Mann= 3 , 0 , 0
       0     .12       0   81.74     .04       0  105.62     .12       0
Bank Sta=81.74,105.62
XS Rating Curve= 0 ,0
Exp/Cntr=0.3,0.1

Type RM Length L Ch R = 1 ,1.5394  ,138.74,169.31,170.38
BEGIN DESCRIPTION:
GF1_12 (SEM 2019)
END DESCRIPTION:
XS GIS Cut Line= 5
  602194.4659036 5424847.1987831  602275.9578036 5424848.2571831
  602286.0120036 5424835.5570831  602326.6012036 5424804.2987831
  602500.4065036 5424802.9140831
#Sta/Elev= 30
       0   81.09   23.85   80.73   28.82   80.05    31.8    80.4   53.67   79.64
   59.63   79.95   68.58   79.04    81.5   79.31   84.01   78.75   85.53   79.05
   89.55   78.41   90.03   78.74   95.18   78.68   95.79   78.97  113.45   79.56
  126.26   79.51  136.11   80.25  140.05   81.31  143.99   81.64  157.92   80.89
  185.89   81.06  191.88   80.62  195.88   80.97  204.87   80.67  240.83   81.92
  257.81   82.12   268.8   81.01  282.78   81.24  290.77    80.7  321.74   80.56
#Mann= 3 , 0 , 0
       0     .12       0   85.53     .04       0   95.79     .12       0
Bank Sta=85.53,95.79
XS Rating Curve= 0 ,0
Exp/Cntr=0.3,0.1

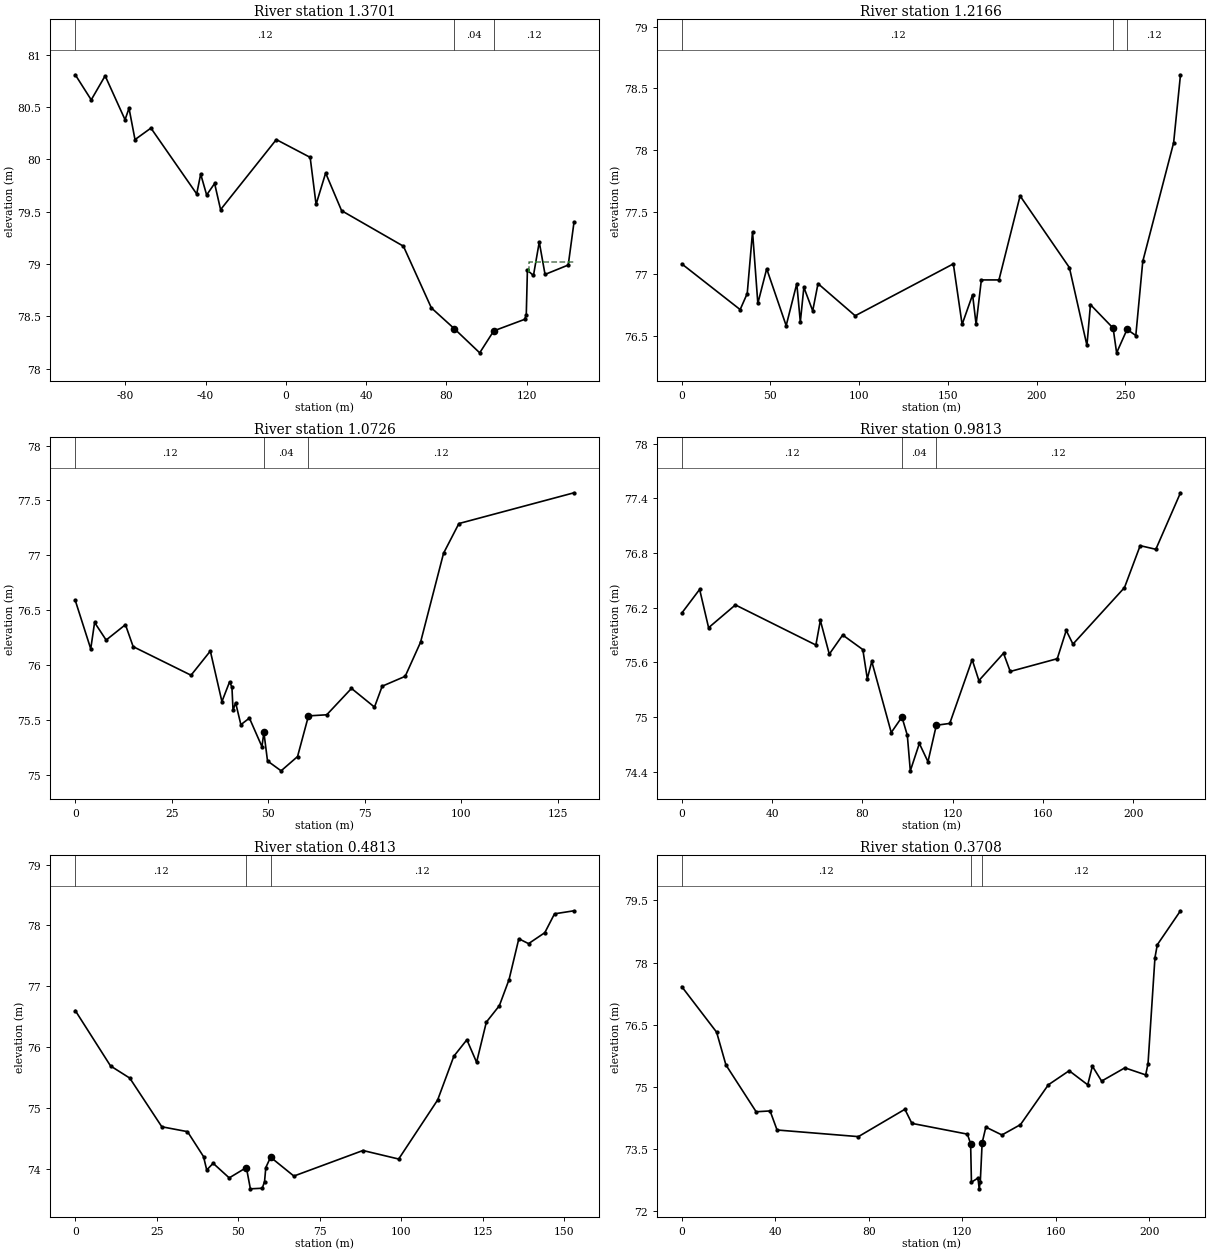
Type RM Length L Ch R = 1 ,1.3701  ,153.77,153.44,149.82
BEGIN DESCRIPTION:
GF1_11 (SEM 2019)
END DESCRIPTION:
XS GIS Cut Line= 5
  602096.9066036 5424912.9505831  602213.9409036 5424910.5263831
  602269.6078036 5424946.1531831  602298.1706036 5424974.7159831
  602323.1549036 5424973.2267831
#Sta/Elev= 30
  -104.9   80.81  -96.96   80.57  -90.02    80.8   -80.1   80.38  -78.12   80.49
  -75.14   80.19   -67.2    80.3  -44.39   79.67   -42.4   79.86  -39.43   79.66
  -35.46   79.77  -32.48   79.52-4.70999   80.19   12.16   80.02   15.11   79.57
   19.88   79.87   27.83   79.51   58.65   79.17   72.57   78.58   84.06   78.38
   96.67   78.15  103.66   78.36  119.01   78.47  119.87   78.51  120.44   78.94
  123.46   78.89  126.35   79.21  129.23    78.9  140.79   78.99  143.67    79.4
#Mann= 3 , 0 , 0
  -104.9     .12       0   84.06     .04       0  103.66     .12       0
#XS Ineff= 2 , 0
           10.32   80.02  121.44           79.02
Permanent Ineff=
       F       F
Bank Sta=84.06,103.66
XS Rating Curve= 0 ,0
Exp/Cntr=0.3,0.1

Type RM Length L Ch R = 1 ,1.2166  ,180.02,144.02,124.68
BEGIN DESCRIPTION:
n/a
END DESCRIPTION:
XS GIS Cut Line= 6
601933.3938035985424985.57888309602031.2898035985425030.55808309
602089.4983035985425045.77168309602147.0453035985425044.44878309
602177.4724035985425058.33938309602196.6547035985425069.58428309
#Sta/Elev= 30
       0   77.08   32.92   76.71   36.91   76.84    39.9   77.34   42.89   76.76
   47.88   77.04   58.86   76.58   64.84   76.92   66.84   76.61   68.83   76.89
   73.82    76.7   76.81   76.92   97.76   76.66   153.1   77.08  158.04   76.59
  163.95   76.83  165.93   76.59  168.89   76.95  178.82   76.95  190.72   77.63
  218.51   77.05  228.41   76.42  230.38   76.75  243.17   76.56  245.14   76.36
  251.04   76.55  255.96    76.5  259.88    77.1  277.28   78.06  281.14   78.61
#Mann= 3 , 0 , 0
       0     .12       0  243.17     .04       0  251.04     .12       0
Bank Sta=243.17,251.04
XS Rating Curve= 0 ,0
Exp/Cntr=0.3,0.1

Type RM Length L Ch R = 1 ,1.0726  ,100.5,91.29,82.52
BEGIN DESCRIPTION:
GF1_10 (SEM 2019)
END DESCRIPTION:
XS GIS Cut Line= 4
602178.0617035985425190.62868309602206.1076035985425156.76188309
602219.8660035985425141.41608309602217.7493035985425076.85758309
#Sta/Elev= 30
       0   76.59       4   76.15       5   76.39    7.99   76.23   12.99   76.37
   14.99   76.17   29.98   75.91   34.98   76.13   37.98   75.67   39.97   75.85
   40.58    75.8   40.86   75.59   41.53   75.66   42.89   75.46    45.1   75.52
   48.35   75.26   48.85   75.39   49.79   75.13   53.31   75.04   57.57   75.17
    60.4   75.54   65.13   75.55   71.54   75.79    77.5   75.62   79.49   75.81
   85.45    75.9   89.43   76.21   95.39   77.02   99.36   77.29  129.18   77.57
#Mann= 3 , 0 , 0
       0     .12       0   48.85     .04       0    60.4     .12       0
Bank Sta=48.85,60.4
XS Rating Curve= 0 ,0
Exp/Cntr=0.3,0.1

Type RM Length L Ch R = 1 ,0.9813  ,516.79,500.01,626.47
BEGIN DESCRIPTION:
GF1_09 (SEM 2019)
END DESCRIPTION:
XS GIS Cut Line= 4
602291.3036035985425275.29548309602300.2995035985425181.63278309
602297.1245035995425165.22858309602292.3620035985425055.16168309
#Sta/Elev= 30
       0   76.14    7.92    76.4   11.89   75.98   23.77   76.23   59.43   75.79
   61.41   76.06   65.37   75.69   71.31    75.9   80.23   75.74   82.21   75.42
   84.19   75.61   92.82   74.83   97.56      75   99.94    74.8  101.27   74.41
  105.27   74.71  109.09   74.51  112.79   74.91  118.74   74.93  128.67   75.63
  131.65    75.4  142.56    75.7  145.54    75.5  166.38   75.64  170.35   75.95
  173.33    75.8  196.16   76.42  203.11   76.88  210.05   76.84  220.97   77.46
#Mann= 3 , 0 , 0
       0     .12       0   97.56     .04       0  112.79     .12       0
Bank Sta=97.56,112.79
XS Rating Curve= 0 ,0
Exp/Cntr=0.3,0.1

Type RM Length L Ch R = 1 ,0.4813  ,108.47,110.49,106.95
BEGIN DESCRIPTION:
GF1_07 (SEM 2019)
END DESCRIPTION:
XS GIS Cut Line= 4
602506.6749035995425466.85418309602549.0083035995425485.37508309
602565.4125035985425470.55838309602622.5626035985425408.11658309
#Sta/Elev= 30
       0    76.6   10.81   75.69   16.71   75.49   26.54   74.69   34.41   74.61
   39.33    74.2   40.31   73.98   42.28   74.09   47.21   73.85   52.47   74.02
    53.7   73.67   57.34   73.68   58.05   73.79   58.43   74.02    59.9   74.19
   67.04   73.88   88.23    74.3   99.18   74.16  111.13   75.13  116.11   75.85
   120.1   76.12  123.08   75.75  126.07   76.41  130.06   76.68  133.04   77.11
  136.03   77.78  139.02    77.7     144   77.88  146.98   78.19  152.96   78.24
#Mann= 3 , 0 , 0
       0     .12       0   52.47     .04       0    59.9     .12       0
Bank Sta=52.47,59.9
XS Rating Curve= 0 ,0
Exp/Cntr=0.3,0.1

Type RM Length L Ch R = 1 ,0.3708  ,107.47,67.71,54.38
BEGIN DESCRIPTION:
GF1_06 (SEM 2019)
END DESCRIPTION:
XS GIS Cut Line= 4
602708.4932035985425622.58498309602622.3843035995425563.49018309
602644.2585035985425539.35018309602660.6627035985425464.73758309
#Sta/Elev= 30
       0   77.42   14.92   76.32    18.9   75.53   31.83    74.4    37.8   74.42
   40.78   73.96   75.59    73.8   95.48   74.46   98.47   74.12  122.22   73.86
  123.61   73.63  123.96    72.7  126.75    72.8  127.28   72.54  127.75   72.71
  128.54   73.65  130.12   74.03  137.01   73.84  144.95   74.09  156.86   75.05
  165.78   75.39  173.72   75.05  175.71    75.5  179.67   75.14   189.6   75.46
  198.52   75.29  199.52   75.56  202.49   78.12  203.49   78.43  213.41   79.25
#Mann= 3 , 0 , 0
       0     .12       0  123.61     .04       0  128.54     .12       0
Bank Sta=123.61,128.54
XS Rating Curve= 0 ,0
Exp/Cntr=0.3,0.1

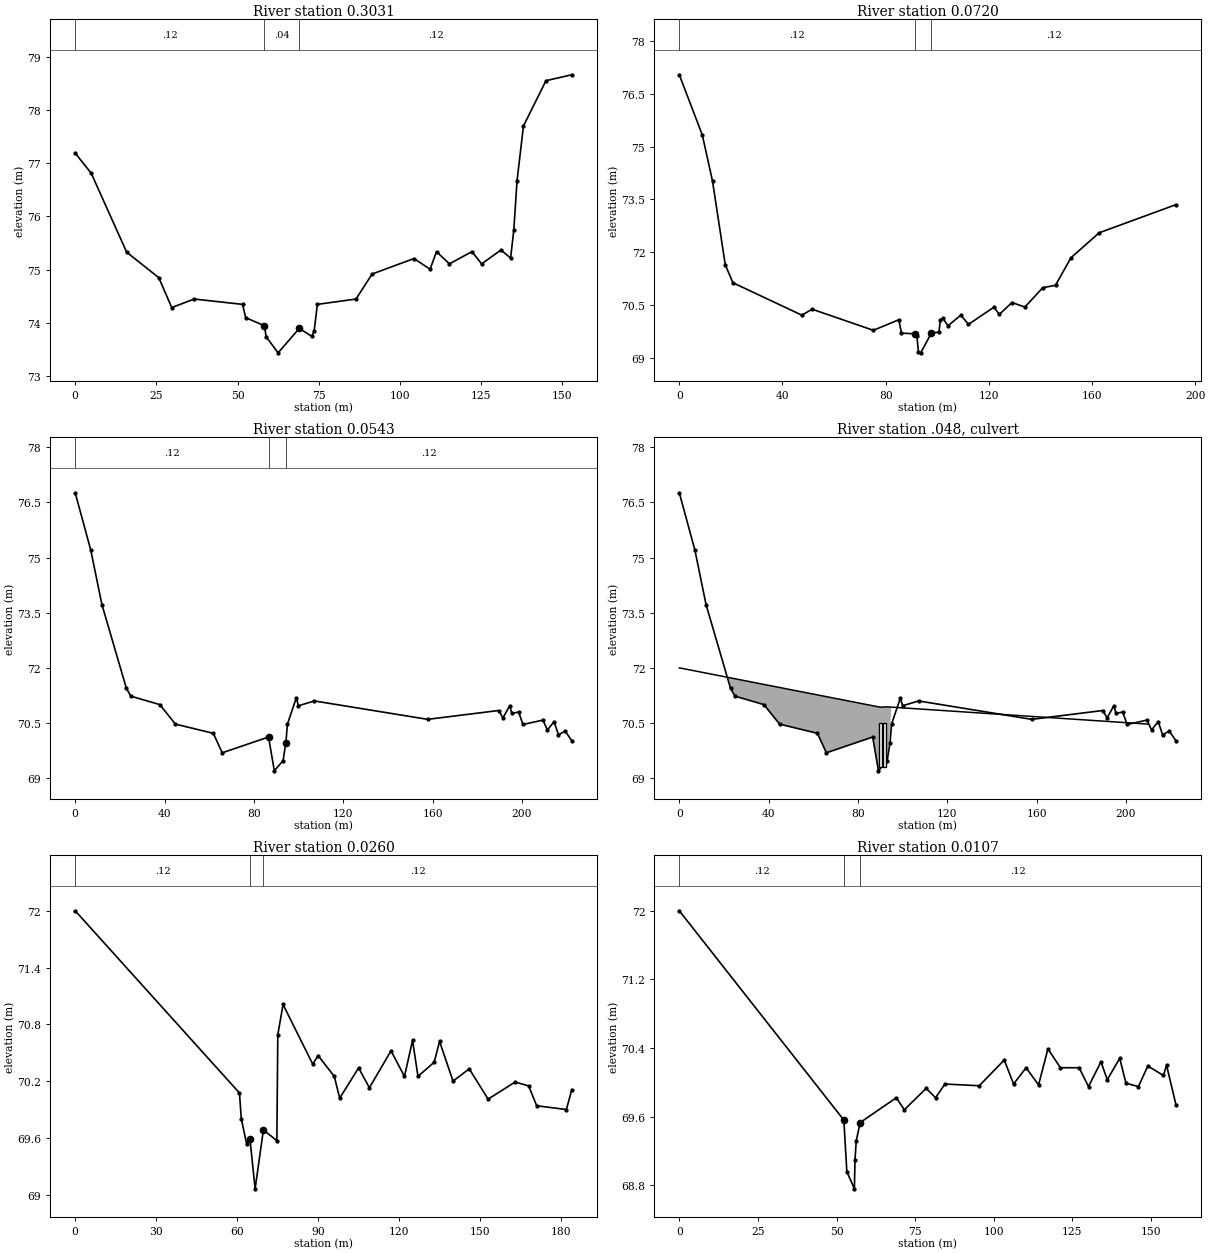
Type RM Length L Ch R = 1 ,0.3031  ,207.25,231.07,240.4
BEGIN DESCRIPTION:
GF1_05 (SEM 2019)
END DESCRIPTION:
XS GIS Cut Line= 4
602713.0503035985425610.25868309602701.9378035985425558.92938309
602697.7045035995425538.29188309602670.7169035985425463.67918309
#Sta/Elev= 30
       0   77.19    4.95   76.81   15.85   75.33   25.76   74.85   29.73   74.29
   36.66   74.45   51.53   74.35   52.52    74.1   58.24   73.95   58.84   73.74
   62.49   73.44   69.03    73.9   72.84   73.75   73.59   73.85   74.58   74.35
   86.48   74.45   91.44   74.92  104.33   75.21  109.29   75.01  111.27   75.34
  115.24   75.11  122.18   75.34  125.16   75.11  131.11   75.37  134.09   75.22
  135.08   75.75  136.07   76.67  138.05    77.7  144.99   78.55  152.93   78.66
#Mann= 3 , 0 , 0
       0     .12       0   58.24     .04       0   69.03     .12       0
Bank Sta=58.24,69.03
XS Rating Curve= 0 ,0
Exp/Cntr=0.3,0.1

Type RM Length L Ch R = 1 ,0.0720  ,14.8,17.78,18.13
BEGIN DESCRIPTION:
GF1_04 (SEM 2019)
END DESCRIPTION:
XS GIS Cut Line= 4
602731.0420035985425643.06708309602799.3047035985425692.27968309
602814.6505035985425699.68798309602881.3257035995425637.24618309
#Sta/Elev= 30
       0   77.04    8.91   75.33   12.87   74.02   17.82   71.64   20.79   71.13
   47.52   70.21   51.48   70.38   75.24   69.78    85.1   70.08   86.14    69.7
   91.38   69.68   92.08   69.63   92.73   69.16   93.62   69.14    97.7    69.7
  100.66   69.73  101.19   70.07  102.19   70.12  104.17   69.91  109.14   70.21
  112.12   69.95  122.04   70.44  124.03   70.23  128.99   70.57  133.96   70.44
  140.91   70.99  145.87   71.06  151.83   71.84  162.75   72.55  192.54   73.35
#Mann= 3 , 0 , 0
       0     .12       0   91.38     .04       0    97.7     .12       0
Bank Sta=91.38,97.7
XS Rating Curve= 0 ,0
Exp/Cntr=0.3,0.1

Type RM Length L Ch R = 1 ,0.0543  ,38.77,28.3,15.31
BEGIN DESCRIPTION:
US of GF1 Stream Newfoundland T'Railway Culvert - GF1_03 (SEM 2019)
END DESCRIPTION:
XS GIS Cut Line= 5
     602726.8087    5425648.8879      602790.838    5425704.4505
     602801.8666    5425713.8767     602806.3161    5425717.6797
     602911.2289    5425769.9066
#Sta/Elev= 30
       0   76.76    6.98    75.2   11.97   73.72   22.94   71.44   24.93   71.23
    37.9      71   44.88   70.47   61.84   70.22   65.83   69.69   86.58   70.12
   89.15    69.2   93.08   69.48   94.34   69.97   95.02   70.47   98.98   71.18
   99.97   70.97  107.12    71.1  157.78    70.6  189.56   70.84  191.54   70.64
  194.52   70.97  195.52   70.76   198.5    70.8  200.48   70.46  209.42   70.58
  211.41   70.31  214.39   70.54  216.37   70.18  219.35   70.28  222.33   70.02
#Mann= 3 , 0 , 0
       0     .12       0   86.58     .04       0   94.34     .12       0
Bank Sta=86.58,94.34
XS Rating Curve= 0 ,0
Exp/Cntr=0.3,0.1

Type RM Length L Ch R = 2 ,.048    ,,,
Node Photo=.\Photos\GF-CR-1.JPG
BEGIN DESCRIPTION:
GF1 Stream Newfoundland T'Railway Culvert
END DESCRIPTION:
Node Name=GF-CR-1
Bridge Culvert--1,0,-1,-1, 0
Deck Dist Width WeirC Skew NumUp NumDn MinLoCord MaxHiCord MaxSubmerge Is_Ogee
2,5.8,1.4,0, 6, 6, , , 0.98, 0, 3,3,,
       0      90      90    92.8    92.8     210
      72   70.93   70.93  70.941  70.941   70.47
       0      66      66    68.8    68.8     185
      72  70.915  70.915   70.89   70.89   70.47
BR Coef=-1 , 0 , 0 ,, 0 ,,,0.8,-1,,0,
WSPro=,,,, 1 ,,,, 0 ,,,, 0 ,,,,-1 ,-1 ,-1 , 0 , 0 , 0 , 0 , 0
Multiple Barrel Culv=2,1.2,1.2,5.8,0.012,0.9,1,8,2,69.303,69.282, 2,Culvert #1  , 0 ,3
      90      66      92      68
BC Culvert Barrel=1,2,0
BC Culvert Barrel=2,1,0
Culvert Bottom n=0.012
BC Design=,, 0 ,, 0 ,,,,,,
BC Use User HTab Curves=0
BC User HTab FreeFlow(D)= 0

Type RM Length L Ch R = 1 ,0.0260  ,15.64,15.24,15.63
BEGIN DESCRIPTION:
DS of GF1 Stream Newfoundland T'Railway Culvert - GF1_02 (SEM 2019) - NOTE: Have LiDAR data on right bank and survey data in center. Left overbank is dummy
END DESCRIPTION:
XS GIS Cut Line= 4
     602750.0921    5425774.3007     602797.7172    5425730.9089
     602807.2897    5425722.7278     602899.3226    5425777.0503
#Sta/Elev= 30
       0      72    60.8  70.07561.48038  69.80363.43005  69.54164.68524  69.591
 66.6055  69.06269.66666  69.68574.64279  69.571      75   70.69   76.94   71.01
   87.92   70.38   89.92   70.47   95.91   70.25   97.91   70.02   104.9   70.34
   108.9   70.13  116.89   70.52  121.88   70.25  124.88   70.63  126.88   70.25
  132.87    70.4  134.87   70.62  139.86    70.2  145.85   70.33  152.84   70.01
  162.83   70.19  167.83   70.15  170.82   69.94  181.81    69.9  183.81   70.11
#Mann= 3 , 0 , 0
       0     .12       064.68524     .04       069.66666     .12       0
Bank Sta=64.68524,69.66666
XS Rating Curve= 0 ,0
Exp/Cntr=0.3,0.1

Type RM Length L Ch R = 1 ,0.0107  ,9.95,10.71,11.65
BEGIN DESCRIPTION:
GF1_01 (SEM 2019) - NOTE: Copied Lidar from right abutment and survey data. rest is placeholder
END DESCRIPTION:
XS GIS Cut Line= 4
     602770.2004    5425783.8257     602807.2422    5425742.5506
     602819.2646    5425733.1388     602885.8288    5425788.1629
#Sta/Elev= 30
       0      72   52.32   69.5653.27589  68.95955.67977  68.75855.86996  69.094
56.26749  69.31957.51548  69.531      69   69.82   71.56   69.6878.50999   69.93
   81.49   69.82   84.47   69.98   95.39   69.96  103.33   70.26  106.31   69.98
  110.28   70.17  114.25   69.97  117.23   70.39   121.2   70.17  127.15   70.17
  130.13   69.95   134.1   70.24  136.09   70.03  140.06   70.28  142.04   69.99
  146.01   69.95  148.99   70.19  153.95   70.08  154.95    70.2  157.93   69.74
#Mann= 3 , 0 , 0
       0     .12       0   52.32     .04       057.51548     .12       0
Bank Sta=52.32,57.51548
XS Rating Curve= 0 ,0
Exp/Cntr=0.3,0.1

River Reach=Little Rushy Pd ,Little Rushy Pd
Reach XY= 30
595175.9906035985422302.16688309595157.1522035985422283.32848309
595106.5638035985422276.76678309595086.2437035985422267.66508309
595074.3904035995422272.74518309595071.0037035985422289.67848309
595066.1354035995422295.39348309595052.8003035985422297.29848309
595046.0270035985422286.71518309595039.4653035985422287.56188309
595021.0238035985422319.65588309595001.7092035985422323.09548309
594997.7228035985422319.77228309595000.7391035995422309.13598309
594995.3415035985422303.42098309594975.4978035995422297.70598309
594941.6839035985422318.02598309594940.7314035995422328.18608309
594929.5872035995422340.99188309594927.7880035985422351.99858309
594932.8812035985422369.05098309594923.9515035985422383.93388309
594899.4775035995422404.50528309594872.2254035995422416.41148309
594864.2879035995422425.93658309594863.7587035985422438.23968309
594825.1278035995422449.94548309594806.3440035985422461.65538309
594795.0992035995422455.30538309 594786.283260675422458.26882177
Reach Downstream Storage Area=Rushy Pond

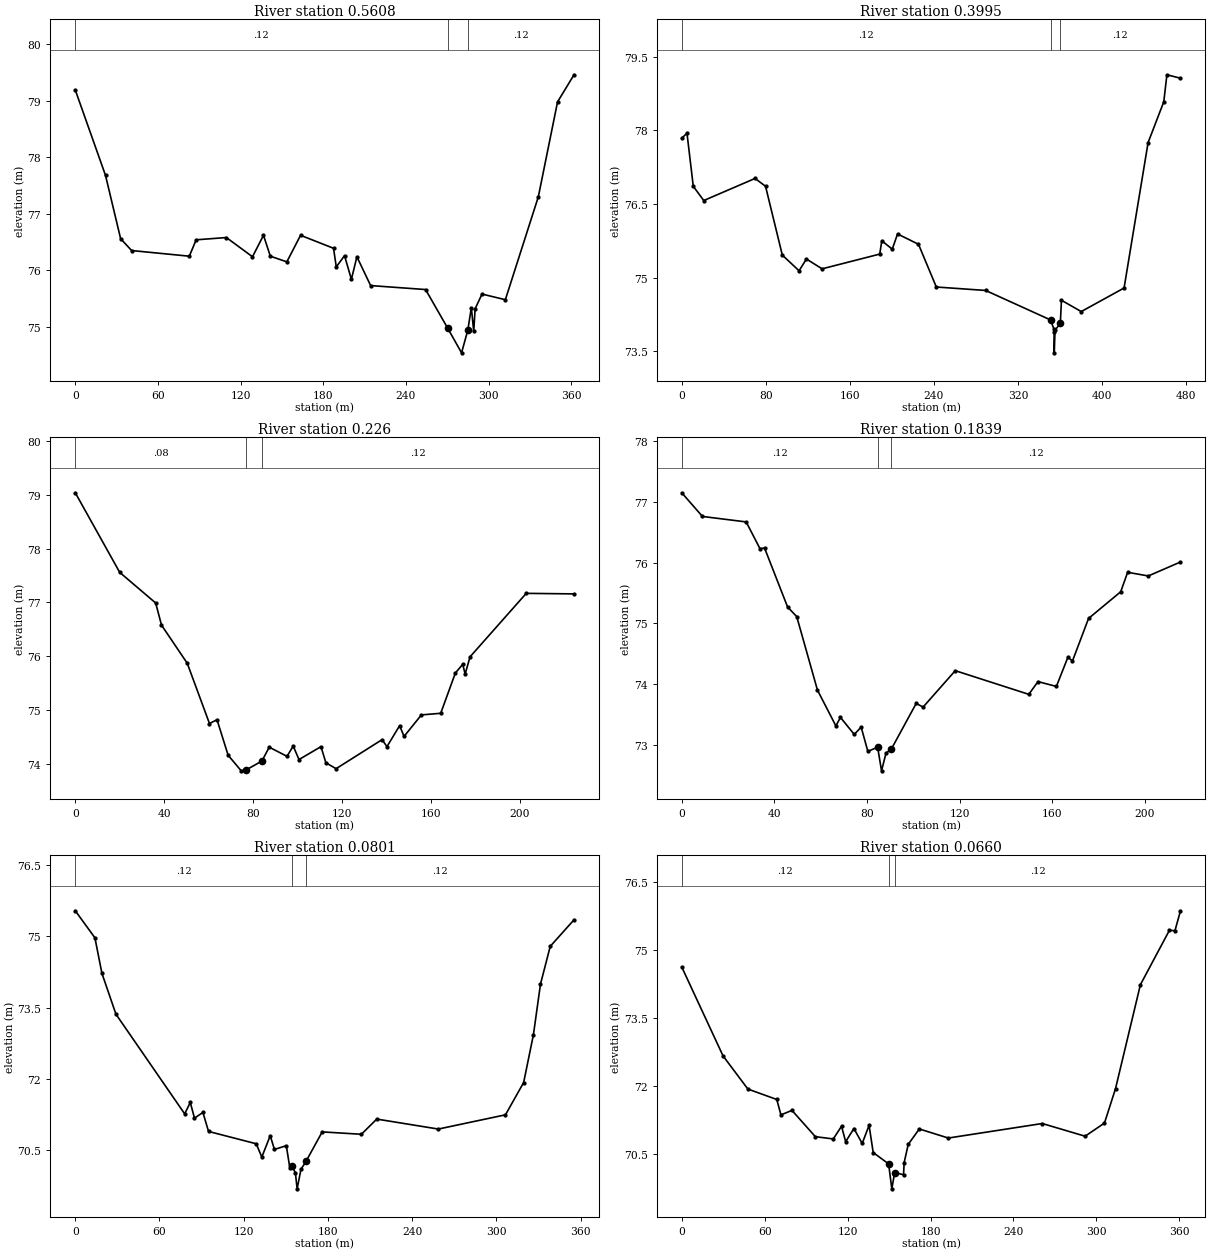
Type RM Length L Ch R = 1 ,0.5608  ,160.32,161.28,155.49
BEGIN DESCRIPTION:
LRP07 (SEM 2019)
END DESCRIPTION:
XS GIS Cut Line= 4
595373.9371035985422110.05558309595182.1138035985422287.32678309
595159.6242035985422307.17058309595134.4888035985422373.31658309
#Sta/Elev= 30
       0   79.19   21.93   77.68    32.9   76.56   40.87   76.35   82.74   76.25
   87.73   76.54  109.66   76.58   128.6   76.24  136.58   76.62  141.56   76.25
  153.53   76.15  163.49   76.62  187.42   76.39  189.41   76.06   195.4   76.26
  200.38   75.84  204.37   76.24  214.34   75.73  254.21   75.66  270.18   74.98
  280.33   74.54  284.85   74.94  287.43   75.34  289.15   74.92  290.18   75.32
  295.17   75.58  312.11   75.48  336.03    77.3  349.99   78.98  361.94   79.46
#Mann= 3 , 0 , 0
       0     .12       0  270.18     .04       0  284.85     .12       0
Bank Sta=270.18,284.85
XS Rating Curve= 0 ,0
Exp/Cntr=0.3,0.1

Type RM Length L Ch R = 1 ,0.3995  ,173,173,173
BEGIN DESCRIPTION:
LRP06 (SEM 2019)
END DESCRIPTION:
XS GIS Cut Line= 5
594989.3454035995421996.40498309595115.1941035995422167.44038309
595043.2073035995422275.42048309595041.8844035985422296.58718309
595118.6137035985422377.28528309
#Sta/Elev= 30
       0   77.84    4.98   77.94   10.97   76.86   20.94   76.57   69.79   77.02
   79.75   76.86   95.71   75.46  111.66   75.14  118.63   75.38  133.59   75.18
  188.42   75.48  190.41   75.75  200.38   75.58  205.37   75.89  225.32   75.68
  242.29   74.81  289.21   74.74  350.98   74.14  354.12   73.96  354.37    73.9
  354.52   73.47   355.3   73.93  360.31   74.07   361.4   74.54  380.23   74.31
     421   74.79  443.86   77.75  458.78   78.58  461.76   79.13  474.68   79.06
#Mann= 3 , 0 , 0
       0     .12       0  350.98     .04       0  360.31     .12       0
Bank Sta=350.98,360.31
XS Rating Curve= 0 ,0
Exp/Cntr=0.3,0.1

Type RM Length L Ch R = 1 ,0.226   ,42.6,42.6,42.6
BEGIN DESCRIPTION:
n/a
END DESCRIPTION:
XS GIS Cut Line= 3
594882.7866417055422278.58441989 594939.796320915422354.00347467
595057.9726350965422408.04389975
#Sta/Elev= 30
       0   79.04      20   77.56    36.2   76.99    38.8   76.58    50.4   75.87
    60.4   74.75    63.8   74.82    68.8   74.16    74.7   73.87      77   73.89
      8474.05143    87.3   74.31    95.3   74.14    98.1   74.33   100.7   74.08
   110.6   74.32   112.8   74.02   117.4   73.91   138.1   74.45   140.3   74.32
     146   74.71     148   74.51   155.8   74.91   164.5   74.94   171.1   75.69
   174.4   75.85   175.5   75.67   177.7   75.99     203   77.17   224.5   77.16
#Mann= 3 , 0 , 0
       0     .08       0      77     .04       0      84     .12       0
Bank Sta=77,84
XS Rating Curve= 0 ,0
Exp/Cntr(USF)=0,0
Exp/Cntr=0.3,0.1

Type RM Length L Ch R = 1 ,0.1839  ,102.2,103.8,104.94
BEGIN DESCRIPTION:
LRP05 (SEM 2019)
END DESCRIPTION:
XS GIS Cut Line= 4
594873.8736035985422312.46228309594920.1758035985422373.31658309
594932.0821035985422387.86868309595045.8532035985422426.23328309
#Sta/Elev= 30
       0   77.15    8.94   76.76   27.81   76.67   33.76   76.23   35.75   76.24
   45.68   75.27   49.65   75.11   58.59    73.9   66.54   73.31   68.52   73.45
   74.48   73.17   77.46   73.29   80.36   72.89   84.57   72.96   86.26   72.57
   88.18   72.86   90.51   72.93  101.22   73.68   104.2   73.62  118.09   74.22
  149.84   73.83  153.81   74.04  161.75   73.96  166.71   74.44   168.7   74.38
  175.64   75.08  189.53   75.52  192.51   75.84  201.44   75.78  215.33   76.01
#Mann= 3 , 0 , 0
       0     .12       0   84.57     .04       0   90.51     .12       0
Bank Sta=84.57,90.51
XS Rating Curve= 0 ,0
Exp/Cntr=0.3,0.1

Type RM Length L Ch R = 1 ,0.0801  ,13.64,14.13,14.32
BEGIN DESCRIPTION:
LRP04 (SEM 2019)
END DESCRIPTION:
XS GIS Cut Line= 4
594785.2381035985422296.58718309594843.7892035985422431.31518309
594855.1663035985422449.04228309595016.7489035995422543.97318309
#Sta/Elev= 30
       0   75.54   13.99   74.97   18.99   74.22   28.98   73.36   77.95   71.26
   81.94    71.5   84.94   71.17   90.94   71.29   94.94   70.89  128.91   70.63
  132.91   70.35  138.91    70.8   141.9   70.51  150.37   70.59  152.88   70.12
  154.16   70.17  156.82   70.02  158.08   69.68   160.8   70.09  164.42   70.26
  175.94   70.88  203.85   70.83  214.82   71.15  258.68   70.94  306.53   71.24
  319.48   71.92  326.46   72.93  331.45   73.99  338.42   74.79  355.37   75.35
#Mann= 3 , 0 , 0
       0     .12       0  154.16     .04       0  164.42     .12       0
Bank Sta=154.16,164.42
XS Rating Curve= 0 ,0
Exp/Cntr=0.3,0.1

Type RM Length L Ch R = 1 ,0.0660  ,26.18,26.64,26.68
BEGIN DESCRIPTION:
US of Little Rushy Pond Brook Unnamed Road Culvert - LRP03 (SEM 2019)
END DESCRIPTION:
XS GIS Cut Line= 4
594764.0713035995422308.49348309594831.6183035985422433.96098309
594841.1433035985422451.95268309595008.8114035995422557.20228309
#Sta/Elev= 30
       0   74.63   29.89   72.67   47.83   71.94   68.76   71.71   71.75   71.37
   79.72   71.47   96.66   70.89  109.61   70.84  115.59   71.12  118.58   70.78
  124.56   71.07  130.54   70.74  135.52   71.14  138.51   70.54  149.66   70.29
  151.97   69.74  154.06    70.1  160.45   70.05  160.91   70.32  163.85   70.72
  171.85   71.06  192.85   70.86  260.83   71.18  291.83    70.9  305.83   71.19
  313.83   71.95  331.82   74.24  352.82   75.44  356.82   75.43  360.82   75.87
#Mann= 3 , 0 , 0
       0     .12       0  149.66     .04       0  154.06     .12       0
Bank Sta=149.66,154.06
XS Rating Curve= 0 ,0
Exp/Cntr=0.3,0.1