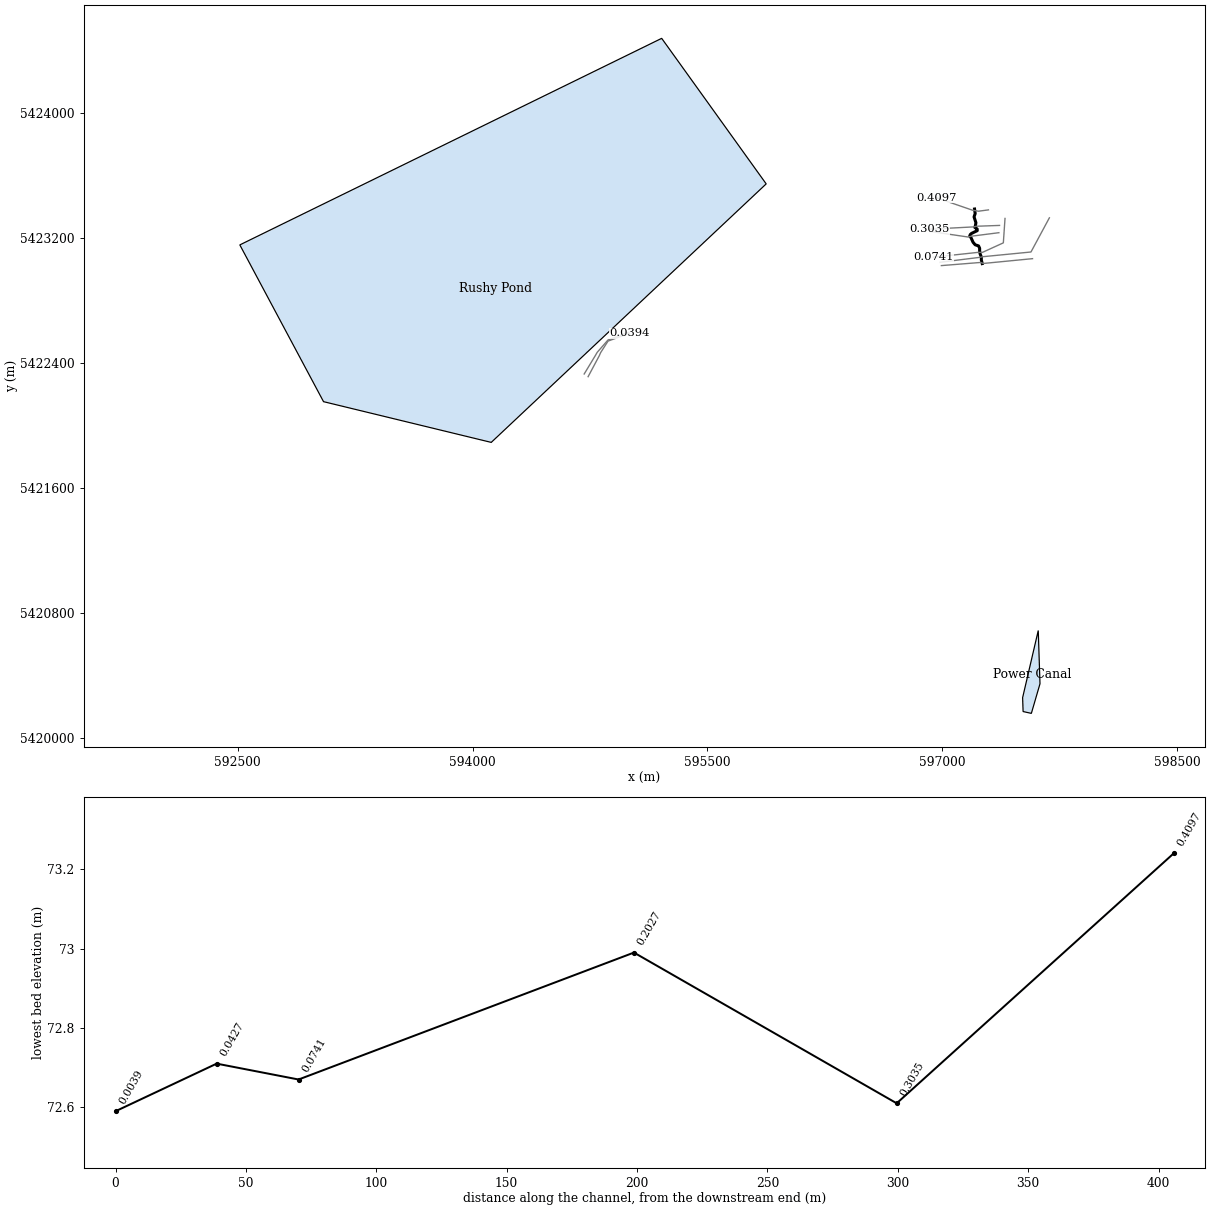
HEC-RAS study Exploits_FMM.prj: Exploits_FMM

--- Exploits_FMM.g01 (geometry) --- (continued)

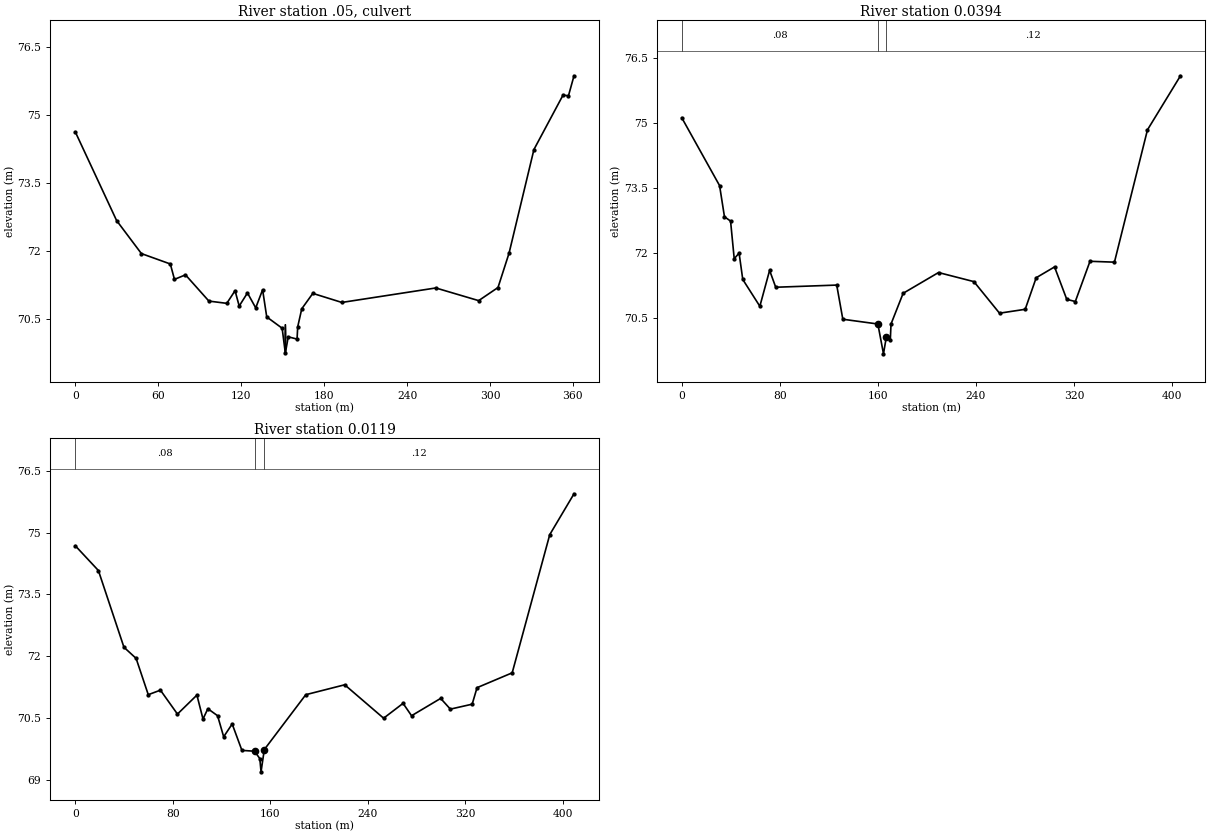
Type RM Length L Ch R = 2 ,.05     ,,,
Node Photo=.\Photos\LRP-CR-1.JPG
BEGIN DESCRIPTION:
Little Rushy Pond Brook Unnamed Road Culvert
END DESCRIPTION:
Node Name=LRP-CR-1
Bridge Culvert--1,0,-1,-1, 0
Deck Dist Width WeirC Skew NumUp NumDn MinLoCord MaxHiCord MaxSubmerge Is_Ogee
4,16,1.4,0, 392, 392, , , 0.98, 0, 3,3,,
      -8-7.00244-6.00488-5.00732-4.00976-3.01221-2.01465-1.01709   -.019.9780214
1.9755792.9731373.9706954.9682535.9658116.9633697.9609278.9584859.956043 10.9536
11.9511612.9487213.9462714.9438315.9413916.9389517.9365118.9340619.9316220.92918
21.92674 22.924323.9218524.9194125.9169726.9145327.9120928.90964 29.907230.90476
31.9023232.8998833.8974334.8949935.8925536.8901137.8876638.8852239.8827840.88034
 41.877942.8754543.8730144.8705745.8681346.8656847.86324 48.860849.8583650.85592
51.8534852.8510353.8485954.8461555.8437156.8412757.8388358.8363859.83394 60.8315
61.8290662.8266163.8241764.8217365.8192966.81685 67.814468.8119669.8095270.80708
71.8046372.7974473.7902574.7830575.7758676.7686777.7614778.7542879.7470980.73989
 81.732782.7255183.7183284.7111285.7039386.6967387.6895488.6823489.6751590.66796
91.6607792.6535793.6463894.6391895.6319996.62479 97.617698.6104199.60322 100.596
101.5888102.5816103.5744104.5672105.5601106.5529107.5457108.5385109.5313110.5241
111.5169112.5097113.5025114.4953115.4881116.4809117.4737118.4665119.4593120.4521
 121.445122.4378123.4306124.4234125.4162 126.409127.4018128.3946129.3874130.3802
 131.373132.3658133.3586134.3514135.3443136.3371137.3299138.3227139.3155140.3083
141.3011142.2939143.2867144.2795145.2723146.2651147.2579148.2507149.2435150.2363
151.2292 152.222153.2148154.2076155.2004156.1932 157.186158.1788159.1716160.1644
161.1572  162.15163.1428164.1356165.1284166.1212167.1141168.1069169.0997170.0925
171.0853172.0781173.0709174.0637175.0565176.0493177.0421178.0349179.0277180.0037
180.9797181.9557182.9317183.9077184.8838185.8598186.8358187.8118188.7878189.7638
190.7398191.7158192.6918193.6678194.6438195.6198196.5958197.5718198.5478199.5238
200.4998201.4758202.4518203.4278204.4038205.3798206.3558207.3318208.2942209.2567
210.2191211.1815212.1439213.1063214.0687215.0311215.9935 216.956217.9184218.8808
219.8432220.8056 221.768222.7304223.6929224.6553225.6177226.5801227.5425228.5049
229.4673230.4297231.4202232.4107233.4012234.3916235.3821236.3726237.3631238.3535
 239.344240.3345 241.325242.3154243.3059244.2964245.2868246.2773247.2678248.2583
249.2487250.2392251.2297252.2202253.2106254.2011255.1916 256.182257.1725 258.163
259.1535260.1439261.1344262.1249263.1154264.1058265.0963266.0868267.0772268.0677
269.0582270.0487271.0391272.0296273.0201274.0106 275.001275.9915 276.982277.9724
278.9624279.9524280.9423281.9323282.9222283.9122284.9021285.8921 286.882 287.872
 288.862289.8519290.8419291.8318292.8218293.8117294.8017295.7917296.7816297.7715
298.7615299.7515300.7414301.7314302.7213303.7113304.7012305.6912306.6812307.6711
308.6611 309.651 310.641311.6309312.6209313.6108314.6008315.5908316.5807317.5707
318.5606319.5506320.5405321.5305322.5204323.5104324.5087 325.507326.5053327.5037
 328.502329.5003330.4986331.4969332.4952333.4936334.4919335.4902336.4885337.4868
338.4852339.4835340.4818341.4801342.4784343.4767344.4751345.4734346.4717  347.47
348.4683349.4666 350.465351.4633352.4616353.4599354.4582355.4565356.4549357.4532
358.4515359.4498360.4482361.4464362.4448363.4431364.4414365.4397 366.438367.4364
368.4347 369.433370.4313371.4296372.4279373.4263374.4246375.4229376.4212377.4195
378.4178379.4162
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       5   5.998   6.995   7.993    8.99   9.988  10.985  11.983   12.98  13.978
  14.976  15.973  16.971  17.968  18.966  19.963  20.961  21.958  22.956  23.954
  24.951  25.949  26.946  27.944  28.941  29.939  30.937  31.934  32.932  33.929
  34.927  35.924  36.922  37.919  38.917  39.915  40.912   41.91  42.907  43.905
  44.902    45.9  46.897  47.895  48.893   49.89  50.888  51.885  52.883   53.88
  54.878  55.875  56.873  57.871  58.868  59.866  60.863  61.861  62.858  63.856
  64.853  65.851  66.849  67.846  68.844  69.841  70.839  71.836  72.834  73.832
  74.829  75.827  76.824  77.822  78.819  79.817  80.814  81.812   82.81  83.807
  84.805  85.797   86.79  87.783  88.776  89.769  90.761  91.754  92.747   93.74
  94.733  95.726  96.718  97.711  98.704  99.697  100.69 101.682 102.675 103.668
 104.661 105.654 106.646 107.639 108.632 109.625 110.618  111.61 112.603 113.596
 114.589 115.582 116.574 117.567  118.56 119.553 120.546 121.539 122.531 123.524
 124.517  125.51 126.503 127.495 128.488 129.481 130.474 131.467 132.459 133.452
 134.445 135.438 136.431 137.423 138.416 139.409 140.402 141.395 142.387  143.38
 144.373 145.366 146.359 147.351 148.344 149.337  150.33 151.323 152.316 153.308
 154.301 155.294 156.287  157.28 158.272 159.265 160.258 161.251 162.244 163.236
 164.229 165.222 166.215 167.208   168.2 169.193 170.186 171.179 172.172 173.164
 174.157  175.15 176.143 177.136 178.128 179.121 180.114 181.107   182.1 183.093
 184.085 185.078 186.071 187.064 188.057 189.049 190.042 191.035 192.028 193.004
  193.98 194.956 195.932 196.908 197.884  198.86 199.836 200.812 201.788 202.764
  203.74 204.716 205.692 206.668 207.644  208.62 209.596 210.572 211.548 212.524
   213.5 214.476 215.452 216.428 217.404  218.38 219.356 220.332 221.294 222.257
 223.219 224.182 225.144 226.106 227.069 228.031 228.994 229.956 230.918 231.881
 232.843 233.806 234.768  235.73 236.693 237.655 238.618  239.58 240.543 241.505
 242.467  243.43  244.42 245.411 246.401 247.392 248.382 249.373 250.363 251.354
 252.344 253.335 254.325 255.315 256.306 257.296 258.287 259.277 260.268 261.258
 262.249 263.239  264.23  265.22 266.211 267.201 268.192 269.182 270.173 271.163
 272.154 273.144 274.134 275.125 276.115 277.106 278.096 279.087 280.077 281.068
 282.058 283.049 284.039  285.03  286.02 287.011 288.001 288.992 289.982 290.972
 291.962 292.952 293.942 294.932 295.922 296.912 297.902 298.892 299.882 300.872
 301.862 302.852 303.842 304.832 305.822 306.812 307.802 308.792 309.782 310.772
 311.762 312.752 313.741 314.731 315.721 316.711 317.701 318.691 319.681 320.671
 321.661 322.651 323.641 324.631 325.621 326.611 327.601 328.591 329.581 330.571
 331.561 332.551 333.541 334.531  335.52  336.51 337.509 338.507 339.505 340.504
 341.502   342.5 343.499 344.497 345.495 346.494 347.492  348.49 349.489 350.487
 351.485 352.484 353.482  354.48 355.478 356.477 357.475 358.473 359.472  360.47
 361.468 362.467 363.465 364.463 365.462  366.46 367.458 368.457 369.455 370.453
 371.452  372.45 373.448 374.446 375.445 376.443 377.441  378.44 379.438 380.436
 381.435 382.433 383.431  384.43 385.428 386.426 387.425 388.423 389.421  390.42
 391.418 392.416
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BR Coef=-1 , 0 , 0 ,, 0 ,,,0.8,-1,,0,
WSPro=,,,, 1 ,,,, 0 ,,,, 0 ,,,,-1 ,-1 ,-1 , 0 , 0 , 0 , 0 , 0
Culvert=1,0.65,,21.8,0.024,0.9,1,2,3,69.724,152,69.456,164,Culvert #1  , 0 ,2
     152     164
BC Culvert Barrel=1,1,0
Culvert Bottom n=0.024
BC Design=,, 0 ,, 0 ,,,,,,
BC Use User HTab Curves=0
BC User HTab FreeFlow(D)= 0

Type RM Length L Ch R = 1 ,0.0394  ,25.17,27.52,26.24
BEGIN DESCRIPTION:
DS of Little Rushy Pond Brook Unnamed Road Culvert - LRP02 (SEM 2019)
END DESCRIPTION:
XS GIS Cut Line= 5
  594737.6130036 5422311.1393831  594809.1287036 5422445.6026831
  594817.5954036 5422465.1818831  594864.8597036 5422538.9313831
  595001.7819036 5422588.5408831
#Sta/Elev= 30
       0   75.12   30.86   73.55   34.84   72.83   39.82   72.73    42.8   71.86
   46.78   71.99   49.77   71.38   63.71   70.76   71.67   71.59   76.65    71.2
  126.42   71.25   131.4   70.46  159.98   70.35  164.57   69.66   166.9   70.05
  170.14   69.98  170.72   70.35   180.6   71.06  209.46   71.54  238.33   71.33
  259.23    70.6  280.18   70.69  289.15   71.42  304.12   71.67  314.09   70.92
  321.07   70.87  333.04    71.8  352.99   71.78  379.93   74.84  406.86   76.09
#Mann= 3 , 0 , 0
       0     .08       0  159.98     .04       0   166.9     .12       0
Bank Sta=159.98,166.9
XS Rating Curve= 0 ,0
Exp/Cntr=0.3,0.1

Type RM Length L Ch R = 1 ,0.0119  ,10.95,11.86,12.51
BEGIN DESCRIPTION:
LRP01 (SEM 2019)
END DESCRIPTION:
XS GIS Cut Line= 5
  594712.4775036 5422328.3372831  594785.2381036 5422448.7229831
  594795.3703036 5422466.5047831  594864.8597036 5422546.2074831
  594998.2281036 5422595.5669831
#Sta/Elev= 30
       0   74.68   18.95   74.08   39.91   72.22   49.88   71.95   59.86   71.07
   69.83   71.18    83.8    70.6   99.76   71.06  104.75   70.48  108.74   70.73
  116.72   70.56  121.71   70.05  128.69   70.36  136.68   69.72  147.04    69.7
  151.37   69.52  152.36    69.2  155.04   69.74  189.06   71.07  220.99   71.31
  252.91    70.5  268.86   70.86  275.82   70.56  299.69   70.98  307.65   70.72
  325.55   70.84  329.53   71.24  358.37    71.6  389.19   74.95  409.08   75.94
#Mann= 3 , 0 , 0
       0     .08       0  147.04     .04       0  155.04     .12       0
Bank Sta=147.04,155.04
XS Rating Curve= 0 ,0
Exp/Cntr=0.3,0.1

River Reach=Mullens Pond    ,Mullens Pond
Reach XY= 22
597205.8806035985423384.21518309597209.8494035985423355.11098309
597202.5733035985423333.94428309597214.4796035985423296.90248309
597211.5568035985423278.33318309597206.9266035995423266.75758309
597222.4974035985423256.67698309597223.1324035985423245.88198309
597187.3606035985423228.52528309597179.1056035985423221.54018309
597174.6606035995423210.74518309597182.7040035995423201.85518309
597196.4835035985423171.16348309597209.9773035985423155.28838309
597231.4086035985423148.14468309597238.2877035985423133.06338309
597238.2877035985423114.80708309597239.8752035985423107.39878309
597240.9336035985423098.40288309597249.3473035985423076.54828309
597249.0828035995423058.55658309597254.9036035985423035.00858309

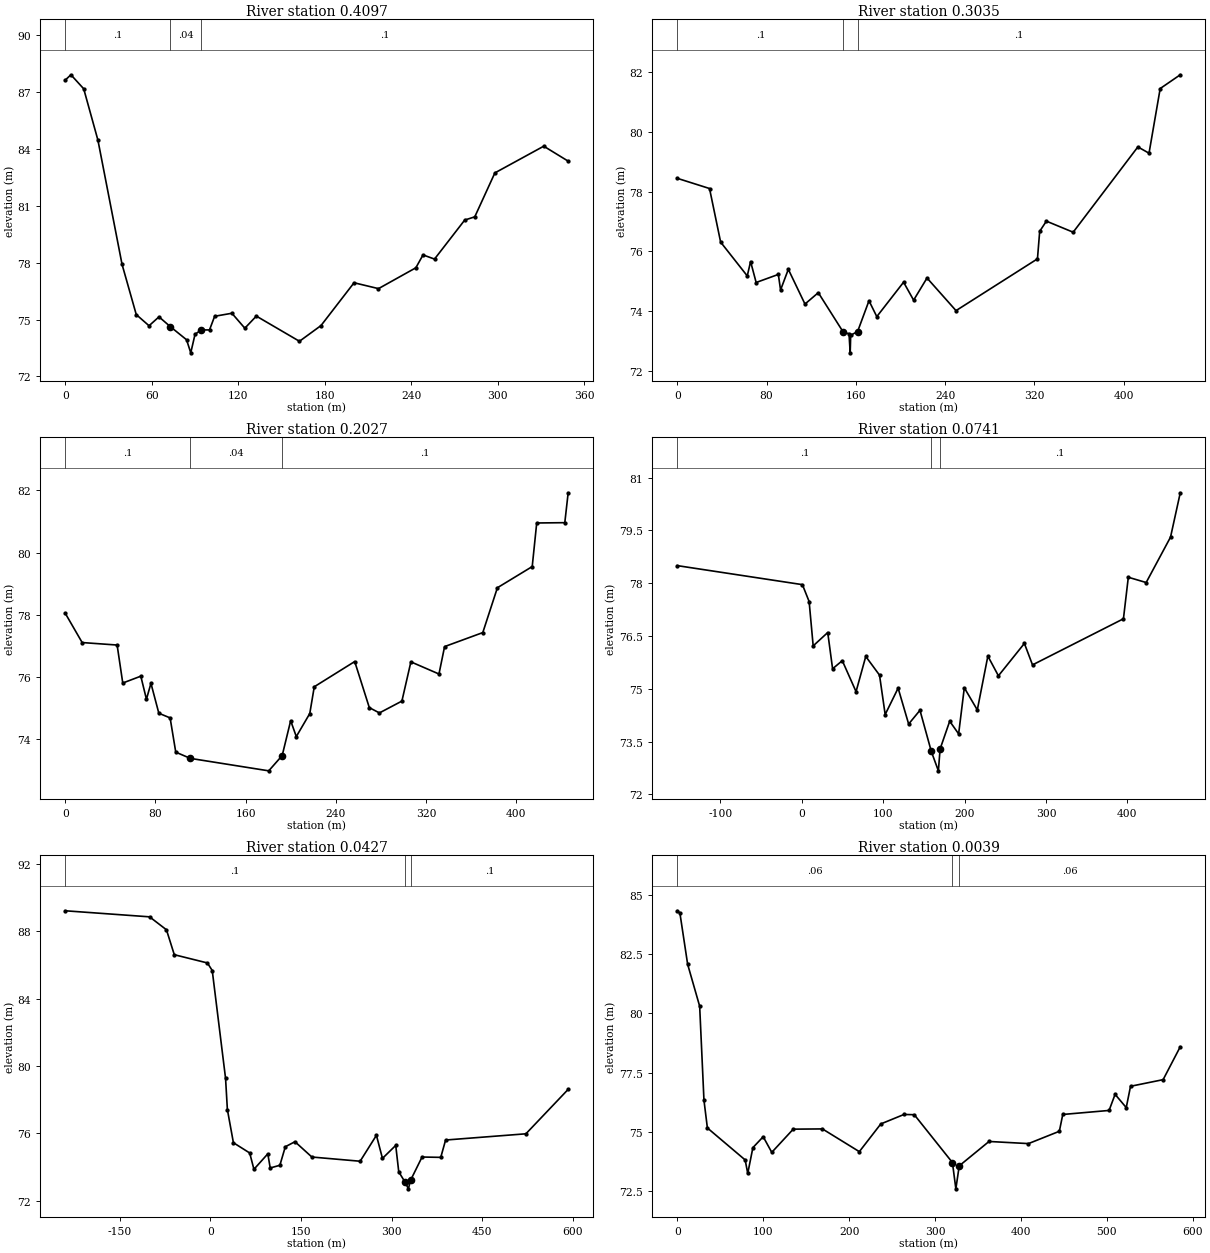
Type RM Length L Ch R = 1 ,0.4097  ,101.46,106.22,106.9
BEGIN DESCRIPTION:
MP06 (SEM 2019)
END DESCRIPTION:
XS GIS Cut Line= 4
597294.5514035985423378.73518309597231.0513035985423370.26858309
597192.9512035995423376.61858309596960.1174035995423457.05208309
#Sta/Elev= 30
       0   87.64    3.94   87.92   12.81   87.18   22.67   84.47   39.42   77.91
   49.28   75.26   58.15   74.67   65.05   75.14   72.98   74.62   84.19   73.93
    87.1   73.24   90.07   74.22   94.35   74.45  100.11   74.45  103.68   75.17
  115.65   75.33  124.63   74.54  132.61   75.18  162.53   73.85  177.49   74.68
  200.42   76.94  217.38   76.63  243.31   77.73  248.29   78.41  256.27   78.19
  277.22   80.25   284.2   80.42  298.16   82.74  332.07   84.15  349.02   83.36
#Mann= 3 , 0 , 0
       0      .1       0   72.98     .04       0   94.35      .1       0
Bank Sta=72.98,94.35
XS Rating Curve= 0 ,0
Exp/Cntr=0.3,0.1

Type RM Length L Ch R = 1 ,0.3035  ,93.2,100.76,102.81
BEGIN DESCRIPTION:
MP05 (SEM 2019)
END DESCRIPTION:
XS GIS Cut Line= 4
597365.4599035985423279.25168309597218.3513035985423273.95998309
597198.2429035995423269.72668309596915.6673035985423254.90998309
#Sta/Elev= 30
       0   78.44   28.84    78.1   38.79   76.31   62.66   75.18   65.64   75.66
   70.62   74.96   90.51   75.23    92.5   74.71   99.46    75.4  114.38   74.24
  126.32   74.62  148.89   73.29  153.85   73.25   154.9   72.61  155.36    73.2
  161.53   73.32  171.75   74.35  178.75   73.82  202.75   74.97  211.75   74.37
  223.75   75.11  249.74   74.02  322.73   75.75  324.73   76.67  330.73   77.01
  354.73   76.64  412.72   79.49  422.72   79.28  432.72   81.44  450.72    81.9
#Mann= 3 , 0 , 0
       0      .1       0  148.89     .04       0  161.53      .1       0
Bank Sta=148.89,161.53
XS Rating Curve= 0 ,0
Exp/Cntr=0.3,0.1

Type RM Length L Ch R = 1 ,0.2027  ,120.78,128.62,122.77
BEGIN DESCRIPTION:
MP04 (SEM 2019)
END DESCRIPTION:
XS GIS Cut Line= 4
597361.2265035995423232.68488309597187.6595035985423210.45988309
597163.3178035985423205.16818309596919.9007035985423241.15158309
#Sta/Elev= 30
       0   78.05      15   77.11      46   77.03      51   75.81   66.99   76.03
   71.99   75.29   75.99    75.8   82.99   74.84   92.99   74.69   97.99   73.59
  110.93   73.39  180.44   72.99  192.36   73.48  199.89    74.6  204.88   74.09
  216.83   74.83  220.81   75.69  256.68    76.5  269.63   75.02  278.59   74.85
  298.52   75.23  306.49   76.49  331.39    76.1  336.37   76.98  370.25   77.43
   383.2   78.87  414.08   79.55  418.06   80.95  442.97   80.96  445.96   81.92
#Mann= 3 , 0 , 0
       0      .1       0  110.93     .04       0  192.36      .1       0
Bank Sta=110.93,192.36
XS Rating Curve= 0 ,0
Exp/Cntr=0.3,0.1

Type RM Length L Ch R = 1 ,0.0741  ,29.72,31.41,32.29
BEGIN DESCRIPTION:
MP03 (SEM 2019)
END DESCRIPTION:
XS GIS Cut Line= 5
  597400.4269036 5423324.0046831  597389.7182036 5423167.6944831
  597256.4513036 5423106.7429831  597227.8763036 5423106.7429831
  596943.1840036 5423076.0512831
#Sta/Elev= 30
    -153    78.5.6799927   77.96    8.95   77.48   13.92   76.22   31.81    76.6
   37.78   75.57   49.71    75.8   66.61   74.92   78.54   75.92   95.44   75.39
   102.4   74.27  118.31   75.02  131.24      74  145.16   74.39  159.11   73.22
  167.79   72.67  169.88   73.29   181.7   74.08  192.67   73.72  199.65   75.03
  215.62    74.4  228.59   75.93  241.56   75.37  273.48   76.29  283.46   75.68
   395.2   76.99  401.19   78.17  423.14   78.02  453.07   79.31  465.04   80.57
#Mann= 3 , 0 , 0
    -153      .1       0  159.11     .04       0  169.88      .1       0
Bank Sta=159.11,169.88
XS Rating Curve= 0 ,0
Exp/Cntr=0.3,0.1

Type RM Length L Ch R = 1 ,0.0427  ,40.77,38.78,38.34
BEGIN DESCRIPTION:
MP02 (SEM 2019)
END DESCRIPTION:
XS GIS Cut Line= 5
  597683.7962036 5423327.9734831  597566.2175036 5423109.1601831
  597260.6847036 5423079.2262831  597239.5180036 5423074.9929831
  596985.5175036 5423043.2428831
#Sta/Elev= 30
  -240.5   89.23 -100.84   88.87-72.8999    88.1-59.9299   86.62   -5.07   86.13
2.919998   85.68   24.98   79.27   27.98   77.42   37.97   75.45   64.95   74.84
   71.95   73.87   94.93   74.79   98.93   73.95  114.92   74.11  123.91   75.21
   139.9   75.51  167.88    74.6  247.82   74.35   274.8   75.89  284.79   74.52
  306.77   75.29  311.77   73.72  321.84   73.13  327.76   72.71  331.23   73.21
  350.35    74.6  381.35   74.58  389.35   75.61  522.34   75.98  592.33   78.62
#Mann= 3 , 0 , 0
  -240.5      .1       0  321.84     .04       0  331.23      .1       0
Bank Sta=321.84,331.23
XS Rating Curve= 0 ,0
Exp/Cntr=0.3,0.1

Type RM Length L Ch R = 1 ,0.0039  ,4.95,3.88,2.93
BEGIN DESCRIPTION:
MP01 (SEM 2019) - Upstream of Second Avenue Culvert
END DESCRIPTION:
XS GIS Cut Line= 4
597576.0686035995423066.52628309597262.8013035985423035.83458309
597243.7513035985423042.18458309596993.9841035995423022.07618309
#Sta/Elev= 30
       0   84.33       3   84.23   11.99   82.07   25.98    80.3   30.98   76.33
   34.97   75.16   78.94   73.81   81.94   73.24   87.93   74.33   99.93   74.79
  109.92   74.13   134.9   75.11  168.88   75.12  211.84   74.16  236.82   75.33
   263.8   75.73   275.8   75.72   320.2    73.7   324.2   72.59  328.11   73.56
   362.8   74.59  408.72    74.5  444.66   75.02  448.65   75.73  502.56    75.9
  509.55   76.58  522.53   76.02  527.52   76.92  565.46    77.2  585.42   78.59
#Mann= 3 , 0 , 0
       0     .06       0   320.2     .04       0  328.11     .06       0
Bank Sta=320.2,328.11
XS Rating Curve= 0 ,0
Exp/Cntr=0.3,0.1

Storage Area=Power Canal     ,597586.238936,5420427.4297862
Storage Area Surface Line= 6
      597612.744     5420686.532
      597623.839     5420345.664
       597568.66     5420156.037
      597515.861     5420167.781
      597512.842     5420256.632
      597612.744     5420686.532
Storage Area Type= 1
Storage Area Vol Elev= 19
  28.566       0  29.706    .013  31.706     .14  33.706    .449  35.706   1.056
  37.706   2.121  39.706   3.858  41.706   9.498  43.706  28.171  45.706  56.916
  47.706   93.98  49.706 135.666  51.706 182.023  53.706 233.813  55.706 293.774
  57.706 360.483  59.706 430.815  61.706 505.199  63.706 585.183
Storage Area Is2D=0
Storage Area Point Generation Data=0,0,,
Storage Area 2D Points= 0
Storage Area Mannings=0.06
2D Cell Volume Filter Tolerance=0.003
2D Cell Minimum Area Fraction=0.01
2D Face Profile Filter Tolerance=0.003
2D Face Area Elevation Profile Filter Tolerance=0.003
2D Face Area Elevation Conveyance Ratio=0.02
2D Face Area Laminar Depth=0.06

Storage Area=Rushy Pond      ,594229.506539,5423213.4868293
Storage Area Surface Line= 6
594118.8875685395421890.49783816
593047.641640875 5422151.2306621
592513.0222341375423154.64691582
595207.540684902 5424476.7339923
595875.040881461 5423545.0954686
594118.8875685395421890.49783816
Storage Area Type= 1
Storage Area Vol Elev= 10
   66.75       0      67664.0372      683320.186      695976.335      708632.484
      7111288.63      7213944.78      7316600.93      7419257.08      7521913.23
Storage Area Is2D=0
Storage Area Point Generation Data=0,0,,
Storage Area 2D Points= 0
Storage Area Mannings=0.06
2D Cell Volume Filter Tolerance=0.003
2D Cell Minimum Area Fraction=0.01
2D Face Profile Filter Tolerance=0.003
2D Face Area Elevation Profile Filter Tolerance=0.003
2D Face Area Elevation Conveyance Ratio=0.02
2D Face Area Laminar Depth=0.06
LCMann Table=0

Chan Stop Cuts=-1
Use User Specified Reach Order=0
Composite Channel Slope=5