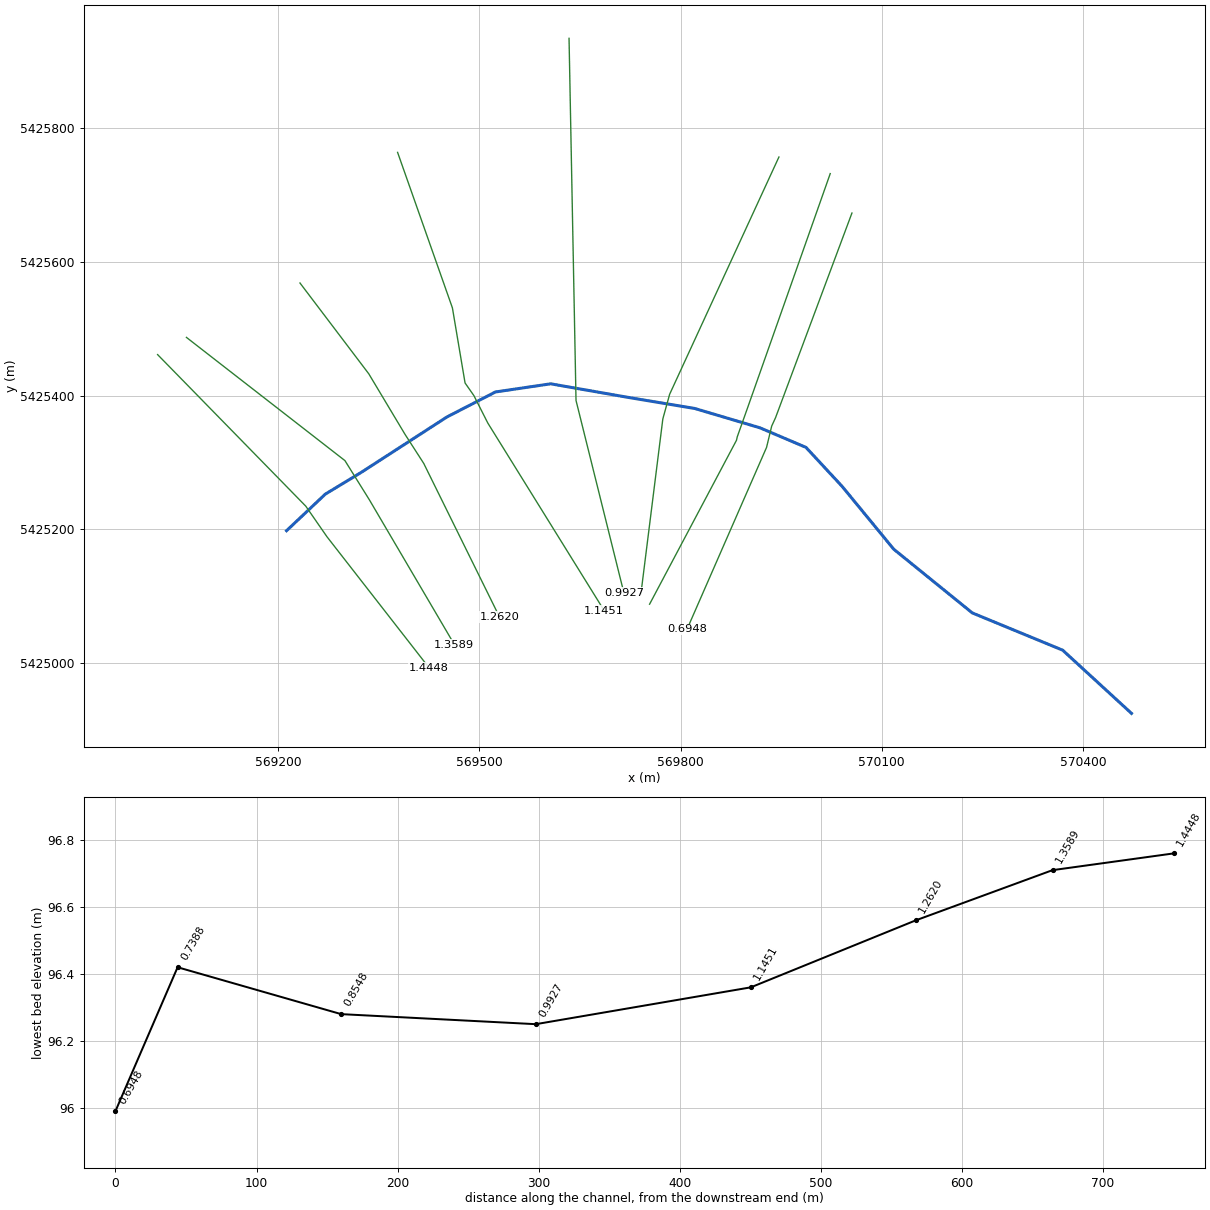
--- Unsteady_RAS.prj (project) ---

Proj Title=Unsteady_RAS
Current Plan=p01
Default Exp/Contr=0.3,0.1
SI Units
Geom File=g01
Unsteady File=u01
Plan File=p01
Y Axis Title=Elevation
X Axis Title(PF)=Main Channel Distance
X Axis Title(XS)=Station
BEGIN DESCRIPTION:
END DESCRIPTION:
DSS File=dss
DSS Export Rating Curves= 0
DSS Export Rating Curve Sorted= 0
DSS Export Volume Flow Curves= 0
DXF OffsetX= 0
DXF OffsetY= 0
DXF ScaleX= 1
DXF ScaleY= 10

--- Unsteady_RAS.p01 (plan) ---

Plan Title=2016
Program Version=5.03
Short Identifier=2016
Simulation Date=8oct2016,00:00,20oct2016,23:00
Geom File=g01
Flow File=u01
Mixed Flow
K Sum by GR= 0
Std Step Tol= 0.003
Critical Tol= 0.003
Num of Std Step Trials= 20
Max Error Tol= 0.1
Flow Tol Ratio= 0.001
Split Flow NTrial= 30
Split Flow Tol= 0.006
Split Flow Ratio= 0.02
Log Output Level= 0
Friction Slope Method= 1
Unsteady Friction Slope Method= 2
Unsteady Bridges Friction Slope Method= 1
Parabolic Critical Depth
Global Vel Dist= 0 , 0 , 0
Global Log Level= 0
CheckData=True
Encroach Param=-1 ,0,0, 0
Computation Interval=10MIN
Output Interval=1HOUR
Instantaneous Interval=1HOUR
Mapping Interval=1HOUR
Run HTab= 1
Run UNet= 1
Run Sediment= 0
Run PostProcess= 1
Run WQNet= 0
Run RASMapper= 0
UNET Theta= 1
UNET Theta Warmup= 1
UNET ZTol= 0.006
UNET ZSATol= 0.006
UNET MxIter= 20
UNET Max Iter WO Improvement= 0
UNET MaxInSteps= 0
UNET DtIC= 0
UNET DtMin= 0
UNET MaxCRTS= 20
UNET WFStab= 2
UNET SFStab= 1
UNET WFX= 1
UNET SFX= 1
UNET DSS MLevel= 4
UNET Pardiso=0
UNET DZMax Abort= 30
UNET Use Existing IB Tables=-1
UNET Froude Reduction=True
UNET Froude Limit= 0.8
UNET Froude Power= 4
UNET Time Slicing=0,0, 5
UNET D1 Cores= 0
UNET D2 Coriolis=0
UNET D2 Cores= 0
UNET D2 Theta= 1
UNET D2 Theta Warmup= 1
UNET D2 Z Tol= 0.003
UNET D2 Volume Tol= 0.003
UNET D2 Max Iterations= 20
UNET D2 Equation= 0
UNET D2 RampUpFraction=0.1
UNET D2 TimeSlices= 1
UNET D2 BCVolumeCheck=0
UNET D1D2 MaxIter= 0
UNET D1D2 ZTol=0.003
UNET D1D2 QTol=0.1
UNET D1D2 MinQTol=0.03
DSS File=dss
Write IC File= 0
Write IC File at Fixed DateTime=0
Write IC File at Sim End=0
Echo Input=False
Echo Parameters=False
Echo Output=False
Write Detailed= 0
HDF Write Warmup=0
HDF Write Time Slices=0
HDF Flush=0
HDF Face Node Velocities=0
HDF Compression= 1
HDF Chunk Size= 1
HDF Spatial Parts= 1
HDF Use Max Rows=0
HDF Fixed Rows= 1
Stage Flow Hydrograph=Exploits River  ,Mill to LRI     ,127.9419
Stage Flow Hydrograph=Exploits River  ,Mill to LRI     ,98.9083
Stage Flow Hydrograph=Exploits River  ,LRI to Badger   ,75.6731
Stage Flow Hydrograph=Exploits River  ,RP to Outlet    ,43.2587
Stage Flow Hydrograph=Exploits River  ,Badger to Wigwam,54.2773
Stage Flow Hydrograph=Exploits River  ,RP to Outlet    ,42.4277
Stage Flow Hydrograph=Exploits River  ,RP to Outlet    ,42.2908
Stage Flow Hydrograph=Exploits River  ,RP to Outlet    ,42.1704
Stage Flow Hydrograph=Little Red Ind  ,Little Red Ind  ,1.4448
Stage Flow Hydrograph=Little Red Ind  ,Little Red Ind  ,1.3589
Stage Flow Hydrograph=Little Red Ind  ,Little Red Ind  ,1.2620
Stage Flow Hydrograph=Little Red Ind  ,Little Red Ind  ,1.1451
Stage Flow Hydrograph=Little Red Ind  ,Little Red Ind  ,0.9927
Stage Flow Hydrograph=Little Red Ind  ,Little Red Ind  ,0.8548
Stage Flow Hydrograph=Little Red Ind  ,Little Red Ind  ,0.7388
Stage Flow Hydrograph=Little Red Ind  ,Little Red Ind  ,0.6948
Stage Flow Hydrograph=Little Red Ind  ,Little Red Ind  ,0.6682
Stage Flow Hydrograph=Little Red Ind  ,Little Red Ind  ,0.6158
Stage Flow Hydrograph=Little Red Ind  ,Little Red Ind  ,0.4661
Stage Flow Hydrograph=Little Red Ind  ,Little Red Ind  ,0.3022
Calibration Method= 0
Calibration Iterations= 20
Calibration Max Change=0.05
Calibration Tolerance=0.2
Calibration Maximum=1.5
Calibration Minimum=0.5
Calibration Optimization Method= 1
WQ AD Non Conservative
WQ ULTIMATE=-1
WQ Max Comp Step=1HOUR
WQ Output Interval=15MIN
WQ Output Selected Increments= 0
WQ Output face flow=0
WQ Output face velocity=0
WQ Output face area=0
WQ Output face dispersion=0
WQ Output cell volume=0
WQ Output cell surface area=0
WQ Output cell continuity=0
WQ Output cumulative cell continuity=0
WQ Output face conc=0
WQ Output face dconc_dx=0
WQ Output face courant=0
WQ Output face peclet=0
WQ Output face adv mass=0
WQ Output face disp mass=0
WQ Output cell mass=0
WQ Output cell source sink temp=0
WQ Output nsm pathways=0
WQ Output nsm derived pathways=0
WQ Output MaxMinRange=-1
WQ Daily Max Min Mean=-1
WQ Daily Range=0
WQ Daily Time=0
WQ Create Restart=0
WQ Fixed Restart=0
WQ System Summary=0
WQ Write To DSS=0
WQ Use Fixed Temperature=0
Sorting and Armoring Iterations= 10
XS Update Threshold= 0.02
Bed Roughness Predictor= 0
Hydraulics Update Threshold= 0.02
Energy Slope Method= 1
Volume Change Method= 1
Sediment Retention Method= 0
XS Weighting Method= 0
Number of US Weighted Cross Sections= 1
Number of DS Weighted Cross Sections= 1
Upstream XS Weight=0
Main XS Weight=1
Downstream XS Weight=0
Number of DS XS's Weighted with US Boundary= 1
Upstream Boundary Weight= 1
Weight of XSs Associated with US Boundary= 0
Number of US XS's Weighted with DS Boundary= 1
Downstream Boundary Weight= 0.5
Weight of XSs Associated with DS Boundary= 0.5
Percentile Method= 0
Sediment Output Level= 3
Mass or Volume Output= 0
Output Increment Type= 1
Profile and TS Output Increment= 1
XS Output Flag= 0
XS Output Increment= 10
Write Gradation File= 0
Read Gradation Hotstart= 0
Write HDF5 File= 1
Write DSS Sediment File= 0
SV Curve= 0
Specific Gage Flag= 0

--- Unsteady_RAS.u01 (unsteady flow) ---

Flow Title=2016
Program Version=5.03
Use Restart= 0
Initial Flow Loc=Rushy Pond      ,Rushy Pond      ,1.605   ,0.6
Initial Storage Elev=Power Canal     ,60.706
Initial Storage Elev=Rushy Pond      ,69.281
Initial RRR Elev=Exploits River  ,RP to Outlet    ,43.2587 ,60.706
Initial RRR Elev=Exploits River  ,RP to Outlet    ,23.7672 ,12.962
Boundary Location=Badger Brk      ,Badger Brk      ,1.9217  ,        ,                ,                ,                ,
Interval=1HOUR
Flow Hydrograph= 0
DSS File=2016.dss
DSS Path=//BADGERBROOKGAUGE/FLOW/31AUG2016 - 30OCT2016/1HOUR/RUN:2016/
Use DSS=True
Use Fixed Start Time=False
Fixed Start Date/Time=01oct2016,00:00
Is Critical Boundary=False
Boundary Location=Exploits River  ,RP to Outlet    ,0.0989  ,        ,                ,                ,                ,
Interval=1DAY
Stage Hydrograph= 200
    .397    .397      .4      .4      .4      .4      .4      .4      .4      .4
      .4      .4      .4      .4      .4      .4      .4      .4      .4      .4
      .4      .4      .4      .4      .4      .4      .4      .4      .4      .4
      .4      .4      .4      .4      .4      .4      .4      .4      .4      .4
      .4      .4      .4      .4      .4      .4      .4      .4      .4      .4
      .4      .4      .4      .4      .4      .4      .4      .4      .4      .4
      .4      .4      .4      .4      .4      .4      .4      .4      .4      .4
      .4      .4      .4      .4      .4      .4      .4      .4      .4      .4
      .4      .4      .4      .4      .4      .4      .4      .4      .4      .4
      .4      .4      .4      .4      .4      .4      .4      .4      .4    .397
      .4      .4      .4      .4      .4      .4      .4      .4      .4      .4
      .4      .4      .4      .4      .4      .4      .4      .4      .4      .4
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Use DSS=False
Use Fixed Start Time=False
Is Critical Boundary=False
Boundary Location=Exploits River  ,RP to Outlet    ,43.309  ,        ,                ,                ,                ,
Elev Controlled Gate=Forebay,100,0,0,0,3.66,3.66,3.66, 0
Boundary Location=Little Red Ind  ,Little Red Ind  ,1.4448  ,        ,                ,                ,                ,
Interval=1HOUR
Flow Hydrograph= 0
DSS File=2016.dss
DSS Path=//SUBLITTLEREDINDIAN/FLOW/31AUG2016 - 30OCT2016/1HOUR/RUN:2016/
Use DSS=True
Use Fixed Start Time=False
Is Critical Boundary=False
Boundary Location=Wigwam Brook    ,Wigwam Brook    ,2.890   ,        ,                ,                ,                ,
Interval=1HOUR
Flow Hydrograph= 0
DSS File=2016.dss
DSS Path=//WIGWAMCULVERT1/FLOW/31AUG2016 - 30OCT2016/1HOUR/RUN:2016/
Use DSS=True
Use Fixed Start Time=False
Is Critical Boundary=False
Boundary Location=Exploits River  ,Mill to LRI     ,100.6527,        ,                ,                ,                ,
Interval=1HOUR
Lateral Inflow Hydrograph= 0
DSS File=2016.dss
DSS Path=//SUBEXPLMILLTONOEL/FLOW/31AUG2016 - 30OCT2016/1HOUR/RUN:2016/
Use DSS=True
Use Fixed Start Time=False
Is Critical Boundary=False
Boundary Location=Little Red Ind  ,Little Red Ind  ,1.3589  ,        ,                ,                ,                ,
Interval=1HOUR
Lateral Inflow Hydrograph= 0
DSS File=2016.dss
DSS Path=//SUBSTR1TOLITREDIND/FLOW/31AUG2016 - 30OCT2016/1HOUR/RUN:2016/
Use DSS=True
Use Fixed Start Time=False
Is Critical Boundary=False
Boundary Location=Exploits River  ,Mill to LRI     ,76.3060 ,        ,                ,                ,                ,
Interval=1HOUR
Lateral Inflow Hydrograph= 0
DSS File=2016.dss
DSS Path=//SUBEXPLNOELTOBAD/FLOW/31AUG2016 - 30OCT2016/1HOUR/RUN:2016/
Use DSS=True
Use Fixed Start Time=False
Is Critical Boundary=False
Boundary Location=Exploits River  ,Badger to Wigwam,51.6126 ,        ,                ,                ,                ,
Interval=1HOUR
Lateral Inflow Hydrograph= 0
DSS File=2016.dss
DSS Path=//SANDYBROOK1/FLOW/31AUG2016 - 30OCT2016/1HOUR/RUN:2016/
Use DSS=True
Use Fixed Start Time=False
Is Critical Boundary=False
Boundary Location=Exploits River  ,Badger to Wigwam,52.8115 ,        ,                ,                ,                ,
Interval=1HOUR
Lateral Inflow Hydrograph= 0
DSS File=2016.dss
DSS Path=//SUBSANDYBRKDAMTOEXPL/FLOW/31AUG2016 - 30OCT2016/1HOUR/RUN:2016/
Use DSS=True
Use Fixed Start Time=False
Is Critical Boundary=False
Boundary Location=                ,                ,        ,        ,                ,Rushy Pond      ,                ,
Interval=1HOUR
Lateral Inflow Hydrograph= 0
DSS File=2016.dss
DSS Path=//RUSHYPONDATTCH/FLOW/31AUG2016 - 30OCT2016/1HOUR/RUN:2016/
Use DSS=True
Use Fixed Start Time=False
Is Critical Boundary=False
Boundary Location=Exploits River  ,RP to Outlet    ,43.6571 ,        ,                ,                ,                ,
Interval=1HOUR
Lateral Inflow Hydrograph= 0
DSS File=2016.dss
DSS Path=//CORDUROYBROOK1/FLOW/31AUG2016 - 30OCT2016/1HOUR/RUN:2016/
Use DSS=True
Use Fixed Start Time=False
Is Critical Boundary=False
Boundary Location=Exploits River  ,RP to Outlet    ,43.3884 ,        ,                ,                ,                ,
Interval=1HOUR
Lateral Inflow Hydrograph= 0
DSS File=2016.dss
DSS Path=//SUBEXPLGOODTOGRAND/FLOW/31AUG2016 - 30OCT2016/1HOUR/RUN:2016/
Use DSS=True
Use Fixed Start Time=False
Is Critical Boundary=False
Boundary Location=Exploits River  ,RP to Outlet    ,41.6238 ,        ,                ,                ,                ,
Interval=1HOUR
Lateral Inflow Hydrograph= 0
DSS File=2016.dss
DSS Path=//SUBEXPLGRFALLSTOST/FLOW/31AUG2016 - 30OCT2016/1HOUR/RUN:2016/
Use DSS=True
Use Fixed Start Time=False
Is Critical Boundary=False
Boundary Location=Exploits River  ,RP to Outlet    ,33.2970 ,        ,                ,                ,                ,
Interval=1HOUR
Lateral Inflow Hydrograph= 0
DSS File=2016.dss
DSS Path=//SUBEXPLSTONYTOGRRATT/FLOW/31AUG2016 - 30OCT2016/1HOUR/RUN:2016/
Use DSS=True
Use Fixed Start Time=False
Is Critical Boundary=False
Boundary Location=Exploits River  ,RP to Outlet    ,30.6038 ,        ,                ,                ,                ,
Interval=1HOUR
Lateral Inflow Hydrograph= 0
DSS File=2016.dss
DSS Path=//SUBGRRATTTOEXPL/FLOW/31AUG2016 - 30OCT2016/1HOUR/RUN:2016/
Use DSS=True
Use Fixed Start Time=False
Is Critical Boundary=False
Boundary Location=Exploits River  ,RP to Outlet    ,31.6595 ,        ,                ,                ,                ,
Interval=1HOUR
Lateral Inflow Hydrograph= 0
DSS File=2016.dss
DSS Path=//GREATRATTLINGBROOK1/FLOW/31AUG2016 - 30OCT2016/1HOUR/RUN:2016/
Use DSS=True
Use Fixed Start Time=False
Is Critical Boundary=False
Boundary Location=Exploits River  ,RP to Outlet    ,29.6258 ,        ,                ,                ,                ,
Interval=1HOUR
Lateral Inflow Hydrograph= 0
DSS File=2016.dss
DSS Path=//STREAM2_1/FLOW/31AUG2016 - 30OCT2016/1HOUR/RUN:2016/
Use DSS=True
Use Fixed Start Time=False
Is Critical Boundary=False
Boundary Location=Exploits River  ,RP to Outlet    ,26.3491 ,        ,                ,                ,                ,
Interval=1HOUR
Lateral Inflow Hydrograph= 0
DSS File=2016.dss
DSS Path=//STREAM3_1/FLOW/31AUG2016 - 30OCT2016/1HOUR/RUN:2016/
Use DSS=True
Use Fixed Start Time=False
Is Critical Boundary=False
Boundary Location=Exploits River  ,RP to Outlet    ,23.3904 ,        ,                ,                ,                ,
Interval=1HOUR
Lateral Inflow Hydrograph= 0
DSS File=2016.dss
DSS Path=//STREAM4_2/FLOW/31AUG2016 - 30OCT2016/1HOUR/RUN:2016/
Use DSS=True
Use Fixed Start Time=False
Is Critical Boundary=False
Boundary Location=Exploits River  ,RP to Outlet    ,25.6408 ,        ,                ,                ,                ,
Interval=1HOUR
Lateral Inflow Hydrograph= 0
DSS File=2016.dss
DSS Path=//SUBSTREAM3URBAN/FLOW/31AUG2016 - 30OCT2016/1HOUR/RUN:2016/
Use DSS=True
Use Fixed Start Time=False
Is Critical Boundary=False
Boundary Location=Exploits River  ,RP to Outlet    ,21.7690 ,        ,                ,                ,                ,
Interval=1HOUR
Lateral Inflow Hydrograph= 0
DSS File=2016.dss
DSS Path=//SUBEXPLBISHTOGAUGE/FLOW/31AUG2016 - 30OCT2016/1HOUR/RUN:2016/
Use DSS=True
Use Fixed Start Time=False
Is Critical Boundary=False
Boundary Location=Exploits River  ,RP to Outlet    ,20.2457 ,        ,                ,                ,                ,
Interval=1HOUR
Lateral Inflow Hydrograph= 0
DSS File=2016.dss
DSS Path=//SUBSTREAM5TOEXPL/FLOW/31AUG2016 - 30OCT2016/1HOUR/RUN:2016/
Use DSS=True
Use Fixed Start Time=False
Is Critical Boundary=False
Boundary Location=Exploits River  ,RP to Outlet    ,18.0852 ,        ,                ,                ,                ,
Interval=1HOUR
Lateral Inflow Hydrograph= 0
DSS File=2016.dss
DSS Path=//SUBJUMPERSBROOK/FLOW/31AUG2016 - 30OCT2016/1HOUR/RUN:2016/
Use DSS=True
Use Fixed Start Time=False
Is Critical Boundary=False
Boundary Location=Exploits River  ,RP to Outlet    ,8.4354  ,        ,                ,                ,                ,
Interval=1HOUR
Lateral Inflow Hydrograph= 0
DSS File=2016.dss
DSS Path=//SUBEASTERN/FLOW/31AUG2016 - 30OCT2016/1HOUR/RUN:2016/
Use DSS=True
Use Fixed Start Time=False
Is Critical Boundary=False
Boundary Location=Exploits River  ,RP to Outlet    ,9.3990  ,        ,                ,                ,                ,
Interval=1HOUR
Lateral Inflow Hydrograph= 0
DSS File=2016.dss
DSS Path=//SUBEXPLNEWGAUTOOUT/FLOW/31AUG2016 - 30OCT2016/1HOUR/RUN:2016/
Use DSS=True
Use Fixed Start Time=False
Is Critical Boundary=False
Boundary Location=Exploits River  ,RP to Outlet    ,3.1711  ,        ,                ,                ,                ,
Interval=1HOUR
Lateral Inflow Hydrograph= 0
DSS File=2016.dss
DSS Path=//SUBOUTLET1/FLOW/31AUG2016 - 30OCT2016/1HOUR/RUN:2016/
Use DSS=True
Use Fixed Start Time=False
Is Critical Boundary=False
Boundary Location=Exploits River  ,RP to Outlet    ,2.4185  ,        ,                ,                ,                ,
Interval=1HOUR
Lateral Inflow Hydrograph= 0
DSS File=2016.dss
DSS Path=//SUBPETERSRIV1TOOUTL/FLOW/31AUG2016 - 30OCT2016/1HOUR/RUN:2016/
Use DSS=True
Use Fixed Start Time=False
Is Critical Boundary=False
Boundary Location=Exploits River  ,RP to Outlet    ,0.9662  ,        ,                ,                ,                ,
Interval=1HOUR
Lateral Inflow Hydrograph= 0
DSS File=2016.dss
DSS Path=//PETERSRIVER1/FLOW/31AUG2016 - 30OCT2016/1HOUR/RUN:2016/
Use DSS=True
Use Fixed Start Time=False
Is Critical Boundary=False
Boundary Location=Exploits River  ,RP to Outlet    ,47.4290 ,        ,                ,                ,                ,
Interval=1HOUR
Lateral Inflow Hydrograph= 0
DSS File=2016.dss
DSS Path=//SUBEXPLCHARTOGOOD/FLOW/31AUG2016 - 30OCT2016/1HOUR/RUN:2016/
Use DSS=True
Use Fixed Start Time=False
Is Critical Boundary=False
Boundary Location=Exploits River  ,RP to Outlet    ,24.1375 ,        ,                ,                ,                ,
Interval=1HOUR
Lateral Inflow Hydrograph= 0
DSS File=2016.dss
DSS Path=//SUBEXPLGRRATTTOBISH/FLOW/31AUG2016 - 30OCT2016/1HOUR/RUN:2016/
Use DSS=True
Use Fixed Start Time=False
Is Critical Boundary=False
Boundary Location=Exploits River  ,RP to Outlet    ,43.2577 ,        ,                ,                ,                ,
Elev Controlled Gate=Outside Gate,61,60.4,0.066,0.066,3.9624,0,3.9624, 0
Elev Controlled Gate=Obermeyer   ,61,60.4,0.025,0.025,1.5,0,0.86, 0
Boundary Location=Exploits River  ,RP to Outlet    ,43.231  ,        ,                ,                ,                ,
Elev Controlled Gate=Inside Gate,61.011,60.401,0.0355,0.0355,2.1336,0,0, 1
Elev Controlled Gate Ref=61,60.4,                ,                ,        ,Power Canal
Elev Controlled Gate=RCC Fboards,,,0.02,0.02,0.9,0,0, 1
Elev Controlled Gate Ref=61.206,59.806,                ,                ,        ,Power Canal
Boundary Location=Exploits River  ,Mill to LRI     ,127.9419,        ,                ,                ,                ,
Interval=1HOUR
Flow Hydrograph= 0
DSS File=2016.dss
DSS Path=//MILLERTOWNDAM/FLOW/31AUG2016 - 30OCT2016/1HOUR/RUN:2016/
Use DSS=True
Use Fixed Start Time=False
Is Critical Boundary=False
Boundary Location=Exploits River  ,RP to Outlet    ,23.7635 ,        ,                ,                ,                ,
Elev Controlled Gate=BF Gates,13.267,11.437,0.008,0.008,4.328,0,0.41, 0
Elev Controlled Gate=BF Fboards,13.419,11.742,0.015,0.015,1.22,0,0, 0
Boundary Location=Exploits River  ,Badger to Wigwam,54.2773 ,        ,                ,                ,                ,
Interval=1HOUR
Lateral Inflow Hydrograph= 0
DSS File=2016.dss
DSS Path=//SUBEXPLBAGERTOCHAR/FLOW/31AUG2016 - 30OCT2016/1HOUR/RUN:2016/
Use DSS=True
Use Fixed Start Time=False
Is Critical Boundary=False
Boundary Location=Exploits River  ,RP to Outlet    ,28.6539 ,        ,                ,                ,                ,
Interval=1HOUR
Lateral Inflow Hydrograph= 0
DSS File=2016.dss
DSS Path=//SUBSTREAM2URBAN/FLOW/31AUG2016 - 30OCT2016/1HOUR/RUN:2016/
Use DSS=True
Use Fixed Start Time=False
Is Critical Boundary=False
Boundary Location=Exploits River  ,RP to Outlet    ,44.3558 ,        ,                ,                ,                ,
Interval=1HOUR
Lateral Inflow Hydrograph= 0
DSS File=2016.dss
DSS Path=//SUBSTREAM6TOSEWER/FLOW/31AUG2016 - 30OCT2016/1HOUR/RUN:2016/
Use DSS=True
Use Fixed Start Time=False
Is Critical Boundary=False

--- Unsteady_RAS.g01 (geometry) ---

Geom Title=Exploits_Geometry
Program Version=5.03

Junct Name=2
Junct Desc=, 0 , 0 ,-1 ,-1
Up River,Reach=Exploits River  ,Mill to LRI
Up River,Reach=Little Red Ind  ,Little Red Ind
Dn River,Reach=Exploits River  ,LRI to Badger
Junc L&A=365,
Junc L&A=325,

Junct Name=3
Junct Desc=, 0 , 0 ,-1 ,-1
Up River,Reach=Exploits River  ,LRI to Badger
Up River,Reach=Badger Brk      ,Badger Brk
Dn River,Reach=Exploits River  ,Badger to Wigwam
Junc L&A=208,
Junc L&A=393,0

Junct Name=Wigwam
Junct Desc=, 0 , 0 ,-1 ,-1
Up River,Reach=Exploits River  ,Badger to Wigwam
Up River,Reach=Wigwam Brook    ,Wigwam Brook
Dn River,Reach=Exploits River  ,Wigwam to RP
Junc L&A=280.45,
Junc L&A=1215,0

Junct Name=RP
Junct Desc=, 0 , 0 ,-1 ,-1
Up River,Reach=Exploits River  ,Wigwam to RP
Up River,Reach=Rushy Pond      ,Rushy Pond
Dn River,Reach=Exploits River  ,RP to Outlet
Junc L&A=939.38,
Junc L&A=805,0

River Reach=Little Red Ind  ,Little Red Ind
Reach XY= 15
     569212.6543    5425198.1977     569270.4736    5425252.8639
      569324.013    5425285.3142     569451.4928    5425367.9431
     569524.0134     5425405.405     569606.3902    5425417.6007
     569724.1196    5425396.9294     569821.1555    5425380.7475
     569918.3586    5425351.8695      569986.996    5425322.6155
     570040.9625    5425264.2393     570117.7482    5425170.5547
     570234.8874    5425075.3554     570369.6267    5425019.6983
     570472.2323    5424925.2875

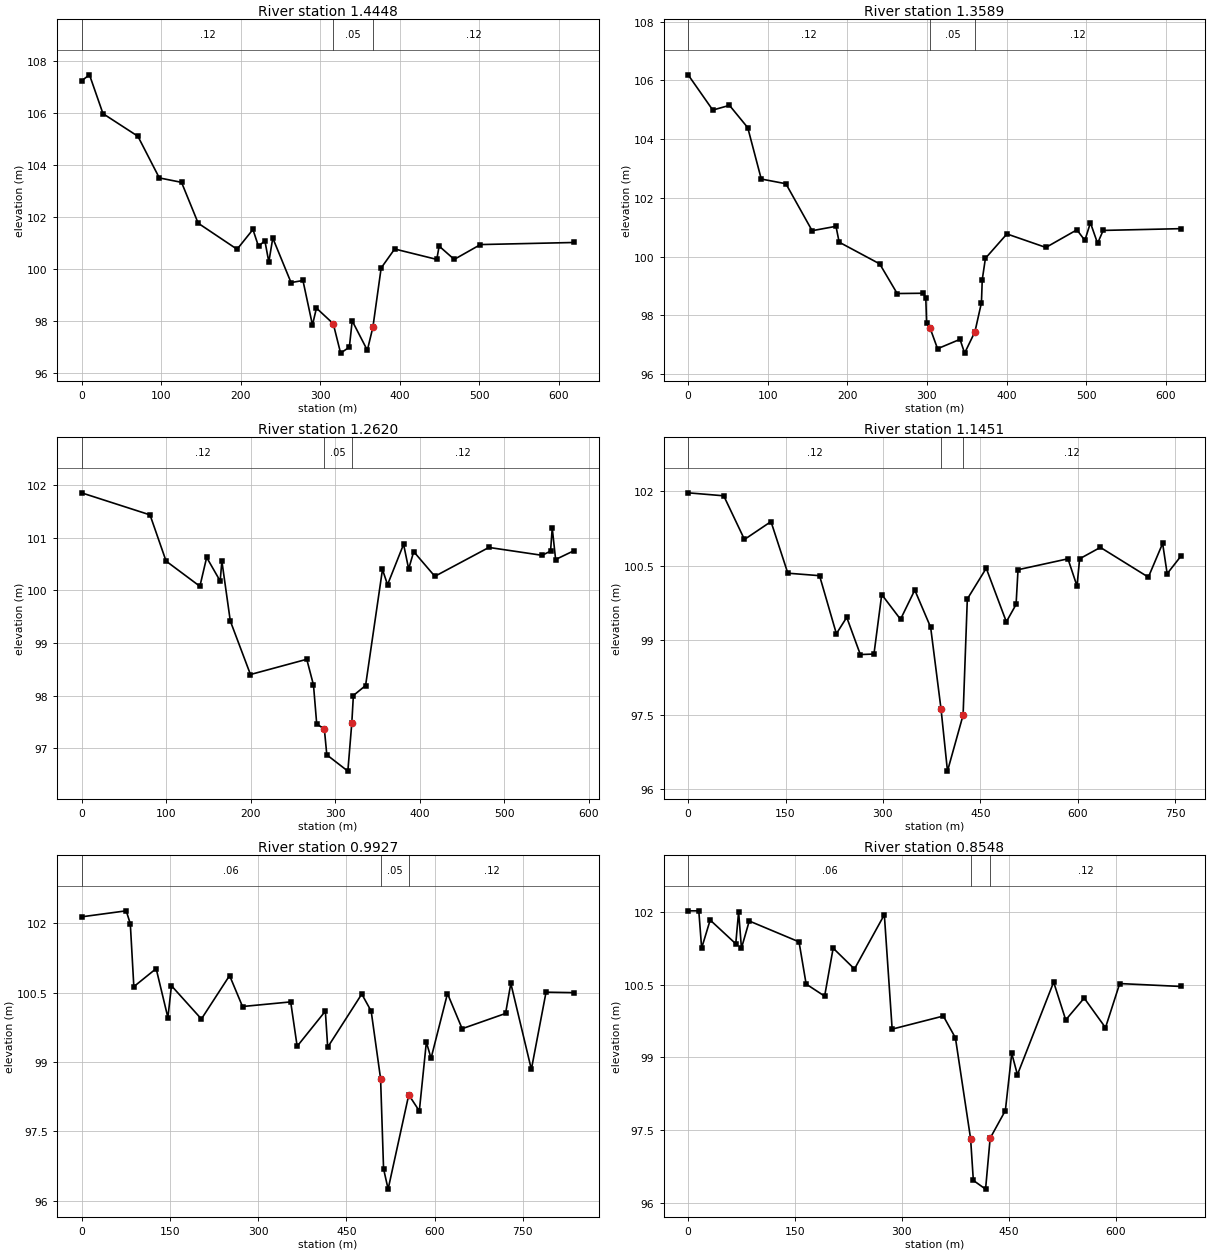
Type RM Length L Ch R = 1 ,1.4448  ,99.23,85.87,92.89
BEGIN DESCRIPTION:
LR12 (SEM 2019)
END DESCRIPTION:
XS GIS Cut Line= 4
569020.3638035985425461.27518309569241.2940035985425234.82298309
569272.8290035995425189.21998309569424.9241035985424993.59988309
#Sta/Elev= 30
       0  107.22    9.98  107.45   26.95  105.96   70.86  105.09   97.81  103.49
  125.75  103.32  146.71  101.75  195.61  100.75  215.57  101.51  222.56  100.86
  230.54  101.08  235.53  100.26  240.52  101.18  263.48   99.47  278.45   99.55
  290.42   97.84  295.41   98.49  316.57   97.89  325.82   96.76  336.81   96.99
  340.38      98  359.44   96.87  366.44   97.76  376.81  100.03   393.8  100.76
  446.75  100.36  449.75  100.87  468.73  100.36  501.71  100.93   619.6  101.01
#Mann= 3 , 0 , 0
       0     .12       0  316.57     .05       0  366.44     .12       0
Bank Sta=316.57,366.44
XS Rating Curve= 0 ,0
Exp/Cntr=0.3,0.1

Type RM Length L Ch R = 1 ,1.3589  ,98.29,96.97,97.34
BEGIN DESCRIPTION:
LR11 (SEM 2019)
END DESCRIPTION:
XS GIS Cut Line= 5
569063.3850035985425486.94048309569299.6660035985425302.87898309
569336.0600035985425244.38098309569461.8483035985425029.73958309
569461.8483035985425028.15208309
#Sta/Elev= 30
       0  106.19   30.95  104.99   51.92  105.15   74.88  104.39   91.85  102.64
   122.8  102.48  155.75  100.88   185.7  101.03  189.69  100.49  240.61   99.75
  262.57   98.74  295.52   98.75  298.51   98.59  299.51   97.73  304.08   97.55
  313.28   96.86  341.48   97.18  347.27   96.71  360.25   97.44  368.41   98.43
  369.41   99.21   373.4   99.94  400.38  100.77  449.34  100.31   488.3  100.91
   498.3  100.55  505.29  101.15  514.28  100.45  521.28  100.89  618.78  100.95
#Mann= 3 , 0 , 0
       0     .12       0  304.08     .05       0  360.25     .12       0
Bank Sta=304.08,360.25
XS Rating Curve= 0 ,0
Exp/Cntr=0.3,0.1

Type RM Length L Ch R = 1 ,1.2620  ,117.98,116.87,117.04
BEGIN DESCRIPTION:
LR10 (SEM 2019)
END DESCRIPTION:
XS GIS Cut Line= 5
569232.6473035985425568.18578309569335.1735035985425432.58658309
569389.2260035985425342.12398309569417.1370035985425298.67898309
569530.1535035995425069.21478309
#Sta/Elev= 30
       0  101.86      81  101.44     100  100.56     140  100.08     148  100.63
     164  100.18     166  100.56  175.96   99.42  199.82    98.4  266.43   98.69
  274.38    98.2  278.19   97.46  287.24   97.36  290.15   96.87  315.03   96.56
  319.72   97.48  321.56      98  336.01   98.19  355.99   100.4  361.99  100.11
  380.97  100.88  386.97  100.41  392.96  100.74  417.94  100.27  481.89  100.82
  544.83  100.67  554.83  100.75  556.82  101.19  560.82  100.59   582.8  100.76
#Mann= 3 , 0 , 0
       0     .12       0  287.24     .05       0  319.72     .12       0
Bank Sta=287.24,319.72
XS Rating Curve= 0 ,0
Exp/Cntr=0.3,0.1

Type RM Length L Ch R = 1 ,1.1451  ,156.91,152.39,143.71
BEGIN DESCRIPTION:
LR09 (SEM 2019)
END DESCRIPTION:
XS GIS Cut Line= 6
569378.1684035985425763.31638309569459.8800035995425531.01998309
569478.7487035985425418.82898309569491.9420035985425399.91198309
569512.6705035995425358.94798309569686.1938035985425078.69428309
#Sta/Elev= 30
       0  101.97   54.83  101.91   86.74  101.03  127.61  101.39  153.53  100.35
  202.38   100.3   228.3   99.13  244.25   99.46  265.21   98.71  286.17   98.72
  298.14   99.92  327.08   99.42  349.04  100.01  373.47   99.26  389.49   97.61
   399.4   96.36  423.45   97.49  429.96   99.83   459.1  100.45  490.06   99.37
  505.04   99.72  508.04  100.42  584.93  100.64  598.91  100.09  602.91  100.64
  634.87  100.87  708.77  100.27  730.74  100.95  737.73  100.34   758.7  100.69
#Mann= 3 , 0 , 0
       0     .12       0  389.49     .05       0  423.45     .12       0
Bank Sta=389.49,423.45
XS Rating Curve= 0 ,0
Exp/Cntr=0.3,0.1

Type RM Length L Ch R = 1 ,0.9927  ,141.85,137.93,136.59
BEGIN DESCRIPTION:
LR08 (SEM 2019)
END DESCRIPTION:
XS GIS Cut Line= 3
  569633.7520036 5425933.6886831  569644.1570036 5425392.7119831
  569715.5080036 5425105.3598831
#Sta/Elev= 30
       0  102.14   75.87  102.27   82.86  101.99   88.85  100.63  126.78  101.02
  146.75   99.96  152.74  100.65  203.65   99.93  251.57  100.87  273.53   100.2
  355.39   100.3  366.38   99.34  414.29   100.1  418.29   99.32  476.19  100.47
  492.16   100.1  508.15   98.64  513.21   96.69  520.97   96.25  556.03   98.29
  573.98   97.94  585.94   99.43  593.91   99.08  621.83  100.48  646.75   99.72
  720.52  100.05  729.49   100.7  764.38   98.84  789.31  100.51  837.16   100.5
#Mann= 3 , 0 , 0
       0     .06       0  508.15     .05       0  556.03     .12       0
Bank Sta=508.15,556.03
XS Rating Curve= 0 ,0
Exp/Cntr=0.3,0.1

Type RM Length L Ch R = 1 ,0.8548  ,117.08,115.94,115.7
BEGIN DESCRIPTION:
LR07 (SEM 2019)
END DESCRIPTION:
XS GIS Cut Line= 4
  569946.6459036 5425756.4258831  569783.7270036 5425401.9979831
  569773.5770036 5425365.2119831  569740.9207036 5425104.1072831
#Sta/Elev= 30
       0  102.02   14.96  102.02   18.96  101.25   30.93  101.83   66.84  101.34
   70.83     102   74.82  101.25    85.8  101.81  155.63  101.38  165.61  100.51
  191.55  100.26  203.52  101.25  233.45  100.82  275.35  101.94  286.32   99.58
  358.15   99.85  375.11    99.4  396.41   97.32  400.25   96.46  417.42   96.28
  423.84   97.33  445.18    97.9  454.15   99.08  462.13   98.64  512.96  100.55
  529.91   99.77  555.82  100.22  585.72   99.61  605.66  100.52  691.38  100.46
#Mann= 3 , 0 , 0
       0     .06       0  396.41     .05       0  423.84     .12       0
Bank Sta=396.41,423.84
XS Rating Curve= 0 ,0
Exp/Cntr=0.3,0.1

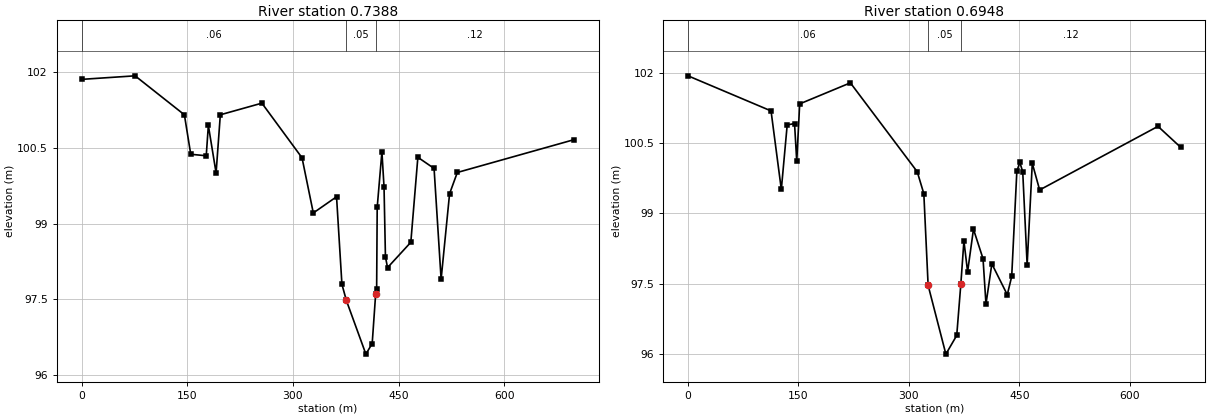
Type RM Length L Ch R = 1 ,0.7388  ,43.98,44.07,46.06
BEGIN DESCRIPTION:
LR06 (SEM 2019)
END DESCRIPTION:
XS GIS Cut Line= 5
  570023.1255036 5425731.6166831  569899.9390036 5425381.8449831
  569884.5520036 5425338.5139831  569883.3601036 5425333.2495831
  569753.8255036 5425088.4046831
#Sta/Elev= 30
       0  101.85   75.97  101.92  145.93  101.15  154.93  100.37  176.92  100.34
  179.92  100.94  190.91     100  196.91  101.15  255.88  101.38  312.86   100.3
  328.85   99.21  361.83   99.53  369.46    97.8  375.77   97.48  403.45   96.42
  412.41   96.63  417.33   97.61  418.72    97.7  419.51   99.32  426.21  100.42
  429.21   99.72  431.21   98.34  434.21   98.13  467.21   98.63  477.21  100.31
  500.21  100.09  510.21    97.9  522.21   99.59  533.21  100.01  699.21  100.66
#Mann= 3 , 0 , 0
       0     .06       0  375.77     .05       0  417.33     .12       0
Bank Sta=375.77,417.33
XS Rating Curve= 0 ,0
Exp/Cntr=0.3,0.1

Type RM Length L Ch R = 1 ,0.6948  ,27.23,26.59,25.31
BEGIN DESCRIPTION:
US of Buchans Hwy Bridge - LR05 (SEM 2019)
END DESCRIPTION:
XS GIS Cut Line= 5
  570055.4848036 5425672.7305831  569941.5670036 5425366.9399831
  569935.8840036 5425354.5409831  569928.1980036 5425322.6279831
  569809.5743036 5425050.8041831
#Sta/Elev= 30
       0  101.94  112.77  101.19  126.74   99.51  134.72  100.89   144.7  100.92
  147.69  100.11  151.68  101.34  220.54  101.79  311.35   99.89  320.33   99.42
  326.16   97.46  350.27   95.99  365.02   96.39  370.56   97.48  374.78   98.41
  379.78   97.75  387.76   98.66  400.75   98.03  404.74   97.06  412.73   97.92
   433.7   97.26  439.69   97.65  446.68    99.9  450.68  100.09  454.67   99.89
  460.66    97.9  467.65  100.07  477.64    99.5  638.41  100.86  669.37  100.41
#Mann= 3 , 0 , 0
       0     .06       0  326.16     .05       0  370.56     .12       0
Bank Sta=326.16,370.56
XS Rating Curve= 0 ,0
Exp/Cntr=0.3,0.1