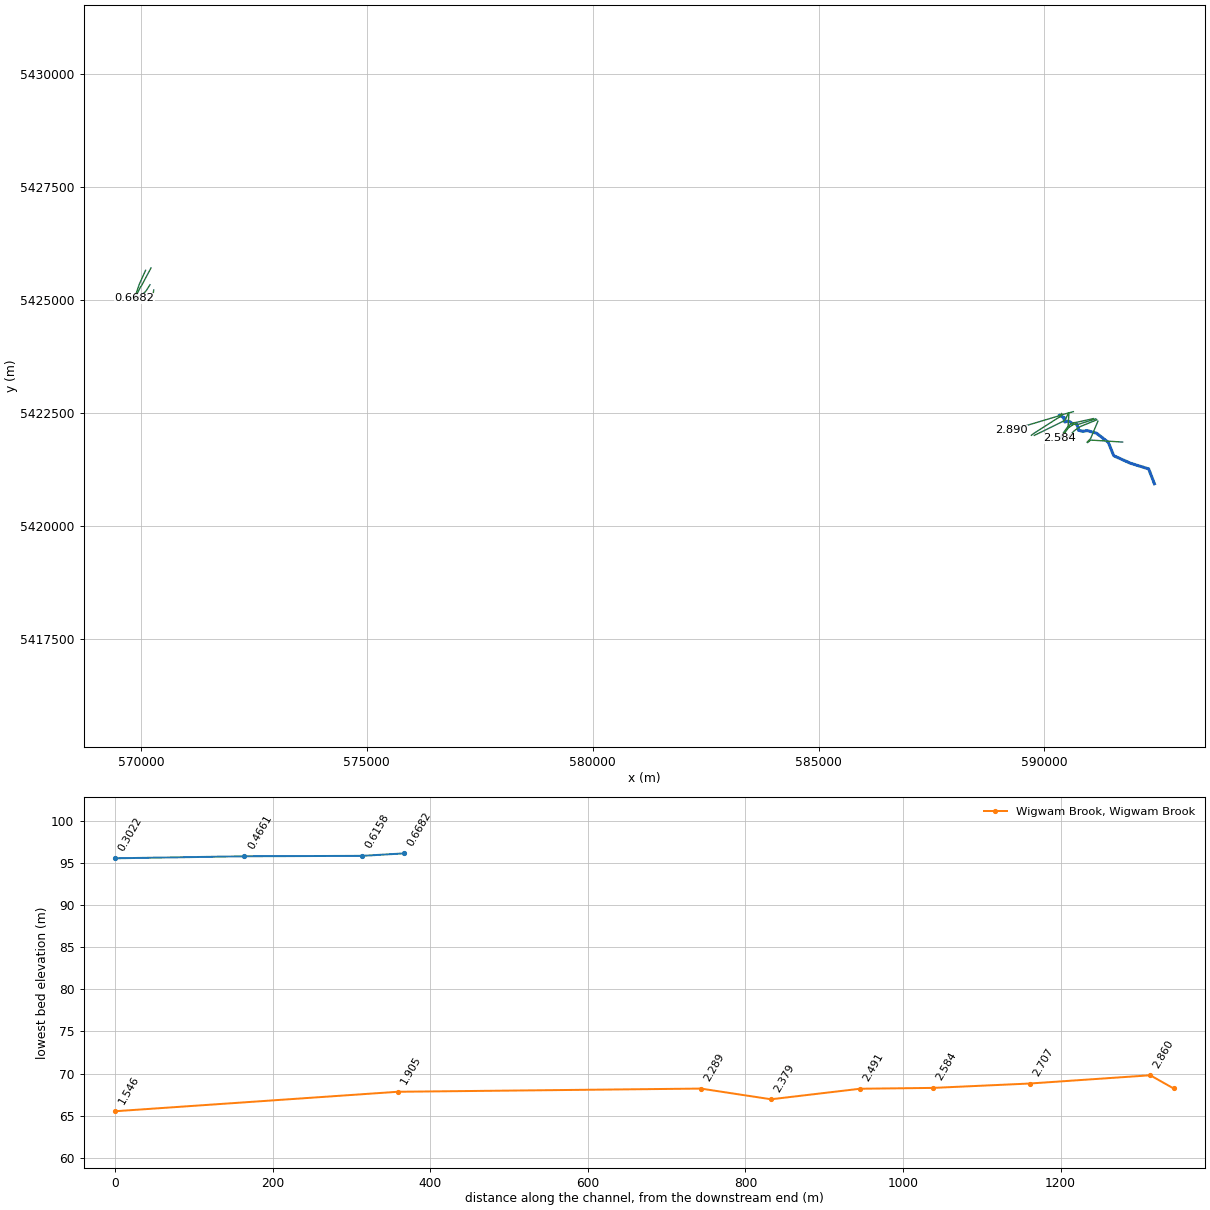
HEC-RAS study Unsteady_RAS.prj: Unsteady_RAS

--- Unsteady_RAS.g01 (geometry) --- (continued)

Type RM Length L Ch R = 3 ,.679    ,,,
Node Photo=.\FFSModel_Pictures\LRI_0_679.JPG
BEGIN DESCRIPTION:
Route 370 Buchans Hwy Bridge
END DESCRIPTION:
Bridge Culvert--1,0,-1,-1, 0
Deck Dist Width WeirC Skew NumUp NumDn MinLoCord MaxHiCord MaxSubmerge Is_Ogee
5,8.8,1.4,0, 200, 200, , , 0.98, 0, 3,3,,
       0   5.972  11.944  13.935  14.931  17.917  19.907  24.884  26.875  29.861
  31.852  33.843  39.815  41.806   53.75  54.746  57.732  64.699  65.695  68.681
  71.667  73.658  76.644  83.611  84.607  86.597  88.591  91.584  99.566 101.561
 105.552 113.534 117.525  119.52 126.504 132.491 135.484 138.477 142.468 143.466
 146.459 149.452 151.448 153.443 157.434 162.423 164.418 174.396  181.38 183.375
 188.364 193.353 197.344 205.325 209.316 213.307 215.303 220.291 227.276 235.257
 239.248 241.244 246.232 249.226 251.221 253.217 257.207 259.203 261.198 262.196
 266.187  269.18 274.169  278.16 284.146 285.144 287.139 289.135 297.117  300.11
 306.096 308.092 312.083 313.081 315.076 316.074 320.065 323.058 332.037 333.035
 334.033 336.028 337.026 338.024 339.022 341.017 342.015 343.013  344.01 345.008
 346.006 347.003 349.997 354.985 355.983 359.974 360.972 361.969 362.967 363.965
 364.963  365.96 368.954 369.951 370.949 372.945 373.942 377.933 379.929 382.922
 386.913 387.911 391.901 398.886 401.879 403.874 408.863 412.854 416.845  418.84
 422.831 424.827 428.818 432.808 434.804 437.796 442.784 447.771 451.761 454.753
 456.748 457.746 459.741 465.726 472.708  479.69 484.678 486.673  487.67  495.65
 500.638 502.633 506.623 510.613  511.61 512.607 514.602 522.582 524.577 537.545
 538.542 544.527 549.514 551.509 552.507 554.502 562.482 563.479 565.474 567.469
 569.464 571.459 574.452 577.444 578.441 581.434 586.421 589.414 590.411 595.399
 600.386 604.376 608.366 613.353 615.348 622.331 624.326 627.318 628.316 632.306
 634.301 638.291 644.275 649.263 653.253 655.248 656.245 660.235  662.23 665.223
 102.638 102.596 102.534 102.502 102.506  102.45 102.431 102.357 102.307 102.255
 102.234 102.179 102.069 102.047 101.827 101.816 101.739 101.604 101.599  101.53
 101.481 101.465 101.419 101.368 101.324 101.303   101.3 101.338 101.288 101.286
 101.249 101.217 101.186 101.191 101.157 101.156 101.188 101.174 101.191 101.213
 101.201 101.239 101.245 101.276 101.305 101.353 101.395 101.502 101.569 101.576
 101.633  101.67 101.735 101.828 101.853 101.902 101.904 101.941 101.948 101.921
 101.902 101.869 101.826  101.79 101.749 101.731 101.653 101.596 101.568 101.532
 101.445 101.391 101.329 101.273 101.207 101.219 101.197 101.202 101.194 101.213
 101.192 101.213 101.181 101.203 101.176 101.196 101.198 101.191 101.331 101.331
 101.331 101.331 101.331 101.331 101.331 101.331 101.331 101.331 101.331 101.331
 101.331 101.331 101.331 101.331 101.331 101.331 101.331 101.331 101.331 101.331
 101.331 101.331 101.331   101.1 101.123 101.104 101.074 101.043 101.008 100.983
 100.926 100.921 100.867  100.75 100.715 100.667 100.587 100.507  100.45 100.443
 100.388 100.379 100.337 100.337 100.314 100.311 100.292 100.292 100.307  100.33
 100.325 100.344 100.335 100.361 100.423 100.459 100.463 100.484  100.47 100.488
 100.485 100.467 100.487 100.498 100.509 100.484 100.493 100.486 100.498 100.506
 100.519 100.522 100.537 100.564 100.554 100.582 100.606 100.625 100.622  100.64
 100.635 100.653 100.659 100.676 100.664  100.68  100.67 100.699 100.685 100.676
 100.695 100.732 100.732 100.746 100.765 100.773 100.795 100.791 100.806 100.817
 100.833 100.837 100.868  100.86 100.883 100.869 100.898 100.922  100.92 100.942
                                                                                
                                                                                
                                                                                
                                                                                
                                                                                
                                                                                
                                                                                
                                                                                
                                                                          99.511
  99.511  99.511  99.511  99.511  99.511  99.511  99.511  99.511  99.511  99.511
  99.511  99.511  99.511  99.511  99.511  99.511  99.511  99.511  99.511  99.511
  99.511  99.511  99.511
                                                                                
                                                                                
                                                                                
                                                                                
                                                                                
                                                                                
                                                                                
                                                                                
      10  15.972  21.944  23.935  24.931  27.917  29.907  34.884  36.875  39.861
  41.852  43.843  49.815  51.806   63.75  64.746  67.732  74.699  75.695  78.681
  81.667  83.658  86.644  93.611  94.607  96.597  98.591 101.584 109.566 111.561
 115.552 123.534 127.525  129.52 136.504 142.491 145.484 148.477 152.468 153.466
 156.459 159.452 161.448 163.443 167.434 172.423 174.418 184.396  191.38 193.375
 198.364 203.353 207.344 215.325 219.316 223.307 225.303 230.291 237.276 245.257
 249.248 251.244 256.232 259.226 261.221 263.217 267.207 269.203 271.198 272.196
 276.187  279.18 284.169  288.16 294.146 295.144 297.139 299.135 307.117  310.11
 316.096 318.092 322.083 323.081 325.076 326.074 330.065 333.058 342.037 343.035
 344.033 346.028 347.026 348.024 349.022 351.017 352.015 353.013  354.01 355.008
 356.006 357.003 359.997 364.985 365.983 369.974 370.972 371.969 372.967 373.965
 374.963  375.96 378.954 379.951 380.949 382.945 383.942 387.933 389.929 392.922
 396.913 397.911 401.901 408.886 411.879 413.874 418.863 422.854 426.845  428.84
 432.831 434.827 438.818 442.808 444.804 447.796 452.784 457.771 461.761 464.753
 466.748 467.746 469.741 475.726 482.708  489.69 494.678 496.673  497.67  505.65
 510.638 512.633 516.623 520.613  521.61 522.607 524.602 532.582 534.577 547.545
 548.542 554.527 559.514 561.509 562.507 564.502 572.482 573.479 575.474 577.469
 579.464 581.459 584.452 587.444 588.441 591.434 596.421 599.414 600.411 605.399
 610.386 614.376 618.366 623.353 625.348 632.331 634.326 637.318 638.316 642.306
 644.301 648.291 654.275 659.263 663.253 665.248 666.245 670.235  672.23 675.223
 102.638 102.596 102.534 102.502 102.506  102.45 102.431 102.357 102.307 102.255
 102.234 102.179 102.069 102.047 101.827 101.816 101.739 101.604 101.599  101.53
 101.481 101.465 101.419 101.368 101.324 101.303   101.3 101.338 101.288 101.286
 101.249 101.217 101.186 101.191 101.157 101.156 101.188 101.174 101.191 101.213
 101.201 101.239 101.245 101.276 101.305 101.353 101.395 101.502 101.569 101.576
 101.633  101.67 101.735 101.828 101.853 101.902 101.904 101.941 101.948 101.921
 101.902 101.869 101.826  101.79 101.749 101.731 101.653 101.596 101.568 101.532
 101.445 101.391 101.329 101.273 101.207 101.219 101.197 101.202 101.194 101.213
 101.192 101.213 101.181 101.203 101.176 101.196 101.198 101.191 101.331 101.331
 101.331 101.331 101.331 101.331 101.331 101.331 101.331 101.331 101.331 101.331
 101.331 101.331 101.331 101.331 101.331 101.331 101.331 101.331 101.331 101.331
 101.331 101.331 101.331   101.1 101.123 101.104 101.074 101.043 101.008 100.983
 100.926 100.921 100.867  100.75 100.715 100.667 100.587 100.507  100.45 100.443
 100.388 100.379 100.337 100.337 100.314 100.311 100.292 100.292 100.307  100.33
 100.325 100.344 100.335 100.361 100.423 100.459 100.463 100.484  100.47 100.488
 100.485 100.467 100.487 100.498 100.509 100.484 100.493 100.486 100.498 100.506
 100.519 100.522 100.537 100.564 100.554 100.582 100.606 100.625 100.622  100.64
 100.635 100.653 100.659 100.676 100.664  100.68  100.67 100.699 100.685 100.676
 100.695 100.732 100.732 100.746 100.765 100.773 100.795 100.791 100.806 100.817
 100.833 100.837 100.868  100.86 100.883 100.869 100.898 100.922  100.92 100.942
                                                                                
                                                                                
                                                                                
                                                                                
                                                                                
                                                                                
                                                                                
                                                                                
                                                                          99.511
  99.511  99.511  99.511  99.511  99.511  99.511  99.511  99.511  99.511  99.511
  99.511  99.511  99.511  99.511  99.511  99.511  99.511  99.511  99.511  99.511
  99.511  99.511  99.511
                                                                                
                                                                                
                                                                                
                                                                                
                                                                                
                                                                                
                                                                                
                                                                                
BR Coef=-1 , 0 , 0 ,, 0 ,,,0.8,-1,,0,
WSPro=,,,, 1 ,,,, 0 ,,,, 0 ,,,,-1 ,-1 ,-1 , 0 , 0 , 0 , 0 , 0
BC Design=,, 0 ,, 0 ,,,,,,
BC HTab HWMax=104
BC Use User HTab Curves=0
BC User HTab FreeFlow(D)= 51
              0.          95.993           1.951          96.579
           4.877          96.741          11.705          96.985
          19.508          97.189          29.261          97.392
          39.015          97.563          48.769          97.718
          58.523           97.86          68.277          97.992
          78.031          98.119          87.784           98.24
          97.538          98.356         107.292          98.466
         117.046          98.573           126.8          98.671
         136.554          98.763         146.307          98.839
         156.061          98.917         165.815             99.
         175.569          99.084         185.323          99.167
         195.077          99.252          204.83          99.339
         214.584          99.431         230.392          99.571
           246.2          99.706         262.008          99.879
         277.816         100.013         293.624         100.141
         347.031         100.571         410.152         101.062
         484.755         101.644         572.927         101.793
         677.137         101.794         800.302         101.869
         945.869         101.975        1117.913          102.08
         1321.25         102.189        1561.573         102.296
        1845.607           102.4        2181.305         102.515
        2578.063         102.653        3046.988           102.8
        3601.205         102.957        4256.229         103.096
        5030.395         103.243        5945.375         103.382
         7026.78         103.644        8304.882         103.972
        8333.199            104.
BC User HTab Sub Curve(D)= 13
              0.          96.433           0.488          96.455
            0.63          96.468           0.772          96.481
           0.914          96.494           1.056          96.505
           1.198          96.517            1.34          96.528
           1.482           96.54           1.624          96.551
           1.766          96.563           1.909          96.574
           1.936          96.574
BC User HTab Sub Curve(D)= 12
              0.          96.584           0.826          96.591
           1.101          96.596           1.377          96.603
           1.652           96.61           1.927          96.619
           2.203          96.628           2.478          96.638
           2.753          96.649           3.029           96.66
           3.304          96.672           3.842          96.684
BC User HTab Sub Curve(D)= 15
              0.          96.735           1.656          96.743
           2.209          96.748           2.761          96.755
           3.313          96.763           3.865          96.773
           4.417          96.783           4.969          96.795
           5.521          96.807           6.074           96.82
           6.626          96.834           7.178          96.848
            7.73          96.863           8.282          96.879
           9.164          96.894
BC User HTab Sub Curve(D)= 14
              0.          96.887           2.727          96.894
           3.637            96.9           4.546          96.907
           5.455          96.916           6.364          96.927
           7.273          96.938           8.182          96.951
           9.091          96.965          10.001          96.981
           10.91          96.997          11.819          97.014
          12.728          97.032          14.208          97.051
BC User HTab Sub Curve(D)= 15
              0.          97.038           3.965          97.046
           5.286          97.052           6.608           97.06
           7.929          97.069           9.251           97.08
          10.572          97.092          11.894          97.106
          13.215          97.121          14.537          97.138
          15.858          97.156           17.18          97.175
          18.501          97.195          19.823          97.216
           21.83          97.238
BC User HTab Sub Curve(D)= 16
              0.          97.189           5.421          97.197
           7.227          97.204           9.034          97.212
          10.841          97.221          12.648          97.233
          14.455          97.246          16.262          97.261
          18.068          97.277          19.875          97.295
          21.682          97.315          23.489          97.335
          25.296          97.357          27.103           97.38
          28.909          97.404           31.44           97.43
BC User HTab Sub Curve(D)= 17
              0.          97.341           7.138          97.349
           9.517          97.356          11.896          97.364
          14.275          97.374          16.654          97.386
          19.034          97.401          21.413          97.416
          23.792          97.434          26.171          97.453
           28.55          97.475           30.93          97.497
          33.309          97.522          35.688          97.548
          38.067          97.575          40.446          97.604
          43.512          97.634
BC User HTab Sub Curve(D)= 17
              0.          97.492           9.097          97.501
          12.129          97.508          15.161          97.517
          18.194          97.528          21.226          97.541
          24.258          97.556          27.291          97.573
          30.323          97.593          33.355          97.614
          36.387          97.637           39.42          97.663
          42.452           97.69          45.484          97.719
          48.516          97.749          51.549          97.782
           55.49          97.816
BC User HTab Sub Curve(D)= 12
              0.          97.643           7.547          97.648
          15.095          97.661          22.642          97.682
          30.189          97.713          37.737          97.753
          45.284          97.803          52.831          97.861
          60.379          97.928          67.926          98.003
          68.277          98.007           69.41          98.007
BC User HTab Sub Curve(D)= 12
              0.          97.795           9.022          97.799
          18.045          97.813          27.067          97.836
          36.089          97.868          45.112          97.911
          54.134          97.963          63.157          98.026
          72.179          98.098          81.201           98.18
          87.784          98.245          88.218          98.245
BC User HTab Sub Curve(D)= 11
              0.          97.946          10.306           97.95
          20.611          97.964          30.917          97.987
          41.222          98.019          51.528          98.061
          61.833          98.113          72.139          98.176
          82.444           98.25           92.75          98.333
         103.625          98.425
BC User HTab Sub Curve(D)= 11
              0.          98.097          11.316          98.102
          22.631          98.114          33.947          98.135
          45.262          98.165          56.578          98.204
          67.893          98.252          79.209           98.31
          90.525          98.378          101.84          98.456
          114.39          98.544
BC User HTab Sub Curve(D)= 12
              0.          98.249          12.417          98.253
          24.834          98.264          37.252          98.284
          49.669          98.312          62.086          98.349
          74.503          98.394           86.92          98.449
          99.337          98.513         111.755          98.585
         124.172          98.666         135.868          98.756
BC User HTab Sub Curve(D)= 14
              0.            98.4          13.945          98.404
          27.891          98.415          41.836          98.435
          55.782          98.462          69.727          98.498
          83.673          98.543          97.618          98.597
         111.563          98.661         125.509          98.735
         139.454           98.82           153.4          98.915
         165.815          99.003           166.2          99.003
BC User HTab Sub Curve(D)= 14
              0.          98.551           15.53          98.555
           31.06          98.566           46.59          98.584
           62.12          98.611           77.65          98.645
           93.18          98.689         108.709          98.742
         124.239          98.806         139.769          98.881
         155.299          98.968         170.829          99.067
         185.323           99.17         185.642           99.17
BC User HTab Sub Curve(D)= 12
              0.          98.703          18.562          98.707
          37.124          98.719          55.686          98.739
          74.249          98.769          92.811          98.808
         111.373          98.859         129.935          98.921
         148.497          98.997         167.059          99.089
         185.621            99.2         204.436          99.336
BC User HTab Sub Curve(D)= 12
              0.          98.854          21.673          98.858
          43.347          98.871           65.02          98.894
          86.694          98.926         108.367           98.97
         130.041          99.026         151.714          99.098
         173.388          99.187         195.061          99.299
         214.584          99.435         214.999          99.435
BC User HTab Sub Curve(D)= 17
              0.          99.005           37.94          99.016
          50.587          99.024          63.234          99.035
           75.88          99.049          88.527          99.066
         101.174          99.085          113.82          99.108
         126.467          99.134         139.114          99.165
          151.76          99.199         164.407          99.238
         177.054          99.283         189.701          99.335
         202.347          99.394         214.994          99.463
         227.682          99.547
BC User HTab Sub Curve(D)= 16
              0.          99.157          29.794          99.165
           44.69          99.169          59.587          99.178
          74.484          99.191          89.381          99.206
         104.277          99.226         119.174          99.248
         134.071          99.275         148.968          99.306
         163.864          99.343         178.761          99.385
         193.658          99.434         208.555          99.492
         223.451          99.561         239.329          99.647
BC User HTab Sub Curve(D)= 16
              0.          99.308          35.532          99.317
          53.297          99.322          71.063          99.334
          88.829          99.349         106.595          99.368
         124.361          99.391         142.127          99.419
         159.892          99.452         177.658          99.492
         195.424          99.539          213.19          99.595
         230.956          99.664         248.722          99.778
         262.008          99.881         262.325          99.881
BC User HTab Sub Curve(D)= 17
              0.          99.459          45.374          99.468
          60.498          99.475          75.623          99.484
          90.748          99.495         105.872          99.509
         120.997          99.525         136.121          99.544
         151.246          99.566         166.371          99.591
         181.495           99.63          196.62          99.666
         211.745          99.707         226.869          99.756
         241.994          99.813         257.118          99.881
         272.442          99.967
BC User HTab Sub Curve(D)= 17
              0.          99.611          36.775           99.62
          55.163          99.625           73.55          99.636
          91.938          99.651         110.325          99.669
         128.713          99.691           147.1          99.717
         165.488          99.746         183.875          99.765
         202.263          99.804          220.65          99.849
         239.038          99.903         257.425          99.967
         275.813         100.045         293.624         100.143
         293.789         100.143
BC User HTab Sub Curve(D)= 16
              0.          99.762          38.257          99.772
          57.385          99.777          76.514          99.789
          95.642          99.804         114.771          99.823
         133.899          99.846         153.028          99.872
         172.156          99.902         191.285          99.937
         210.413          99.975         229.542         100.017
          248.67         100.064         267.799         100.095
         286.927         100.165          307.63         100.254
BC User HTab Sub Curve(D)= 17
              0.          99.913          39.739          99.923
          59.608          99.929          79.478          99.942
          99.347          99.958         119.217          99.977
         139.086         100.001         158.956         100.028
         178.825          100.06         198.695         100.095
         218.564         100.134         238.434         100.177
         258.303         100.224         278.173         100.276
         298.042         100.332         317.912          100.37
         336.299         100.485
BC User HTab Sub Curve(D)= 17
              0.         100.064          41.221         100.075
          61.831         100.081          82.442         100.094
         103.052         100.111         123.663         100.131
         144.273         100.156         164.884         100.184
         185.494         100.216         206.105         100.253
         226.715         100.293         247.326         100.338
         267.936         100.387         288.546         100.441
         309.157         100.503         329.767         100.571
         350.729           100.6
BC User HTab Sub Curve(D)= 18
              0.         100.216           43.81         100.227
          65.715         100.234          87.621         100.248
         109.526         100.266         131.431         100.289
         153.336         100.316         175.241         100.347
         197.146         100.382         219.051         100.422
         240.957         100.468         262.862         100.519
         284.767         100.576         306.672         100.639
         328.577         100.707         350.482         100.781
         372.387          100.86          394.49          100.94
BC User HTab Sub Curve(D)= 16
              0.         100.367          36.085         100.372
           72.17         100.388         108.255         100.415
          144.34         100.453         180.425         100.504
          216.51         100.566         252.595         100.643
          288.68         100.733         324.765         100.836
         360.849         100.954         396.934         101.087
         433.019         101.561         469.104         101.622
         484.755         101.646         486.212         101.646
BC User HTab Sub Curve(D)= 23
              0.         100.518           53.76         100.533
           80.64         100.544          107.52         100.564
           134.4         100.591          161.28         100.625
          188.16         100.666          215.04         100.713
          241.92         100.767           268.8         100.828
          295.68         100.896          322.56         100.971
          349.44         101.055          376.32         101.147
           403.2         101.247          430.08         101.556
         432.968         101.563          456.96         101.605
         467.829         101.623          483.84         101.648
         485.812         101.651         486.212         101.651
         488.993         101.651
BC User HTab Sub Curve(D)= 24
              0.          100.67          30.459         100.673
          60.919         100.682          91.378         100.698
         121.838         100.722         152.297         100.756
         182.757         100.802         213.216         100.853
         243.676         100.915         274.135         100.985
         304.595         101.062         335.054         101.149
         365.514         101.245         395.973         101.351
         426.433         101.549         430.018         101.558
         432.968         101.565         456.892         101.608
         464.689         101.621          483.84          101.65
         485.812         101.653         487.351         101.654
         488.993         101.654         490.802         101.654
BC User HTab Sub Curve(D)= 22
              0.         100.821          35.281         100.824
          70.562         100.834         105.842         100.851
         141.123         100.878         176.404         100.919
         211.685         100.976         246.966         101.057
         282.247         101.142         317.527         101.237
         352.808         101.338         388.089         101.442
          423.37         101.544         426.286         101.551
         430.018          101.56         432.968         101.567
         458.651         101.614         464.689         101.623
          483.84         101.651         485.812         101.654
         487.351         101.656         492.717         101.657
BC User HTab Sub Curve(D)= 20
              0.         100.972          61.041         100.982
          91.561         100.987         122.081            101.
         152.602         101.019         183.122         101.046
         213.642         101.085         244.162         101.139
         274.683         101.226         305.203         101.331
         335.723         101.416         366.244         101.501
         396.764         101.586         442.816         101.602
         457.805         101.615         461.978         101.623
         485.812         101.656         488.325         101.659
         492.717         101.661         494.527         101.661
BC User HTab Sub Curve(D)= 12
              0.         101.124          71.851         101.133
         107.777         101.138         143.702          101.15
         179.628         101.167         215.553         101.189
         251.479         101.224         287.405         101.279
          323.33         101.448         359.256         101.602
         395.181         101.705         522.545         101.708
BC User HTab Sub Curve(D)= 26
              0.         101.275          82.206         101.281
         109.608         101.286         137.009         101.292
         164.411           101.3         191.813          101.31
         219.215         101.322         246.617         101.336
         274.019         101.352         301.421         101.372
         308.641         101.382          323.33         101.449
         328.822         101.474         329.535         101.477
         356.224         101.592         356.937         101.595
         359.256         101.603         383.626         101.675
         384.689         101.678         395.181         101.706
         411.028         101.708          438.43         101.709
         465.832         101.709         493.234          101.71
         522.545         101.711         524.355         101.711
BC User HTab Sub Curve(D)= 27
              0.         101.426          93.287         101.434
         124.383         101.435         155.479          101.44
         186.574         101.447          217.67         101.455
         248.766         101.464         279.862         101.475
         310.957         101.488         334.475         101.503
         342.053         101.534         342.765         101.537
         356.224         101.593         356.937         101.596
         359.256         101.605         373.149         101.647
         374.189          101.65         383.626         101.676
         384.689         101.679         395.181         101.708
         404.245          101.71          429.58         101.713
          435.34         101.713         466.436         101.713
         497.532         101.713         524.355         101.714
         526.165         101.714
BC User HTab Sub Curve(D)= 21
              0.         101.578         138.844         101.584
         173.555         101.587         208.266         101.592
         242.977         101.597         277.688         101.603
         312.399         101.611          347.11         101.619
         363.501         101.627         381.821         101.674
         382.921         101.677         384.689         101.681
         395.181         101.709         404.245         101.712
         416.532         101.715         441.861         101.718
         451.243         101.718         485.954         101.718
         520.665         101.718         526.165         101.718
         528.593         101.718
BC User HTab Sub Curve(D)= 13
              0.         101.729         150.667         101.733
         263.667         101.742         301.334         101.747
         339.001         101.752         376.667         101.757
         414.334         101.764         452.001         101.771
         489.667         101.779         527.334         101.788
         565.001         101.797         572.927         101.798
         685.858         101.798
BC User HTab Sub Curve(D)= 12
              0.          101.88         246.785         101.887
         329.046         101.892         411.308         101.899
         493.569         101.909         575.831          101.92
         658.092         101.934         740.354         101.952
         822.615         101.972         904.877         101.996
         987.138         102.024        1080.156         102.057
BC User HTab Sub Curve(D)= 14
              0.         102.032         281.509          102.04
         375.346         102.041         469.182         102.046
         563.019         102.053         656.855         102.061
         750.692         102.072         844.528         102.084
         938.365         102.099        1032.201         102.117
        1126.038         102.138        1219.874         102.162
         1321.25         102.189         1322.29         102.189
BC User HTab Sub Curve(D)= 14
              0.         102.183         425.331         102.189
         531.664         102.193         637.997         102.197
          744.33         102.203         850.663         102.209
         956.996         102.218        1063.329         102.228
        1169.662          102.24        1275.994         102.254
        1382.327          102.27         1488.66          102.29
        1561.573         102.304        1582.075         102.304
BC User HTab Sub Curve(D)= 11
              0.         102.334         598.857          102.34
         958.172         102.351        1077.943         102.357
        1197.715         102.362        1317.486          102.37
        1437.258         102.379        1557.029         102.389
        1676.801         102.401        1796.572         102.416
        1941.397         102.432
BC User HTab Sub Curve(D)= 11
              0.         102.486         670.273         102.489
        1206.492         102.499        1340.547         102.503
        1474.602         102.507        1608.656         102.512
        1742.711         102.518        1876.766         102.526
         2010.82         102.533        2144.875         102.542
         2295.62         102.555
BC User HTab Sub Curve(D)= 9
              0.         102.637         896.745         102.641
        1494.574         102.649        1942.947         102.659
        2092.404         102.665        2241.862          102.67
        2391.319         102.676        2540.776         102.683
        2727.614           102.7
BC User HTab Sub Curve(D)= 8
              0.         102.788        1242.539         102.792
        1988.063         102.802        2236.571         102.803
        2485.079         102.806        2733.586         102.812
        2982.094         102.822        3210.974         102.847
BC User HTab Sub Curve(D)= 5
              0.          102.94         2190.75         102.943
        3286.125         102.948        3559.969         102.951
         3579.83         102.951
BC User HTab Sub Curve(D)= 2
              0.         103.091        4245.216         103.094
BC User HTab Sub Curve(D)= 3
              0.         103.242        5030.395         103.245
        5048.444         103.245
BC User HTab Sub Curve(D)= 3
              0.         103.394        5945.375         103.397
        6006.935         103.397
BC User HTab Sub Curve(D)= 2
              0.         103.545        6630.625         103.548
BC User HTab Sub Curve(D)= 2
              0.         103.696        7241.876         103.699
BC User HTab Sub Curve(D)= 2
              0.         103.847        7831.658         103.851

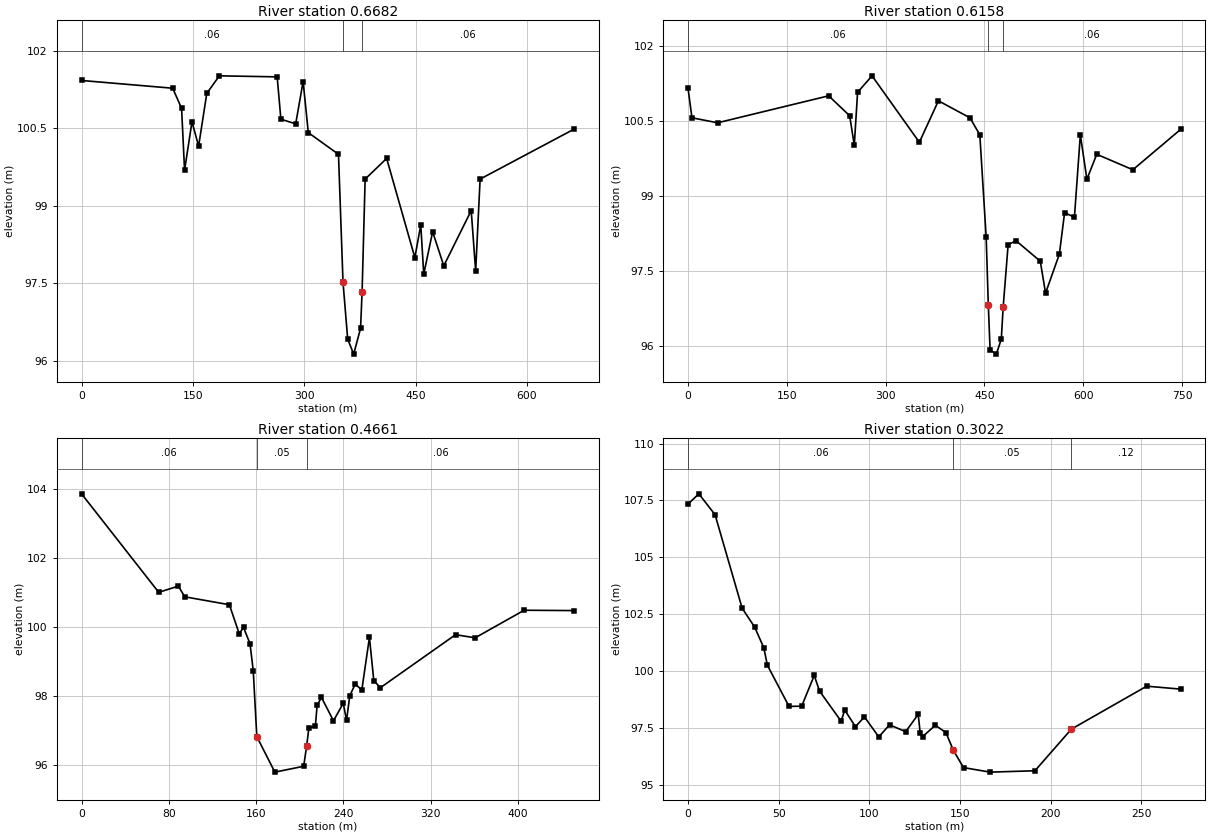
Type RM Length L Ch R = 1 ,0.6682  ,55.35,52.41,48.81
BEGIN DESCRIPTION:
DS of Buchans Hwy Bridge - LR04 (SEM 2019)
END DESCRIPTION:
XS GIS Cut Line= 4
  570104.6974036 5425666.3805831  569965.1030036 5425355.8259831
  569950.6520036 5425312.5279831  569860.3744036 5425049.7457831
#Sta/Elev= 30
       0  101.43  122.81  101.28   134.8  100.89  138.79   99.69  148.78  100.63
  157.76  100.16  168.75  101.18  185.72  101.52   263.6   101.5  268.59  100.68
  288.56  100.59  298.55  101.41  305.54  100.42  346.21     100  352.32   97.52
  358.64   96.42  366.68   96.13  375.97   96.63  378.03   97.34  382.13   99.52
  411.12   99.92   449.1      98   457.1   98.63  461.09   97.68  473.09    98.5
  488.08   97.84  525.06   98.91  531.06   97.74  537.05   99.52  663.99  100.49
#Mann= 3 , 0 , 0
       0     .06       0  352.32     .05       0  378.03     .06       0
Bank Sta=352.32,378.03
XS Rating Curve= 0 ,0
Exp/Cntr=0.3,0.1

Type RM Length L Ch R = 1 ,0.6158  ,149.73,149.64,151.5
BEGIN DESCRIPTION:
LR03  (SEM 2019)
END DESCRIPTION:
XS GIS Cut Line= 4
  570224.8816036 5425718.4011831  570014.6690036 5425324.9919831
  569991.8290036 5425294.6229831  569873.7157036 5425058.3668831
#Sta/Elev= 30
       0  101.16    5.99  100.57    44.9  100.47  213.55  101.01  245.48  100.61
  252.46  100.02  257.45  101.08   279.4  101.41  351.25  100.08  380.19  100.91
  428.09  100.57  443.05  100.23   452.7   98.18  455.93   96.83  458.66   95.92
  468.13   95.84  475.68   96.14   478.5   96.78  486.04   98.03     498   98.11
  534.88    97.7  542.86   97.06  563.79   97.84  571.76   98.67  586.71   98.58
  595.68  100.23  605.65   99.34   620.6   99.84  675.42   99.53  748.18  100.34
#Mann= 3 , 0 , 0
       0     .06       0  455.93     .05       0   478.5     .06       0
Bank Sta=455.93,478.5
XS Rating Curve= 0 ,0
Exp/Cntr=0.3,0.1

Type RM Length L Ch R = 1 ,0.4661  ,171.87,163.89,167.83
BEGIN DESCRIPTION:
School Rd - LR02 (SEM 2019)
END DESCRIPTION:
XS GIS Cut Line= 4
  570202.2855036 5425346.1416831  570124.1513036 5425223.3892831
  570081.7383036 5425173.5372831  569887.1582036 5425031.6998831
#Sta/Elev= 30
       0  103.87   70.76  101.01    88.7  101.19   94.68  100.88  135.54  100.65
  144.51   99.81  148.49   99.99  154.44   99.52  157.39   98.74  160.68   96.82
  177.22   95.79  203.64   95.96   206.4   96.56  208.37   97.06  214.38   97.14
  215.96   97.73  219.95   97.96  230.95   97.28  239.94   97.79  242.93   97.29
  245.93   98.01  250.93   98.35  256.92   98.17  263.92    99.7  267.91   98.45
  273.91   98.24  342.85   99.78  360.83   99.69  405.79  100.49  451.75  100.48
#Mann= 3 , 0 , 0
       0     .06       0  160.68     .05       0   206.4     .06       0
Bank Sta=160.68,206.4
XS Rating Curve= 0 ,0
Exp/Cntr=0.3,0.1

Type RM Length L Ch R = 1 ,0.3022  ,182.29,302.23,152.5
BEGIN DESCRIPTION:
LR01  (SEM 2019)
END DESCRIPTION:
XS GIS Cut Line= 5
  570284.2231036 5425229.9242831  570276.5901036 5425166.7154831
  570243.0550036 5425114.2269831  570200.3580036 5425058.0029831
  570163.3838036 5424992.5414831
#Sta/Elev= 30
       0  107.34    5.97  107.79   14.92  106.87   29.84  102.76   36.81  101.92
   41.78  101.02   43.77  100.25   55.71   98.44   62.67   98.45    69.6    99.8
   72.57   99.11   84.43   97.79   86.41   98.28   92.34   97.55   97.28   97.98
  105.19    97.1  111.12   97.63  120.02   97.33  126.95   98.09  128.01   97.29
  129.33   97.11  136.39   97.61  142.22   97.29  146.26   96.52  151.93   95.75
  166.55   95.55  191.32   95.61  211.39   97.44  252.94   99.33  271.74    99.2
#Mann= 3 , 0 , 0
       0     .06       0  146.26     .05       0  211.39     .12       0
Bank Sta=146.26,211.39
XS Rating Curve= 0 ,0
Exp/Cntr=0.3,0.1

River Reach=Wigwam Brook    ,Wigwam Brook
Reach XY= 30
590332.2576035985422454.28008309590338.6076035985422444.75508309
590366.1243035985422444.75508309590377.2368035985422441.05088309
590392.5827035985422423.05918309590435.4453035985422410.88828309
590439.6786035985422402.95078309590439.6786035985422387.60498309
590434.9161035995422365.37988309590444.4411035985422342.09648309
590442.8536035995422321.98818309590446.0286035985422312.46308309
590455.0245035985422307.70058309590496.8287035985422327.27978309
590538.6330035985422322.35858309590571.9706035985422308.86478309
590598.1644035985422285.84598309590622.7707035985422273.14598309
590675.9520035985422277.90848309590708.4958035985422266.00218309
590735.4834035985422205.67708309590755.3272035985422124.71438309
590852.1649035985422101.69558309590941.0650035985422119.95188309
591152.4675035985422059.89138309591411.7597035985421858.80768309
591533.4683035985421562.47368309591894.6253035985421399.09318309
592306.0532035995421270.76998309592433.2195035985420942.02968309

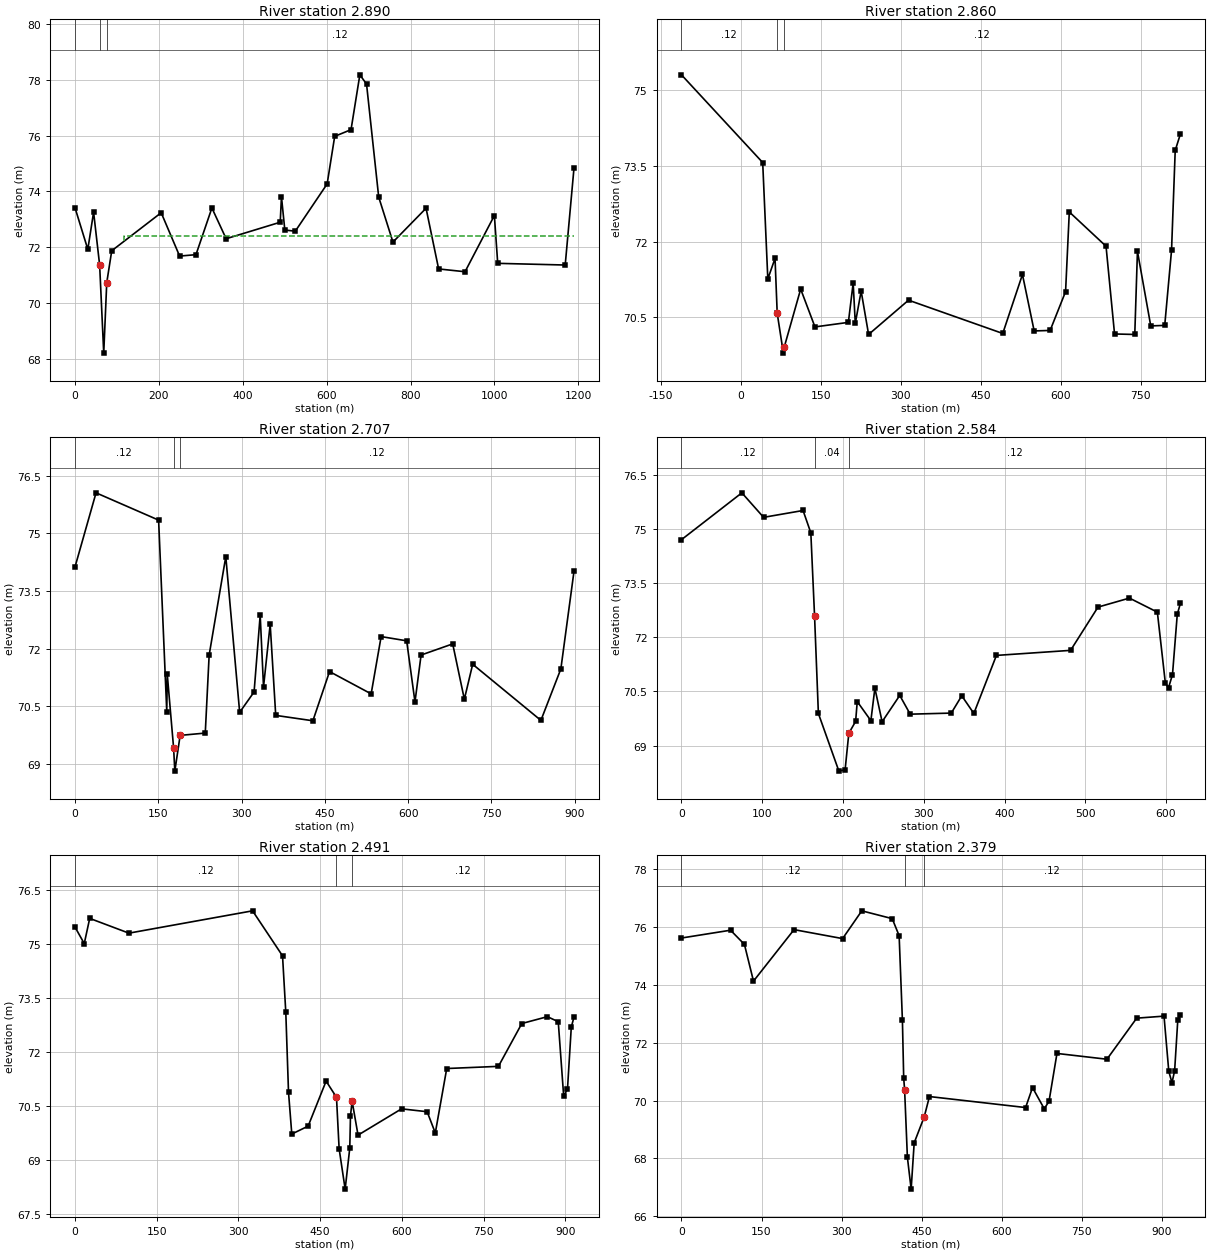
Type RM Length L Ch R = 1 ,2.890   ,24.28,29.72,40.78
BEGIN DESCRIPTION:
DS of Wigwam Brook T'Railway - WB07 (SEM 2019)
END DESCRIPTION:
XS GIS Cut Line= 4
  590379.4059036 5422496.5255831  590347.3280036 5422454.0299831
  590318.3870036 5422444.9039831  589258.6286036 5422128.2248831
#Sta/Elev= 30
       0   73.42   30.57   71.93   44.37   73.26   58.76   71.37   68.52   68.22
   75.71   70.74   87.59   71.88  205.49   73.24  249.45   71.69  288.42   71.74
  326.38   73.41  360.36   72.31  489.25    72.9  492.24   73.81  500.24   72.62
  525.22   72.58  601.15   74.27  619.14   75.97   658.1   76.21  679.09   78.17
  695.07   77.84  724.05    73.8  758.02   72.19  836.95    73.4  866.92   71.23
  929.87   71.13  999.81   73.14  1007.8   71.43 1168.67   71.37 1189.65   74.84
#Mann= 3 , 0 , 0
       0     .12       0   58.76     .04       0   75.71     .12       0
#XS Ineff= 2 , 0
                          117.02           72.39
Permanent Ineff=
       F       F
Bank Sta=58.76,75.71
XS Rating Curve= 0 ,0
Exp/Cntr=0.3,0.1

Type RM Length L Ch R = 1 ,2.860   ,153.38,152.89,153.26
BEGIN DESCRIPTION:
WB06 (SEM 2019)
END DESCRIPTION:
XS GIS Cut Line= 6
  590639.2349202 5422537.8042778  590383.1908036 5422469.0381831
  590348.7430036 5422427.2109831  590280.9807036 5422387.7816831
  589765.7279036 5422057.8942831  589710.0985224 5422015.1363391
#Sta/Elev= 30
  -111.7   75.31   40.72   73.57   50.33   71.26   63.87   71.67   67.94   70.58
   79.54   69.79   81.16   69.91  111.98   71.06  138.77   70.31  201.47    70.4
  210.46   71.18  214.45   70.38  225.44   71.02  239.42   70.16  314.33   70.84
  491.13   70.18  528.08   71.35  550.06   70.23  580.02   70.24  608.99   71.01
  615.98   72.59   684.9   71.91  700.88   70.17  738.83   70.16  743.83   71.81
   768.8   70.33  795.02   70.34  807.81   71.83   814.7   73.81  824.55   74.14
#Mann= 3 , 0 , 0
  -111.7     .12       0   67.94     .04       0   81.16     .12       0
#XS Ineff= 2 , 0
Permanent Ineff=
       F       F
Bank Sta=67.94,81.16
XS Rating Curve= 0 ,0
Exp/Cntr=0.3,0.1

Type RM Length L Ch R = 1 ,2.707   ,129.04,122.82,125.65
BEGIN DESCRIPTION:
WB05 (SEM 2019)
END DESCRIPTION:
XS GIS Cut Line= 6
  590527.0437036 5422504.4631831  590467.2390036 5422365.1679831
  590422.6630036 5422329.5809831  589841.3779036 5422044.0696831
  589803.0290036 5422026.0365831  589774.4238361 5422012.5853539
#Sta/Elev= 30
       0   74.12    37.9   76.05  150.59   75.34  165.26   70.36  166.17   71.33
  177.66    69.4  179.77   68.81  189.37   69.74  234.61    69.8   241.6   71.83
  271.57   74.39  296.55   70.34  322.52   70.87  333.51   72.87  339.51      71
   351.5   72.63  361.49   70.26  428.42   70.12   458.4    71.4  533.33   70.82
  551.31   72.31  597.27    72.2  612.25   70.61  623.24   71.83  680.19   72.12
  701.17   70.68  716.16   71.59  839.04   70.13  874.97   71.47  898.63   74.01
#Mann= 3 , 0 , 0
       0     .12       0  177.66     .04       0  189.37     .12       0
Bank Sta=177.66,189.37
XS Rating Curve= 0 ,0
Exp/Cntr=0.3,0.1

Type RM Length L Ch R = 1 ,2.584   ,174.27,92.75,71.69
BEGIN DESCRIPTION:
WB04 (SEM 2019)
END DESCRIPTION:
XS GIS Cut Line= 6
  590542.1249036 5422507.6381831  590531.5320036 5422349.4479831
  590525.7900036 5422292.6219831  590524.6624036 5422217.1250831
  590358.6169036 5421986.3764831  590335.3717036 5421950.8947831
#Sta/Elev= 30
       0   74.71   74.79   76.01  101.71   75.33  150.57   75.52  160.19    74.9
  164.79    72.6  169.54   69.89  194.93   68.29  202.65   68.33  207.22   69.34
  215.66   69.67  217.65   70.22  234.54   69.69   239.5   70.59  248.45   69.66
   270.3   70.39  283.22   69.87  334.09    69.9  347.06   70.38  362.03   69.89
  389.98    71.5  481.81   71.64  515.75   72.84  554.67   73.09  589.26    72.7
  599.12   70.74  603.07    70.6     608   70.97  613.92   72.64  617.87   72.95
#Mann= 3 , 0 , 0
       0     .12       0  164.79     .04       0  207.22     .12       0
Bank Sta=164.79,207.22
XS Rating Curve= 0 ,0
Exp/Cntr=0.3,0.1

Type RM Length L Ch R = 1 ,2.491   ,55.37,112.9,116.52
BEGIN DESCRIPTION:
WB03 (SEM 2019)
END DESCRIPTION:
XS GIS Cut Line= 5
  591085.0510036 5422384.6066831  590620.2550036 5422282.1389831
  590585.1120036 5422276.3849831  590377.0103036 5421991.7617831
  590349.6592036 5421947.7197831
#Sta/Elev= 30
       0   75.47      17   75.01      27   75.71   98.99    75.3  325.97   75.92
  380.97   74.67  386.96    73.1  391.96   70.88  397.96   69.72  427.96   69.94
  460.96   71.19  480.01   70.74  484.86   69.31  495.91   68.19  504.41   69.33
  505.71   70.23  508.74   70.63  519.56   69.69  599.47   70.42  646.42   70.34
   661.4   69.75  682.38   71.54  777.27    71.6  820.22   72.79  867.15   72.98
  887.09   72.84  897.06   70.77  904.04   70.97  911.02   72.69     916   72.97
#Mann= 3 , 0 , 0
       0     .12       0  480.01     .04       0  508.74     .12       0
Bank Sta=480.01,508.74
XS Rating Curve= 0 ,0
Exp/Cntr=0.3,0.1

Type RM Length L Ch R = 1 ,2.379   ,80.97,89.26,127.2
BEGIN DESCRIPTION:
WB02 (SEM 2019)
END DESCRIPTION:
XS GIS Cut Line= 6
  591135.8511036 5422379.0503831  590752.4691036 5422258.4001831
  590642.9314036 5422256.0188831  590528.6312036 5422179.8187831
  590387.9893036 5421983.5383831  590366.0634036 5421944.5447831
#Sta/Elev= 30
       0   75.62   91.98   75.89  117.98    75.4  134.97   74.13  210.96   75.91
  301.94    75.6  337.93   76.56  394.92   76.29   407.9    75.7  414.04   72.77
  416.44   70.78  418.17   70.37  423.36   68.04  430.41   66.94  436.09   68.54
  454.95   69.44  464.67   70.14  644.87   69.76  657.82   70.45  679.73   69.72
   688.7   69.97  703.64   71.63  797.27   71.43  853.05   72.85  904.24   72.92
  913.19   71.01  919.15   70.62  924.12   71.03  930.09    72.8  935.06   72.97
#Mann= 3 , 0 , 0
       0     .12       0  418.17     .04       0  454.95     .12       0
Bank Sta=418.17,454.95
XS Rating Curve= 0 ,0
Exp/Cntr=0.3,0.1

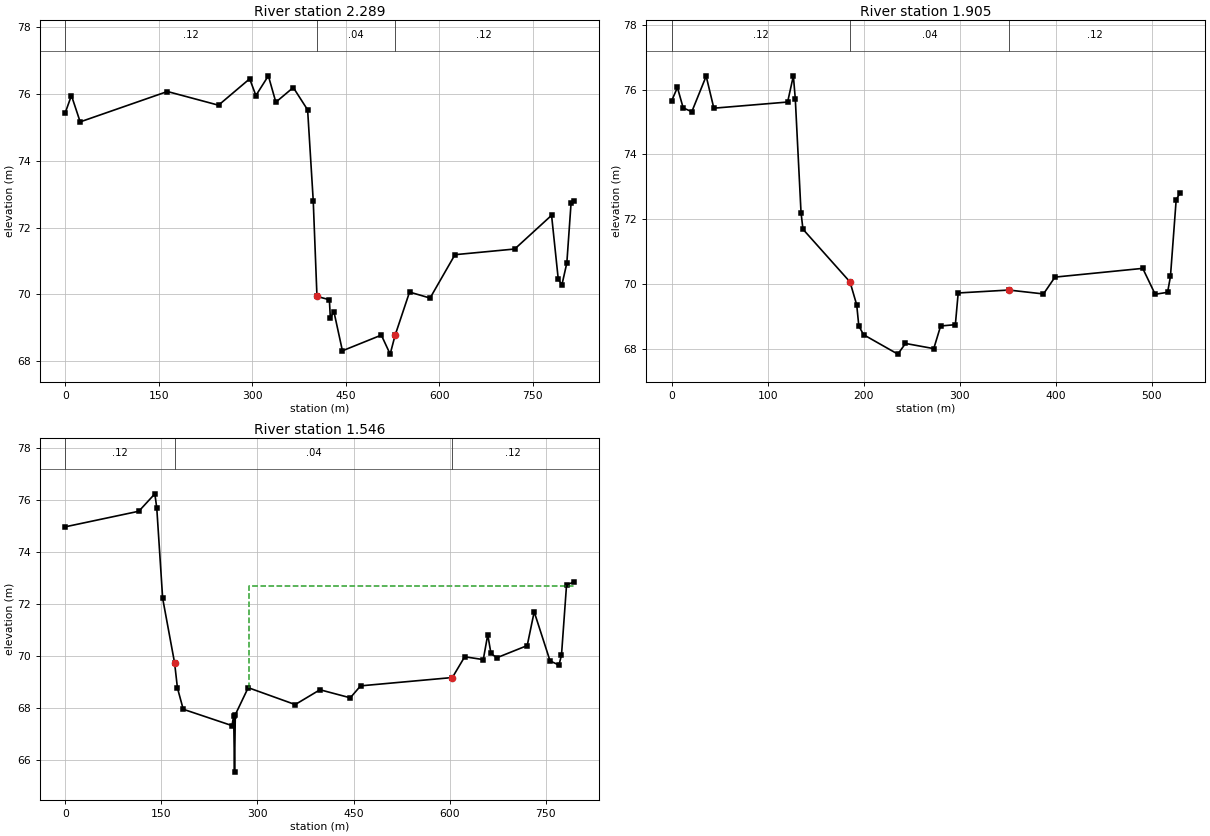
Type RM Length L Ch R = 1 ,2.289   ,330.66,384.77,394.78
BEGIN DESCRIPTION:
WB01 (SEM 2019)
END DESCRIPTION:
XS GIS Cut Line= 5
  591158.0762036 5422357.6190831  590788.1879036 5422206.0125831
  590654.8377036 5422111.5560831  590510.9583036 5421959.9827831
  590481.4220036 5421928.6696831
#Sta/Elev= 30
       0   75.44    9.99   75.96   23.99   75.17   163.9   76.08  245.85   75.67
  295.82   76.46  305.81   75.96   325.8   76.55  337.79   75.76  365.77    76.2
  388.76   75.53  397.75   72.81  403.74   69.94  423.67   69.84  425.16    69.3
  430.97   69.48  444.56   68.31  506.98   68.78  521.12   68.21  528.99   68.77
  552.21   70.07  585.13   69.89  625.05   71.19  720.87   71.36  779.98   72.37
  790.74   70.45  796.61   70.29  804.44   70.94  811.29   72.75   815.2    72.8
#Mann= 3 , 0 , 0
       0     .12       0  403.74     .04       0  528.99     .12       0
Bank Sta=403.74,528.99
XS Rating Curve= 0 ,0
Exp/Cntr=0.3,0.1

Type RM Length L Ch R = 1 ,1.905   ,547.02,358.45,129.45
BEGIN DESCRIPTION:
NA04 (SEM 2019)
END DESCRIPTION:
XS GIS Cut Line= 3
  591183.2315036 5422327.8489831  591020.1759036 5421940.5919831
  590943.3854036 5421862.5237831
#Sta/Elev= 30
       0   75.66    5.99   76.07   11.98   75.44   20.97   75.32   35.95   76.42
   43.94   75.43  120.82   75.62  126.81   76.43  128.81   75.72   134.8    72.2
   136.8   71.69  185.85   70.06  192.82   69.35  195.01    68.7  199.97   68.43
  235.66   67.83  243.65   68.16   273.1      68  280.27    68.7   295.6   68.74
  298.56   69.72  351.38   69.81  387.44   69.69  399.42   70.21  490.87   70.48
  503.81   69.68  516.75   69.74  519.74   70.23  525.71    72.6  529.69   72.81
#Mann= 3 , 0 , 0
       0     .12       0  185.85     .04       0  351.38     .12       0
Bank Sta=185.85,351.38
XS Rating Curve= 0 ,0
Exp/Cntr=0.3,0.1

Type RM Length L Ch R = 1 ,1.546   ,144.01,151.96,265.45
BEGIN DESCRIPTION:
US of TCH - NA03 (SEM 2019)
END DESCRIPTION:
XS GIS Cut Line= 3
  591729.5972036 5421864.8272831  591021.8275036 5421908.9816831
  590957.1438036 5421855.1153831
#Sta/Elev= 30
       0   74.96   114.9   75.56  139.88   76.23  142.88   75.69  152.08   72.21
  170.73   69.72  175.14   68.76  184.18   67.94  260.29   67.31  262.92   67.69
  264.24   65.52  265.46   67.73   285.6   68.77  358.92   68.12   397.6   68.69
  444.88   68.38     461   68.84   604.2   69.16  623.48   69.96  652.46   69.85
  659.45   70.81  664.45   70.09  673.44   69.92  721.03   70.39  731.92   71.69
  756.68    69.8  770.54   69.64  774.51   70.02  782.43   72.73  793.32   72.83
#Mann= 3 , 0 , 0
       0     .12       0  170.73     .04       0   604.2     .12       0
#XS Ineff= 2 , 0
       0                   286.8       0    72.7
Permanent Ineff=
       F       T
Bank Sta=170.73,604.2
XS Rating Curve= 0 ,0
Exp/Cntr=0.3,0.1