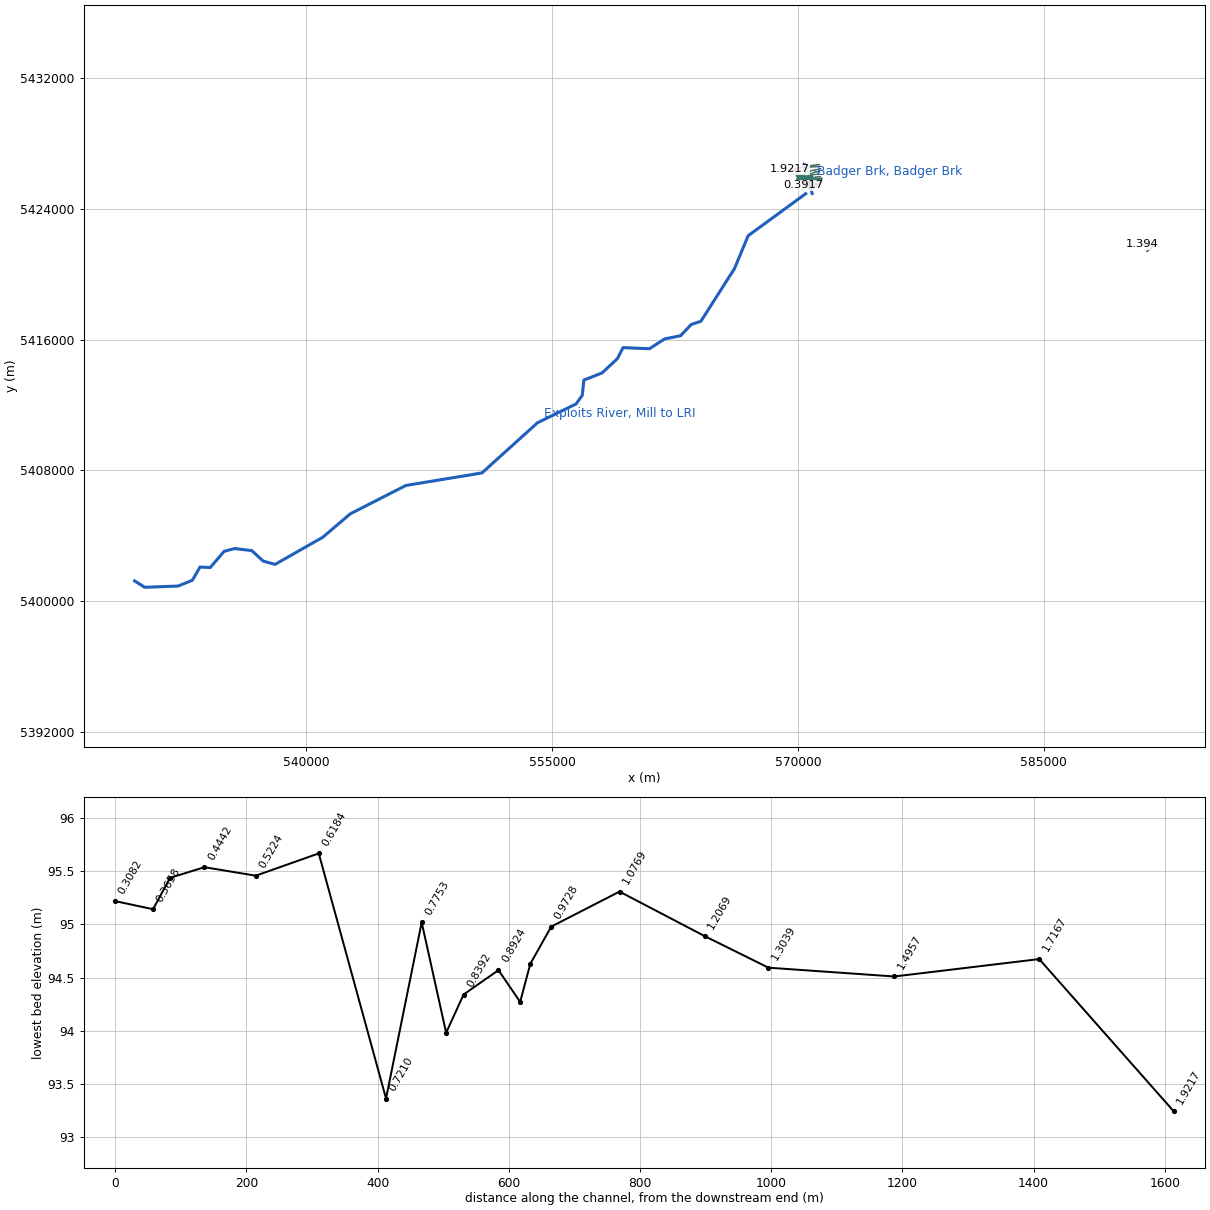
HEC-RAS study Unsteady_RAS.prj: Unsteady_RAS

--- Unsteady_RAS.g01 (geometry) --- (continued)

Type RM Length L Ch R = 2 ,1.424   ,,,
BEGIN DESCRIPTION:
Trans Canada Highway at North Angle
END DESCRIPTION:
Bridge Culvert--1,0,-1,-1, 0
Deck Dist Width WeirC Skew NumUp NumDn MinLoCord MaxHiCord MaxSubmerge Is_Ogee
100,24.4,1.4,0, 100, 100, , , 0.98, 0, 3,3,,
       0   2.997  10.987  14.983   25.97  32.962  39.953  61.928  77.909  89.895
  91.893  99.884 105.877 109.872 114.866 117.863 121.858 125.853  128.85 130.847
 140.836 143.832 146.829 156.817 160.813 164.808 173.797 176.794 181.788 183.786
 192.775 194.773 200.766 202.764  214.75 223.739 247.711 253.704 261.695 266.689
 276.677 281.672 289.662 292.659 296.654 301.648 303.646 324.621  334.61 340.603
 354.587 358.582 362.577 365.574 382.554 391.543 398.535 400.533 407.525 414.517
 419.511 430.498 435.492  437.49 442.484 458.465  463.46 466.456 472.449 484.435
 500.416 508.407 519.394  531.38 532.379 539.371 552.356 560.347 570.335 587.315
 601.299 604.295  617.28 623.273  634.26  643.25 647.245 652.239 659.231 670.218
 682.204 685.201 692.193 698.186 700.183 704.179 716.165 724.156 730.149  737.14
  73.232  73.238   73.19  73.189  73.115  73.111   73.06  73.017  72.927  72.893
  72.862  72.825  72.824  72.762  72.778  72.723  72.745  72.723  72.744   72.71
  72.702  72.726   72.69  72.692  72.656  72.666  72.586  72.619  72.586  72.609
  72.593  72.564  72.597  72.577  72.602  72.583  72.622  72.607   72.63  72.623
  72.682  72.666  72.712  72.693  72.714  72.693  72.713  72.664  72.672  72.697
  72.688  72.696  72.661   72.68  72.652  72.622  72.615  72.642  72.643  72.667
   72.66  72.697  72.695  72.723   72.71  72.756   72.73  72.752  72.748  72.708
  72.681  72.701  72.699  72.727  72.708  72.742  72.706  72.707  72.676  72.718
  72.741  72.727  72.728  72.741  72.724  72.776  72.763  72.783  72.783  72.763
  72.762   72.78  72.778  72.744   72.77  72.738  72.754  72.784  72.759  72.817
                                                                                
                                                                                
                                                                                
                                                                                
                                                                                
                                                                                
                                                                                
                                                                                
                                                                                
                                                                                
       0   2.997  10.987  14.983   25.97  32.962  39.953  61.928  77.909  89.895
  91.893  99.884 105.877 109.872 114.866 117.863 121.858 125.853  128.85 130.847
 140.836 143.832 146.829 156.817 160.813 164.808 173.797 176.794 181.788 183.786
 192.775 194.773 200.766 202.764  214.75 223.739 247.711 253.704 261.695 266.689
 276.677 281.672 289.662 292.659 296.654 301.648 303.646 324.621  334.61 340.603
 354.587 358.582 362.577 365.574 382.554 391.543 398.535 400.533 407.525 414.517
 419.511 430.498 435.492  437.49 442.484 458.465  463.46 466.456 472.449 484.435
 500.416 508.407 519.394  531.38 532.379 539.371 552.356 560.347 570.335 587.315
 601.299 604.295  617.28 623.273  634.26  643.25 647.245 652.239 659.231 670.218
 682.204 685.201 692.193 698.186 700.183 704.179 716.165 724.156 730.149  737.14
  73.232  73.238   73.19  73.189  73.115  73.111   73.06  73.017  72.927  72.893
  72.862  72.825  72.824  72.762  72.778  72.723  72.745  72.723  72.744   72.71
  72.702  72.726   72.69  72.692  72.656  72.666  72.586  72.619  72.586  72.609
  72.593  72.564  72.597  72.577  72.602  72.583  72.622  72.607   72.63  72.623
  72.682  72.666  72.712  72.693  72.714  72.693  72.713  72.664  72.672  72.697
  72.688  72.696  72.661   72.68  72.652  72.622  72.615  72.642  72.643  72.667
   72.66  72.697  72.695  72.723   72.71  72.756   72.73  72.752  72.748  72.708
  72.681  72.701  72.699  72.727  72.708  72.742  72.706  72.707  72.676  72.718
  72.741  72.727  72.728  72.741  72.724  72.776  72.763  72.783  72.783  72.763
  72.762   72.78  72.778  72.744   72.77  72.738  72.754  72.784  72.759  72.817
                                                                                
                                                                                
                                                                                
                                                                                
                                                                                
                                                                                
                                                                                
                                                                                
                                                                                
                                                                                
BR Coef=-1 , 0 , 0 ,, 0 ,,,0.8,-1,,0,
WSPro=,,,, 1 ,,,, 0 ,,,, 0 ,,,,-1 ,-1 ,-1 , 0 , 0 , 0 , 0 , 0
Culvert=2,1.4,1.6,24.4,0.014,0.5,1,8,3,68.606,190,68.606,190,Culvert #1  , 0 ,100
Culvert Bottom n=0.04
Culvert Bottom Depth=1.4
BC Design=,, 0 ,, 0 ,,,,,,
BC HTab HWMax=76
BC Use User HTab Curves=0
BC User HTab FreeFlow(D)= 0

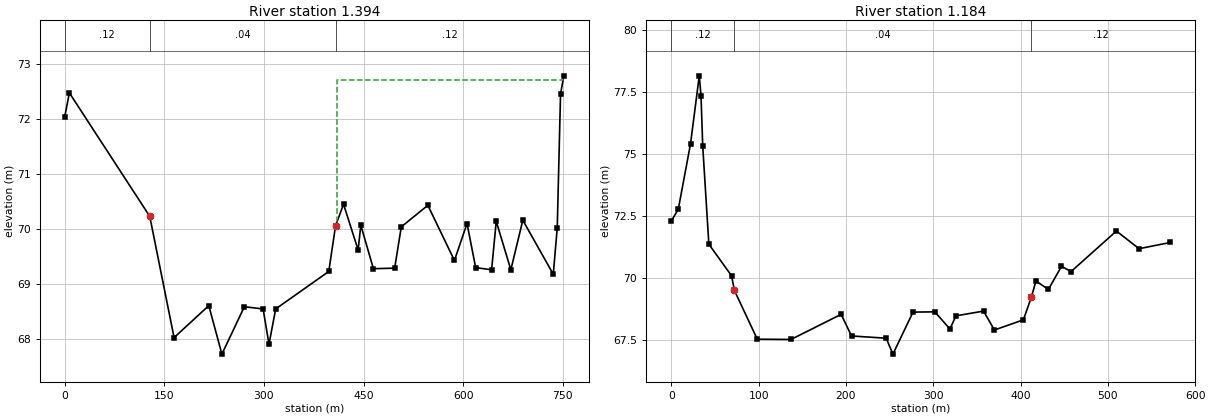
Type RM Length L Ch R = 1 ,1.394   ,102.55,210.08,310.23
BEGIN DESCRIPTION:
DS of TCH - NA02 (SEM 2019)
END DESCRIPTION:
XS GIS Cut Line= 4
  591741.2389036 5421731.2123831  591320.5505036 5421774.0749831
  591023.9861036 5421818.7055831  591017.0288036 5421846.7611831
#Sta/Elev= 30
       0   72.04       7   72.47  128.03   70.23  164.64   68.03  216.96   68.61
  236.66   67.73  270.52   68.59  298.78   68.55  307.56   67.91   317.7   68.55
  397.62   69.23  407.87   70.06  419.87   70.45  441.87   69.62  445.86   70.07
  464.86   69.28  496.86   69.29  506.86   70.04  546.86   70.43  586.86   69.43
  605.85    70.1  618.85    69.3  642.85   69.26  649.85   70.14  671.85   69.26
  689.85   70.16  735.73   69.18  741.71   70.02  746.69   72.45  751.68   72.78
#Mann= 3 , 0 , 0
       0     .12       0  128.03     .04       0  407.87     .12       0
#XS Ineff= 2 , 0
       0                  409.76       0    72.7
Permanent Ineff=
       F       T
Bank Sta=128.03,407.87
XS Rating Curve= 0 ,0
Exp/Cntr=0.3,0.1

Type RM Length L Ch R = 1 ,1.184   ,649.29,1184.04,868
BEGIN DESCRIPTION:
North Angle - NA01 (SEM 2019)
END DESCRIPTION:
XS GIS Cut Line= 3
591756.5847035985421728.56658309591389.3423035985421463.45348309
591295.4150035995421390.69298309
#Sta/Elev= 30
       0    72.3       8   72.78      22   75.41      32   78.14      34   77.34
   35.99    75.3   42.99   71.37   68.99    70.1   72.27   69.51   98.46   67.55
  137.12   67.54  194.52   68.55  206.43   67.68  246.11   67.59  253.82   66.95
  276.88   68.64  301.81   68.65  319.16   67.96  326.04   68.49  357.66   68.68
  370.12   67.92  403.31   68.33  412.44   69.24  417.67   69.89  431.94   69.55
  446.94   70.48  457.93   70.27  509.85    71.9  535.81   71.19  571.75   71.44
#Mann= 3 , 0 , 0
       0     .12       0   72.27     .04       0  412.44     .12       0
Bank Sta=72.27,412.44
XS Rating Curve= 0 ,0
Exp/Cntr=0.3,0.1

River Reach=Badger Brk      ,Badger Brk
Reach XY= 30
     570382.3974    5426714.7412     570363.7238    5426642.2364
     570363.2736    5426580.0099      570380.008    5426514.2004
     570424.7418    5426444.3103     570479.6389    5426373.2943
     570543.4582    5426300.4861     570641.2846      5426200.18
     570800.4117    5425976.8899     570824.7512     5425960.703
     570849.2496      5425932.45     570857.1987    5425859.5457
     570844.2978    5425826.3609     570823.2081    5425788.6188
     570807.2691    5425697.6227     570792.4086    5425668.2214
     570750.9888    5425631.4814     570721.3674    5425615.2237
     570707.6528     5425595.996     570690.9096    5425565.3002
     570683.2893     5425517.577     570710.7069    5425411.9142
     570721.8377    5425386.6647     570726.9116    5425338.4788
     570735.2763     5425325.121     570731.4901    5425258.8212
     570740.4263    5425239.2619     570760.1978     5425221.455
     570819.0139    5425142.8716      570864.899    5424936.1873

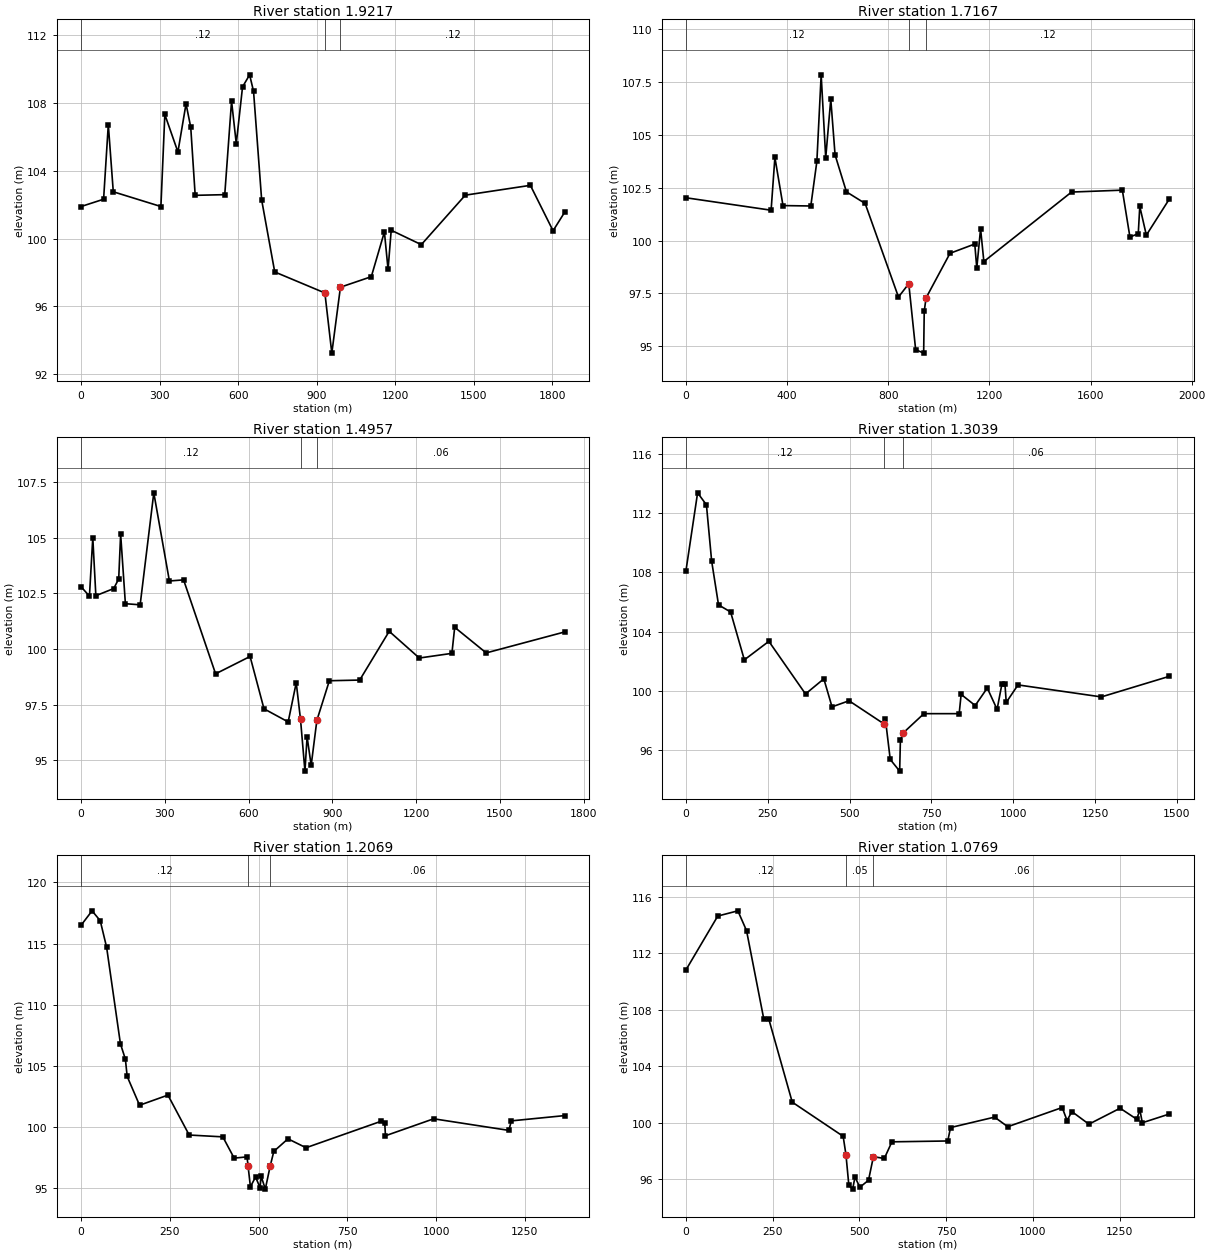
Type RM Length L Ch R = 1 ,1.9217  ,197.74,204.95,213.43
BEGIN DESCRIPTION:
BB06A (SEM 2019)
END DESCRIPTION:
XS GIS Cut Line= 6
  571308.9118036 5426706.1733831  570593.0028036 5426624.9547831
  570394.3130036 5426592.2669831  570328.3320036 5426574.0269831
  569709.8947036 5426418.0764831  569492.0791036 5426427.9283831
#Sta/Elev= 30
       0  101.89   85.94  102.32  103.93  106.72  122.92  102.76  304.79  101.89
  319.78  107.32  369.74  105.11  400.72  107.95  418.71  106.57   435.7  102.55
  548.62  102.59   574.6  108.11  592.59   105.6  616.57  108.95  643.56  109.66
  658.55  108.69  689.52  102.28  739.44   98.03  930.99   96.79957.4399   93.24
  990.36   97.13 1108.28   97.75 1158.27  100.39 1172.26   98.18 1184.26  100.49
 1299.22   99.64 1467.17  102.56 1715.73  103.14 1802.34  100.46 1846.15  101.54
#Mann= 3 , 0 , 0
       0     .12       0  930.99     .05       0  990.36     .12       0
Bank Sta=930.99,990.36
XS Rating Curve= 0 ,0
Exp/Cntr=0.3,0.1

Type RM Length L Ch R = 1 ,1.7167  ,220.41,220.98,223.48
BEGIN DESCRIPTION:
BB05 (SEM 2016)
END DESCRIPTION:
XS GIS Cut Line= 4
  571327.2238036 5426588.3872831  570732.3214036 5426555.8672831
  570332.7896036 5426337.2788831  569472.5343036 5426345.8957831
#Sta/Elev= 30
       0  102.03  336.88  101.44  351.88  103.94  383.87  101.66  493.83  101.64
  517.82  103.75  534.81  107.85  552.81  103.92   572.8   106.7  589.79  104.06
  634.74  102.31  708.65  101.76  840.48   97.33  881.21   97.96908.3811   94.84
 940.072  94.674  942.35   96.66  949.65   97.29 1044.22    99.4 1142.13   99.84
 1150.13    98.7 1165.12  100.56 1178.11   99.01 1524.82   102.3 1725.66  102.39
 1755.64  100.17 1788.61  100.33  1794.6  101.62 1820.58  100.26 1911.51  101.97
#Mann= 3 , 0 , 0
       0     .12       0  881.21     .05       0  949.65     .12       0
Bank Sta=881.21,949.65
XS Rating Curve= 0 ,0
Exp/Cntr=0.3,0.1

Type RM Length L Ch R = 1 ,1.4957  ,191.68,191.83,196.23
BEGIN DESCRIPTION:
BB05A (SEM 2019)
END DESCRIPTION:
XS GIS Cut Line= 6
  571384.6265036 5426449.3026831  571098.3751036 5426384.8446831
  570868.6799036 5426350.0741831  570639.1779036 5426261.4737831
  570324.3048036 5426104.8151831  569716.9908036 5426137.1507831
#Sta/Elev= 30
       0  102.79   29.94  102.37   41.92     105    52.9  102.39  116.77  102.71
  134.73  103.14  141.72  105.15  158.69  102.03  211.58  101.98  260.48  107.01
  316.35  103.05   367.2   103.1  481.86   98.88  605.41   99.66  655.21   97.31
  741.86   96.72  770.74   98.48   786.1   96.83  801.92   94.51  809.67   96.05
  824.29   94.77  844.64   96.79   889.4   98.57  998.08    98.6 1103.77  100.79
 1211.59   99.59 1328.44    99.8 1338.42  100.97 1451.27   99.82 1731.89  100.76
#Mann= 3 , 0 , 0
       0     .12       0   786.1     .05       0  844.64     .06       0
Bank Sta=786.1,844.64
XS Rating Curve= 0 ,0
Exp/Cntr=0.3,0.1

Type RM Length L Ch R = 1 ,1.3039  ,101.12,96.99,92.76
BEGIN DESCRIPTION:
BB04 (SEM 2016)
END DESCRIPTION:
XS GIS Cut Line= 6
  571312.8846036 5426266.6835831  571279.2574036 5426264.0965831
  571042.6509036 5426258.9089831  570732.5781036 5426096.7021831
  570584.6871036 5426004.0439831  569903.2756036 5426032.4634831
#Sta/Elev= 30
       0  108.09   35.72  113.37   62.69  112.56   78.66  108.76   99.63  105.81
  136.58  105.33  178.52   102.1  253.41  103.35  365.37    99.8  421.36  100.82
  446.36   98.93  498.35   99.34  604.39   97.79  609.33   98.12 624.219  95.381
652.9771  94.593  655.23   96.66   662.3   97.14  727.03   98.47  834.79   98.47
  840.78   99.77  883.72   99.02  920.66   100.2  950.62   98.76   965.6   100.5
  974.59  100.48  978.58   99.23 1014.53  100.41 1269.15    99.6 1476.84  100.99
#Mann= 3 , 0 , 0
       0     .12       0  604.39     .05       0   662.3     .06       0
Bank Sta=604.39,662.3
XS Rating Curve= 0 ,0
Exp/Cntr=0.3,0.1

Type RM Length L Ch R = 1 ,1.2069  ,150.42,129.99,115.78
BEGIN DESCRIPTION:
BB04A (SEM 2019)
END DESCRIPTION:
XS GIS Cut Line= 4
  571258.0140036 5426125.9812831  570944.7676036 5426088.3940831
  570653.7215036 5425952.7864831  569929.9179036 5425997.2709831
#Sta/Elev= 30
       0   116.5   30.95  117.68   53.91  116.87   71.88   114.7  110.82  106.79
   124.8  105.53  129.79  104.12  164.74  101.76  244.61  102.59  304.51   99.32
  399.25   99.17  431.16   97.43467.4399   97.53  470.37   96.77476.9399   95.09
  491.54   95.88503.9301   95.02507.4301   95.93  518.87   94.89  532.75   96.79
  542.85   97.98  582.73   99.01  633.59   98.28  845.34  100.45  855.33  100.32
  857.33   99.26  993.18  100.65 1204.94    99.7 1211.93  100.48 1361.76  100.91
#Mann= 3 , 0 , 0
       0     .12       0  470.37     .05       0  532.75     .06       0
Bank Sta=470.37,532.75
XS Rating Curve= 0 ,0
Exp/Cntr=0.3,0.1

Type RM Length L Ch R = 1 ,1.0769  ,121.67,104.07,95.79
BEGIN DESCRIPTION:
BB04B (SEM 2019)
END DESCRIPTION:
XS GIS Cut Line= 4
  571354.7469036 5425969.5420831  570892.8970036 5425912.7989831
  570832.4320036 5425908.6779831  569965.5408036 5425946.0643831
#Sta/Elev= 30
       0  110.83   91.87  114.65  149.78  115.02  174.75  113.62  224.67  107.34
  238.65  107.38  306.55  101.47  453.34   99.05  461.37   97.75  469.77   95.57
480.6899   95.31  487.49   96.17  501.39   95.44  526.41   95.94  540.53   97.61
  571.91   97.48   593.9   98.66  754.85   98.72  762.85   99.67   889.8  100.41
  927.79   99.73 1084.74  101.09 1098.73  100.17 1112.73   100.8 1161.71   99.91
 1251.68  101.04 1299.66  100.26 1308.66  100.93 1315.66  100.01 1393.63  100.63
#Mann= 3 , 0 , 0
       0     .12       0  461.37     .05       0  540.53     .06       0
Bank Sta=461.37,540.53
XS Rating Curve= 0 ,0
Exp/Cntr=0.3,0.1

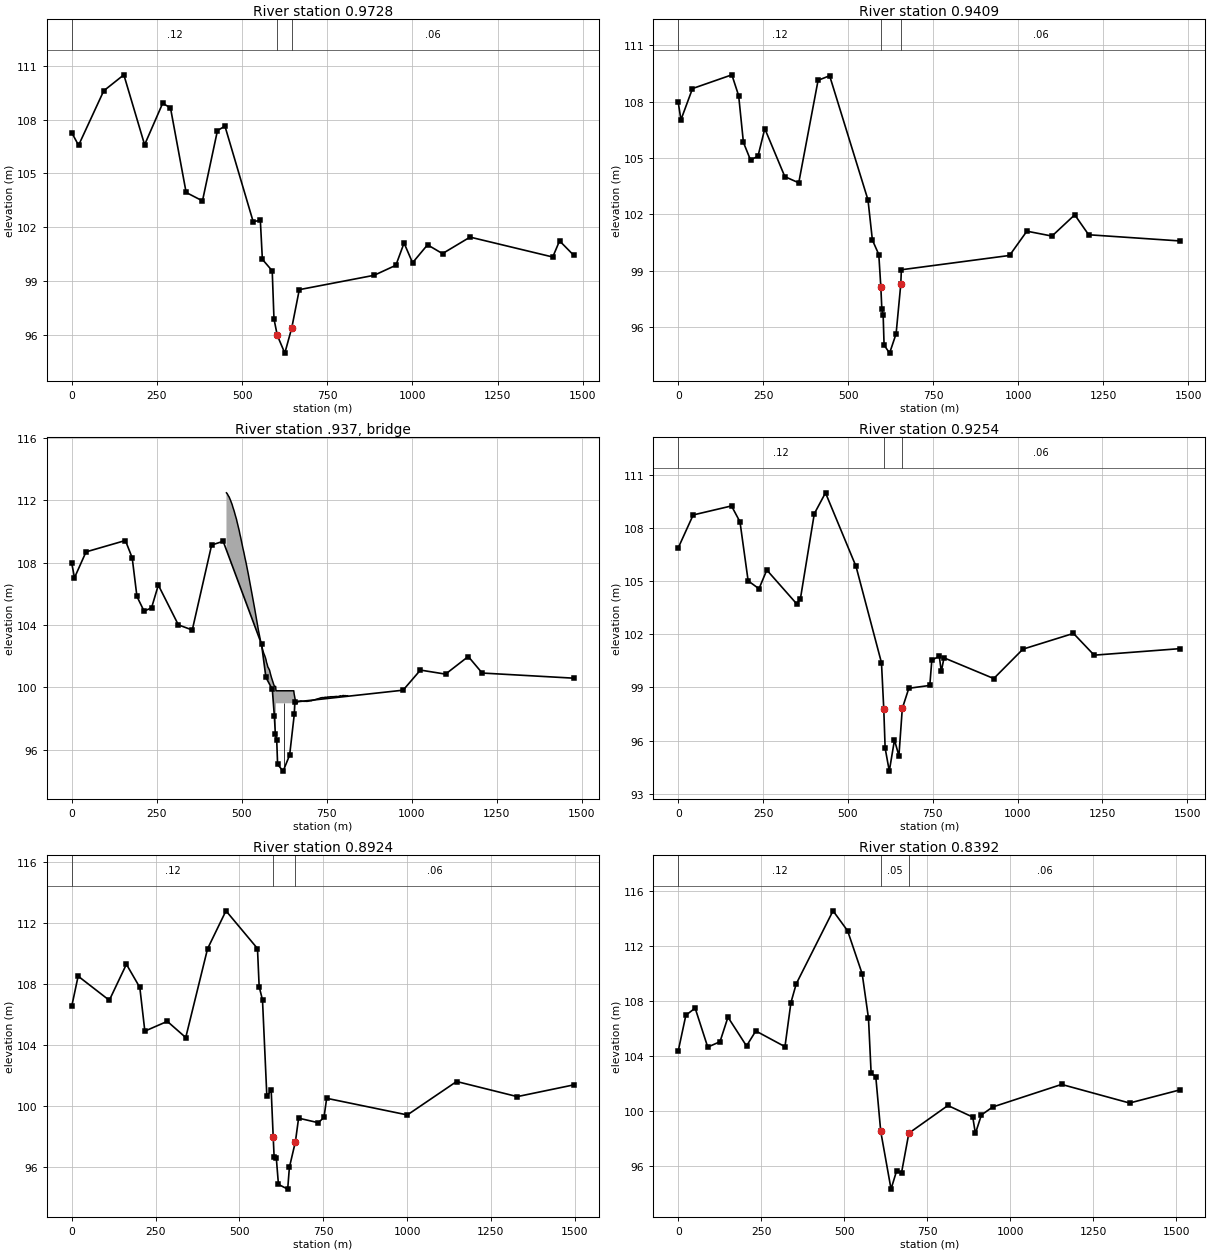
Type RM Length L Ch R = 1 ,0.9728  ,31.05,31.96,33.49
BEGIN DESCRIPTION:
BB04C (SEM 2019)
END DESCRIPTION:
XS GIS Cut Line= 4
  571444.9355036 5425880.3426831  570894.6006036 5425797.1113831
  570745.4148036 5425831.9637831  569983.8026036 5425895.4246831
#Sta/Elev= 30
       0  107.27   19.99  106.57   93.93  109.61  152.89   110.5  213.84   106.6
  266.81  108.91  289.79  108.66  335.75  103.94  383.72  103.47  427.69  107.39
  449.67  107.64  532.61  102.31   553.6  102.39  559.58  100.21  588.49   99.57
  593.66   96.89  603.35   95.97  625.49   94.98  645.88   96.39  668.01   98.52
  887.62   99.32  951.56   99.88  975.53  101.12 1000.51  100.02 1044.46  101.02
 1088.42  100.53 1169.34  101.45 1412.09  100.34 1432.07  101.24 1474.03  100.43
#Mann= 3 , 0 , 0
       0     .12       0  603.35     .05       0  645.88     .06       0
Bank Sta=603.35,645.88
XS Rating Curve= 0 ,0
Exp/Cntr=0.3,0.1

Type RM Length L Ch R = 1 ,0.9409  ,14.05,15.45,18.19
BEGIN DESCRIPTION:
US of Badger Brook Footbridge - BB03 (SEM 2016)
END DESCRIPTION:
XS GIS Cut Line= 5
  571436.8805036 5425847.1186831  570876.5547036 5425772.9754831
  570779.8029036 5425789.5026831  570588.0976036 5425822.2227831
  569970.7594036 5425869.6644831
#Sta/Elev= 30
       0  107.96    7.99  107.03   41.94  108.69  157.78  109.42  177.75  108.31
  191.73  105.83   212.7  104.89  234.67   105.1  254.64  106.56  313.56  104.01
   354.5  103.68  411.42  109.13  445.38  109.37  558.22  102.77  571.16  100.64
     590   99.87  595.95   98.16  598.92   96.99  602.89   96.63605.5291  95.058
621.7991  94.629640.9189  95.659  654.64   98.28  656.42   99.06  974.68   99.82
 1025.62  101.11 1099.52  100.85 1166.43  101.98 1207.37  100.92 1477.01  100.59
#Mann= 3 , 0 , 0
       0     .12       0  595.95     .05       0  654.64     .06       0
Bank Sta=595.95,654.64
XS Rating Curve= 0 ,0
Exp/Cntr=0.3,0.1

Type RM Length L Ch R = 3 ,.937    ,,,
Node Photo=.\FFSModel_Pictures\BB_0_937.JPG
BEGIN DESCRIPTION:
Badger Brook Footbridge
END DESCRIPTION:
Bridge Culvert--1,0,-1,-1, 0
Deck Dist Width WeirC Skew NumUp NumDn MinLoCord MaxHiCord MaxSubmerge Is_Ogee
10,1.3,1.4,0, 100, 100, , , 0.98, 0, 3,3,,
     455456.9817 460.945462.9267  466.89471.8442473.8259477.7892480.7617484.7251
485.7159492.6517494.6334496.6151503.5509506.5234509.4959512.4684519.4043530.2311
538.1052548.9321555.8218557.8205 561.818 564.816567.8141569.8128571.8115572.8108
574.8095576.8082578.8069 581.805 584.803587.8011594.7966596.7834 599.746600.7335
 601.721602.7086603.6961604.6836605.6711610.6087615.5463624.4341628.3841629.3717
631.3467632.3342636.2843638.2594642.2094644.1845647.1471649.1221650.1096651.0972
652.0847653.0722654.0597658.0098660.9724662.9474664.9225669.8601673.8294678.8151
683.8008686.7923688.7865693.7723701.7494704.7408706.7351709.7266723.6866727.6751
732.6609738.6437 740.638745.6237748.6151750.6094751.6066753.6009755.5952760.5809
770.5523778.5294783.5151790.4951793.4866798.4723800.4666 805.427808.3426811.2582
 112.478 112.432 112.274 112.212 112.005 111.721 111.567 111.304 111.064 110.769
 110.666 110.047 109.825 109.646 108.915 108.635 108.311 108.021 107.259 105.985
 105.046 103.685 102.934 102.744  102.39 102.182 102.023 101.896 101.742  101.61
 101.486 101.309 101.238 101.103  100.84 100.609 100.141 100.065 100.061  99.782
  99.782  99.782  99.782  99.782  99.782  99.782  99.782  99.782  99.782  99.782
  99.782  99.782  99.782  99.782  99.782  99.782  99.782  99.782  99.782  99.782
  99.782  99.782  99.596  99.137  98.971  98.977  99.113  99.111  99.135  99.112
  99.102  99.113  99.101  99.106   99.14  99.136  99.163  99.169  99.267  99.289
  99.332  99.348  99.338  99.368  99.362  99.327  99.371  99.393  99.378    99.4
  99.403  99.421   99.41  99.463  99.441  99.482  99.467   99.47  99.457  99.464
                                                                                
                                                                                
                                                                                
                                                                          98.982
  98.982  98.982  98.982  98.982  98.982  98.982  98.982  98.982  98.982  98.982
  98.982  98.982  98.982  98.982  98.982  98.982  98.982  98.982  98.982  98.982
  98.982  98.982
                                                                                
                                                                                
                                                                                
     460461.9817 465.945467.9267  471.89476.8442478.8259482.7892485.7617489.7251
490.7159497.6517499.6334501.6151508.5509511.5234514.4959517.4684524.4043535.2311
543.1052553.9321560.8218562.8205 566.818 569.816572.8141574.8128576.8115577.8108
579.8095581.8082583.8069 586.805 589.803592.8011599.7966601.7834 604.746605.7335
 606.721607.7086608.6961609.6836610.6711615.6087620.5463629.4341633.3841634.3717
636.3467637.3342641.2843643.2594647.2094649.1845652.1471654.1221655.1096656.0972
657.0847658.0722659.0597663.0098665.9724667.9474669.9225674.8601678.8294683.8151
688.8008691.7923693.7865698.7723706.7494709.7408711.7351714.7266728.6866732.6751
737.6609743.6437 745.638750.6237753.6151755.6094756.6066758.6009760.5952765.5809
775.5523783.5294788.5151795.4951798.4866803.4723805.4666 810.427813.3426816.2582
 112.478 112.432 112.274 112.212 112.005 111.721 111.567 111.304 111.064 110.769
 110.666 110.047 109.825 109.646 108.915 108.635 108.311 108.021 107.259 105.985
 105.046 103.685 102.934 102.744  102.39 102.182 102.023 101.896 101.742  101.61
 101.486 101.309 101.238 101.103  100.84 100.609 100.141 100.065 100.061  99.782
  99.782  99.782  99.782  99.782  99.782  99.782  99.782  99.782  99.782  99.782
  99.782  99.782  99.782  99.782  99.782  99.782  99.782  99.782  99.782  99.782
  99.782  99.782  99.596  99.137  98.971  98.977  99.113  99.111  99.135  99.112
  99.102  99.113  99.101  99.106   99.14  99.136  99.163  99.169  99.267  99.289
  99.332  99.348  99.338  99.368  99.362  99.327  99.371  99.393  99.378    99.4
  99.403  99.421   99.41  99.463  99.441  99.482  99.467   99.47  99.457  99.464
                                                                                
                                                                                
                                                                                
                                                                          98.982
  98.982  98.982  98.982  98.982  98.982  98.982  98.982  98.982  98.982  98.982
  98.982  98.982  98.982  98.982  98.982  98.982  98.982  98.982  98.982  98.982
  98.982  98.982
                                                                                
                                                                                
                                                                                
Pier Skew, UpSta & Num, DnSta & Num=  ,624.25, 2 ,631.25, 2 , 0 , 0 , 0 ,,
     2.2     2.2
       0     100
     2.2     2.2
       0     100
BR Coef=-1 , 0 , 0 ,, 0 ,,,0.8,-1,,0,
WSPro=,,,, 1 ,,,, 0 ,,,, 0 ,,,,-1 ,-1 ,-1 , 0 , 0 , 0 , 0 , 0
BC Design=,, 0 ,, 0 ,,,,,,
BC HTab HWMax=106
BC Use User HTab Curves=0
BC User HTab FreeFlow(D)= 0

Type RM Length L Ch R = 1 ,0.9254  ,35.97,33.06,29
BEGIN DESCRIPTION:
02YO019 Badger Brook Below Footbridge - BB03A (SEM 2019)
END DESCRIPTION:
XS GIS Cut Line= 5
  571439.6576036 5425835.4555831  570845.8720036 5425764.7429831
  570766.6315036 5425772.0116831  570543.1302036 5425807.5026831
  569969.1254036 5425852.6449831
#Sta/Elev= 30
       0  106.88      44  108.74  156.99  109.25  181.99  108.35  205.99  105.02
  237.99  104.57  260.99  105.63  348.99  103.72  359.99     104  400.99  108.81
  433.99  109.99  523.98  105.83  598.97  100.39  605.72   97.77  609.76   95.57
  621.99   94.27  637.26   96.03  650.35   95.13   660.3   97.81  679.55   98.95
  741.36   99.11  747.34  100.54  769.27  100.76  775.25    99.9  783.23  100.67
  929.85    99.5 1015.81  101.16 1164.76  102.05 1225.73  100.82 1479.63  101.19
#Mann= 3 , 0 , 0
       0     .12       0  605.72     .05       0   660.3     .06       0
Bank Sta=605.72,660.3
XS Rating Curve= 0 ,0
Exp/Cntr=0.3,0.1

Type RM Length L Ch R = 1 ,0.8924  ,58.47,53.16,43.45
BEGIN DESCRIPTION:
BB03B (SEM 2019)
END DESCRIPTION:
XS GIS Cut Line= 4
  571442.6350036 5425784.8015831  570886.6962036 5425718.2957831
  570636.6574036 5425773.9431831  569957.7985036 5425833.2438831
#Sta/Elev= 30
       0  106.56      19  108.52  111.98  106.94  162.97   109.3  202.96  107.78
  217.96  104.92  284.95  105.56  339.94   104.5  404.93  110.31  459.92   112.8
   553.9  110.33   558.9  107.84  568.87  106.96  581.83  100.66  594.79  101.04
  600.85   97.96  603.47    96.7   610.1    96.6  616.42   94.88  643.99   94.57
  649.13      96  667.04   97.68  676.52   99.22  735.33   98.92  752.27   99.27
  760.24  100.52 1000.91   99.43 1147.79  101.62 1328.63  100.63 1497.49   101.4
#Mann= 3 , 0 , 0
       0     .12       0  600.85     .05       0  667.04     .06       0
Bank Sta=600.85,667.04
XS Rating Curve= 0 ,0
Exp/Cntr=0.3,0.1

Type RM Length L Ch R = 1 ,0.8392  ,31,26.62,20.23
BEGIN DESCRIPTION:
BB03C (SEM 2019)
END DESCRIPTION:
XS GIS Cut Line= 4
  571436.1329036 5425719.4961831  570876.0476036 5425643.0251831
  570656.8206036 5425761.5106831  569960.8786036 5425819.0884831
#Sta/Elev= 30
       0  104.37   22.97  106.96   50.94  107.48   88.89  104.65  125.84  105.04
  149.81  106.82  205.74  104.73   233.7  105.82  321.59  104.68  339.57  107.88
  355.55  109.24  466.41  114.54  510.35  113.09   554.3  109.96  573.26  106.74
  581.23  102.74  595.19  102.51  610.14   98.53  641.23   94.34  658.29   95.69
  672.75   95.52  694.87    98.4  812.49  100.41  887.41   99.57   895.4   98.38
  913.39   99.72  947.35   100.3 1155.16  101.94 1359.96  100.59 1512.82  101.55
#Mann= 3 , 0 , 0
       0     .12       0  610.14     .05       0  694.87     .06       0
Bank Sta=610.14,694.87
XS Rating Curve= 0 ,0
Exp/Cntr=0.3,0.1

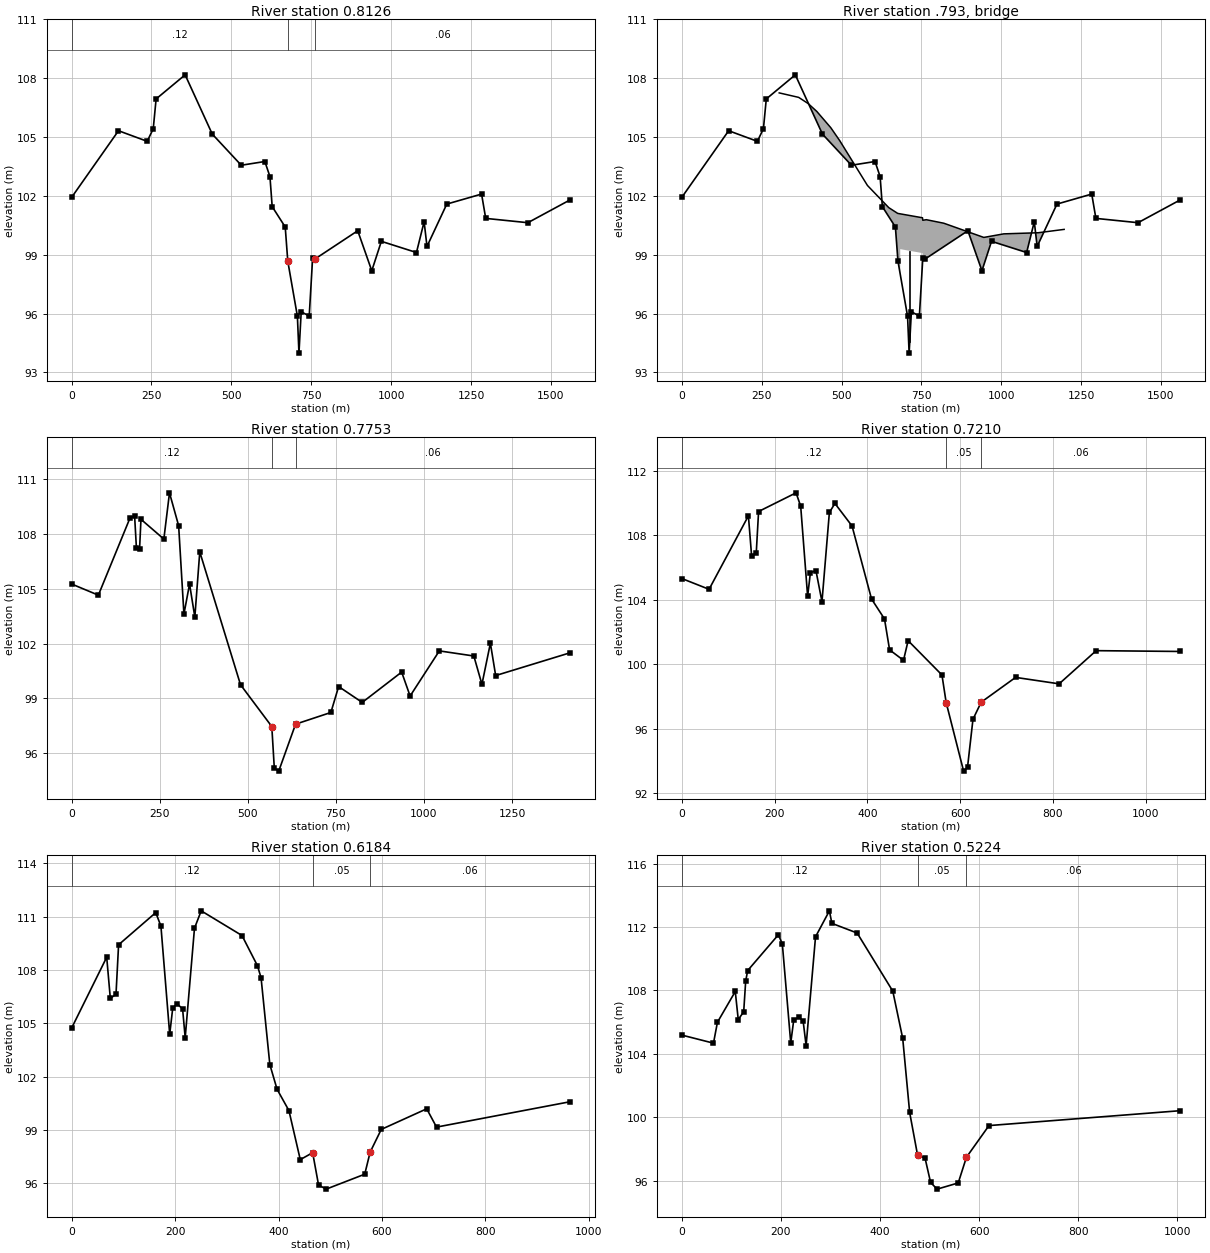
Type RM Length L Ch R = 1 ,0.8126  ,38.46,37.26,37.32
BEGIN DESCRIPTION:
US of Badger Brook TCH Bridge - BB03D (SEM 2019)
END DESCRIPTION:
XS GIS Cut Line= 6
  571453.8272036 5425609.9846831  570965.4253036 5425528.7775831
  570860.9780036 5425602.2767831  570758.8660036 5425683.5759831
  570658.4694036 5425749.7428831  569973.5592036 5425807.8825831
#Sta/Elev= 30
       0  101.92  146.74  105.32  236.57  104.78  255.54  105.42  264.52  106.94
  355.36  108.17   440.2  105.15  531.03  103.56  604.86  103.75  620.83  102.98
  627.81  101.45  668.66  100.41  676.63   98.67  706.73   95.86  711.62   93.98
  718.65   96.09  743.73   95.87  754.34   98.82  760.87   98.77  895.57  100.22
  939.53   98.18   969.5   99.68  1079.4   99.11 1103.37  100.68 1112.37   99.42
 1174.31  101.58  1283.2  102.09 1296.19  100.85 1428.06  100.63 1560.94   101.8
#Mann= 3 , 0 , 0
       0     .12       0  676.63     .05       0  760.87     .06       0
Bank Sta=676.63,760.87
XS Rating Curve= 0 ,0
Exp/Cntr=0.3,0.1

Type RM Length L Ch R = 3 ,.793    ,,,
Node Photo=.\FFSModel_Pictures\BB_0_793.JPG
BEGIN DESCRIPTION:
Badger Brook TCH Bridge
END DESCRIPTION:
Bridge Culvert--1,0,-1,-1, 0
Deck Dist Width WeirC Skew NumUp NumDn MinLoCord MaxHiCord MaxSubmerge Is_Ogee
13,8.9,1.4,0, 18, 18, , , 0.98, 0, 3,3,,
     305365.8315395.7486 422.674466.5524 494.475 581.188647.9228 675.812683.7803
753.4294754.4244765.3693820.0897945.33511007.7971115.5571196.792
107.2485107.0204106.7035106.3027105.4716104.8118102.5279101.3977101.1052 101.082
 100.882100.7539100.7837100.6041 99.8794100.0615100.1181100.2892
                                                                          99.282
  99.082
     185245.8315275.7486 302.674346.5524 374.475 461.188527.9228 555.812563.7803
633.4294634.4244645.3693700.0897825.3351 887.797995.55751076.792
107.2485107.0204106.7035106.3027105.4716104.8118102.5279101.3977101.1052 101.082
 100.882100.7539100.7837100.6041 99.8794100.0615100.1181100.2892
                                                                          99.282
  99.082
Pier Skew, UpSta & Num, DnSta & Num=  ,713.45, 3 ,594.45, 3 , 3 , 3 , 0 ,,
    1.38    1.38    2.59
       0    95.4   101.1
    1.38    1.38    2.59
       0    95.4   101.1
BR Coef=-1 , 0 , 0 ,, 0 ,,,0.8,-1,,0,
WSPro=,,,, 1 ,,,, 0 ,,,, 0 ,,,,-1 ,-1 ,-1 , 0 , 0 , 0 , 0 , 0
BC Design=,, 0 ,, 0 ,,,,,,
BC HTab HWMax=107
BC Use User HTab Curves=0
BC User HTab FreeFlow(D)= 0

Type RM Length L Ch R = 1 ,0.7753  ,49.06,54.37,66.47
BEGIN DESCRIPTION:
DS of Badger Brook TCH Bridge - BB02 (SEM 2016)
END DESCRIPTION:
XS GIS Cut Line= 5
  571291.7718036 5425553.7127831  570930.0307036 5425493.2930831
  570857.8325036 5425557.5163831  570648.9210036 5425724.5733831
  569967.0463036 5425784.4468831
#Sta/Elev= 30
       0  105.26   75.95  104.65  165.89  108.88  178.88  108.97  183.88  107.25
  192.87  107.17  196.87   108.8  261.82  107.72  277.81  110.25  303.79  108.45
  318.78  103.61  334.77  105.26  349.76  103.45  363.75  107.02  479.35   99.75
  568.18   97.46  575.25  95.196 587.834   95.02  635.66   97.59  735.87   98.23
  757.85   99.65   824.8   98.78  936.72  100.44   960.7   99.13 1043.64   101.6
 1141.57  101.32 1164.56   99.77 1188.54  102.02 1203.53  100.25 1415.38   101.5
#Mann= 3 , 0 , 0
       0     .12       0  568.18     .05       0  635.66     .06       0
Bank Sta=568.18,635.66
XS Rating Curve= 0 ,0
Exp/Cntr=0.3,0.1

Type RM Length L Ch R = 1 ,0.7210  ,97.07,102.56,116.89
BEGIN DESCRIPTION:
BB02A (SEM 2019)
END DESCRIPTION:
XS GIS Cut Line= 5
  571267.0254036 5425527.1883831  570914.4535036 5425470.8661831
  570736.9240036 5425595.2409831  570631.5749036 5425645.6255831
  570249.0164036 5425682.7771831
#Sta/Elev= 30
       0  105.32   58.84  104.65  143.61  109.21   150.6   106.7  160.57  106.92
  165.56  109.48  246.34  110.64  256.31  109.81  271.27  104.22  277.26  105.68
  289.22  105.81  302.19  103.88  318.15  109.42  330.11  109.98  367.03  108.58
  408.99  104.05  436.95  102.81  447.94  100.89  477.91  100.24   487.9  101.46
  560.82   99.33  569.86   97.62  607.48   93.36  615.96   93.61  627.67   96.58
  645.36   97.64  719.53   99.18  813.38   98.78  893.24  100.84 1074.94  100.79
#Mann= 3 , 0 , 0
       0     .12       0  569.86     .05       0  645.36     .06       0
Bank Sta=569.86,645.36
XS Rating Curve= 0 ,0
Exp/Cntr=0.3,0.1

Type RM Length L Ch R = 1 ,0.6184  ,83.08,96.04,122.15
BEGIN DESCRIPTION:
BB02B (SEM 2019)
END DESCRIPTION:
XS GIS Cut Line= 5
  571196.4541036 5425504.7467831  570871.7068036 5425456.0267831
  570735.1320036 5425503.4669831  570642.3830036 5425516.7479831
  570268.6150036 5425651.7830831
#Sta/Elev= 30
       0  104.73   67.87  108.72   74.86   106.4   85.84  106.64   90.83  109.42
  162.69  111.23  172.67  110.47  189.64  104.38  195.63  105.89  204.61  106.09
   214.6   105.8  219.59  104.19  237.55  110.35  250.53  111.33  329.38  109.94
  359.29  108.24  366.27  107.56  383.22  102.68  397.18  101.29  420.11  100.09
  442.05   97.33  465.98   97.72  477.39    95.9  492.16   95.67  566.66   96.51
  577.12   97.75  598.61   99.03  686.48  100.19  705.45   99.16  964.07  100.59
#Mann= 3 , 0 , 0
       0     .12       0  465.98     .05       0  577.12     .06       0
Bank Sta=465.98,577.12
XS Rating Curve= 0 ,0
Exp/Cntr=0.3,0.1

Type RM Length L Ch R = 1 ,0.5224  ,89.47,78.16,55.47
BEGIN DESCRIPTION:
BB02C (SEM 2019)
END DESCRIPTION:
XS GIS Cut Line= 5
  571237.5709036 5425502.1812831  570752.7620036 5425426.1249831
  570638.7351036 5425404.1022831  570493.1912036 5425515.4818831
  570303.4755036 5425618.8007831
#Sta/Elev= 30
       0  105.18   63.97  104.67   71.96  105.99  107.94  107.93  113.94  106.16
  124.93  106.65  128.93  108.58  132.93  109.25   194.9  111.51  202.89  110.93
  219.88  104.68  225.88  106.13  236.87  106.32  244.87  106.06  250.87  104.52
  269.86  111.38  297.84  113.02  302.84  112.23  353.81  111.62  425.77  107.95
  445.76  104.97  459.76   100.3  475.75    97.6  490.74   97.43  502.01   95.88
  515.22   95.46  557.75   95.85   574.3   97.47  619.82   99.47 1006.17  100.41
#Mann= 3 , 0 , 0
       0     .12       0  475.75     .05       0   574.3     .06       0
Bank Sta=475.75,574.3
XS Rating Curve= 0 ,0
Exp/Cntr=0.3,0.1

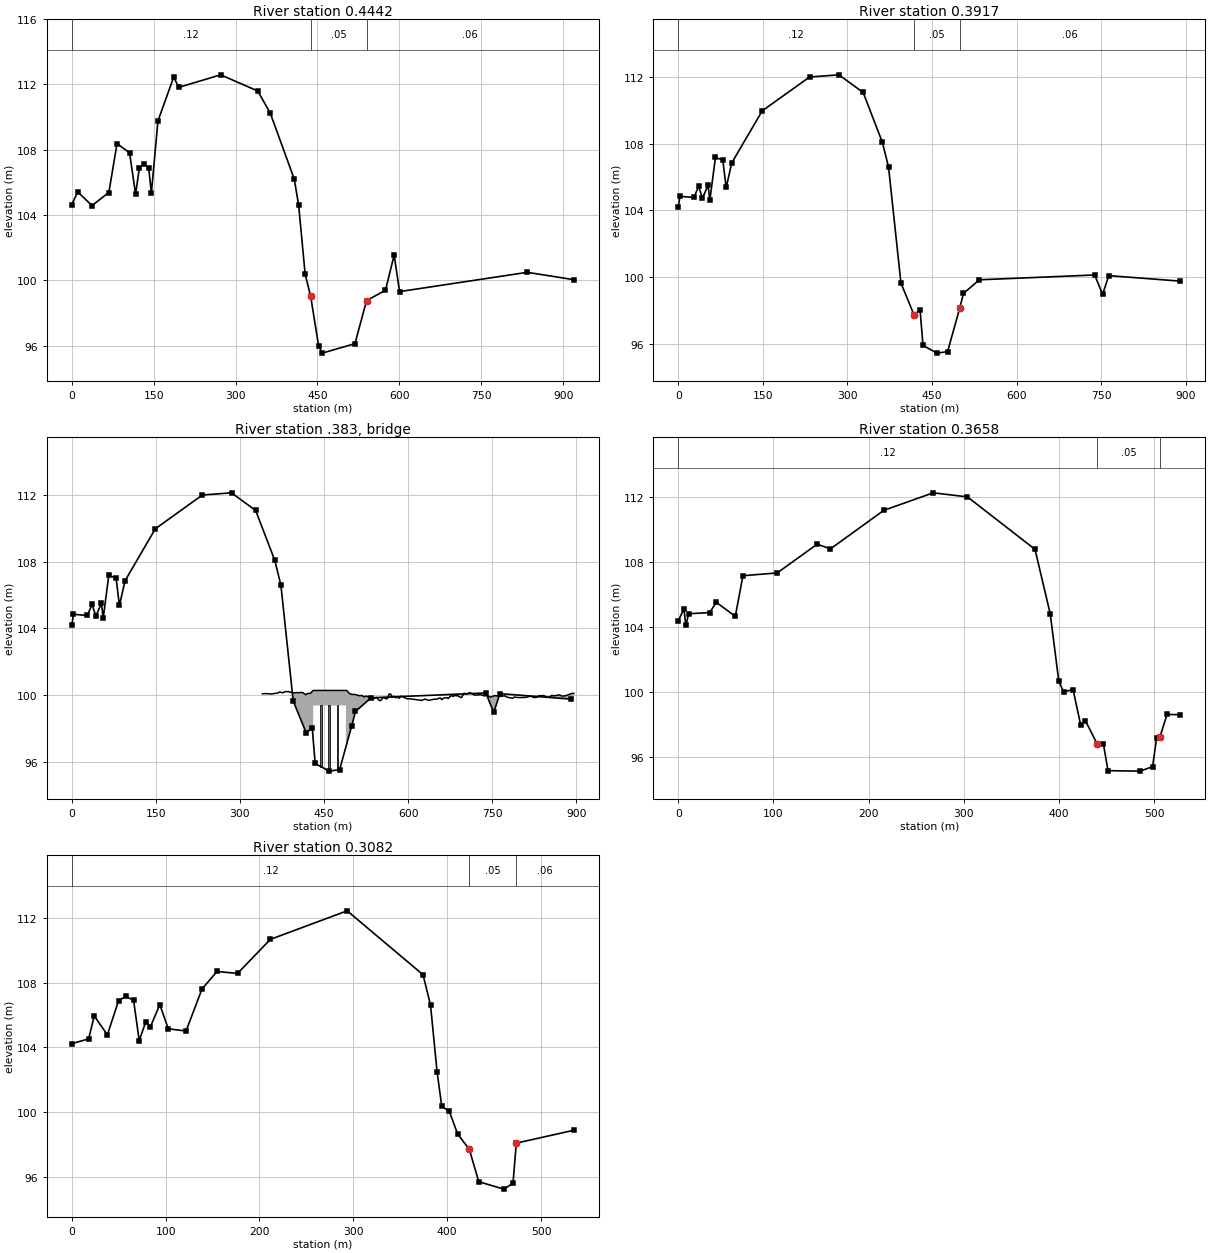
Type RM Length L Ch R = 1 ,0.4442  ,48.45,52.49,52.53
BEGIN DESCRIPTION:
Sunset Dr - BB02D (SEM 2019)
END DESCRIPTION:
XS GIS Cut Line= 6
  571185.3666036 5425462.8027831  570761.3830036 5425332.9131831
  570675.9460036 5425355.9979831  570603.2346036 5425365.3165831
  570427.5679036 5425516.7339831  570361.5645036 5425565.8887831
#Sta/Elev= 30
       0  104.64   10.99  105.42   36.95  104.58   67.91  105.38   82.89  108.38
  105.86  107.81  116.85  105.28  123.84   106.9  132.83   107.1  140.82   106.9
  145.81  105.35   157.8  109.76  186.76  112.46  195.75  111.82  272.65  112.59
  340.56   111.6  363.53  110.24  407.48   106.2  415.47  104.61  427.45  100.36
  437.44   99.03  451.94      96  458.51   95.54  518.61   96.12  539.86   98.76
  574.53   99.39  590.38  101.55  600.29   99.31  834.16  100.49  919.46  100.04
#Mann= 3 , 0 , 0
       0     .12       0  437.44     .05       0  539.86     .06       0
Bank Sta=437.44,539.86
XS Rating Curve= 0 ,0
Exp/Cntr=0.3,0.1

Type RM Length L Ch R = 1 ,0.3917  ,39.49,25.87,32.12
BEGIN DESCRIPTION:
US of Badger Brook T'Railway Bridge - BB02E (SEM 2019)
END DESCRIPTION:
XS GIS Cut Line= 4
  571155.5483036 5425428.1316831  570791.1355036 5425275.7784831
  570682.7561036 5425307.5697831  570325.1607036 5425443.5344831
#Sta/Elev= 30
       0  104.18       3  104.85      28  104.78      36  105.45      43  104.74
      53  105.52      56   104.6      66  107.18      79  107.03      85  105.38
   94.99  106.86  148.99  109.98  232.99  112.01  284.98  112.14  327.98  111.08
  361.98   108.1  372.98  106.61  394.98   99.65  417.97   97.75  428.96   98.02
  434.12    95.9   459.1   95.44  477.75   95.53  499.06   98.12  505.93   99.02
   533.9   99.84  738.67  100.13  752.65   98.96  763.64  100.09   890.5   99.76
#Mann= 3 , 0 , 0
       0     .12       0  417.97     .05       0  499.06     .06       0
Bank Sta=417.97,499.06
XS Rating Curve= 0 ,0
Exp/Cntr=0.3,0.1

Type RM Length L Ch R = 3 ,.383    ,,,
Node Photo=.\FFSModel_Pictures\BB_0_383.JPG
BEGIN DESCRIPTION:
Badger Brook T'Railway Bridge
END DESCRIPTION:
Bridge Culvert--1,0,-1,-1, 0
Deck Dist Width WeirC Skew NumUp NumDn MinLoCord MaxHiCord MaxSubmerge Is_Ogee
17,3.3,1.4,0, 97, 97, , , 0.98, 0, 3,3,,
     340347.8069355.6139368.4265370.4012376.2238380.9067386.5263393.9559411.4159
417.2854420.2202425.9996430.6752433.4243 435.257440.2317460.1305465.1052472.0697
474.0596479.0343482.0191 484.009485.9989487.9887488.9837490.9735494.9587499.9471
503.9377512.9167 517.905 520.898525.8863536.7898543.6909547.6344 550.592555.5214
561.4366 563.368566.2651569.1623571.0937573.9908577.9013580.8461583.7909587.7173
597.5333603.4229624.0365629.9109636.7554646.5334649.4667657.2891660.2224 662.178
669.0834671.0694677.0274680.0064682.9854688.9434694.9014699.8664704.8315709.7964
718.7335729.6565734.6215740.5795747.5305754.4815764.4115772.3555777.3205786.2575
789.2365798.1787810.1015818.0501825.0051830.9665832.9536841.8958847.8572853.8186
855.8057  859.78869.7158874.6836 880.645892.5679895.5486
 100.079 100.093 100.065 100.135 100.194 100.138 100.214 100.207 100.141 100.159
 100.027 100.094 100.113 100.281 100.281 100.281 100.281 100.281 100.281 100.281
 100.281 100.281 100.281 100.281 100.281 100.281 100.281  100.27 100.101 100.037
 100.048  99.965   99.98  99.902  99.941  99.757  99.862  99.706  99.662  99.864
  99.767  99.819 100.076 100.052  99.861  99.944  99.841  99.915   99.81  99.941
  99.787  99.779  99.685  99.763  99.685  99.758  99.746  99.834  99.721  99.806
  99.851  99.797  99.978  99.922  99.982  99.953  99.845 100.113 100.065 100.155
  99.998 100.032  99.961  99.966  99.884  99.974  99.926  99.959  99.871  99.809
  99.886  99.852  99.867  99.941  99.851  99.888  99.963  99.974  99.869  99.914
  99.988  99.958 100.016  99.941  99.963 100.107 100.104
                                                                                
                          99.381  99.381  99.381  99.381  99.381  99.381  99.381
  99.381  99.381  99.381  99.381  99.381  99.381  99.381
                                                                                
                                                                                
                                                                                
                                                                                
                                                                                
                                                                                
                                                        
     354 361.807 369.614 382.427 384.401 390.224 394.907 400.526 407.956 425.416
 431.285  434.22     440 444.675 447.424 449.257 454.232 474.131 479.105  486.07
  488.06 493.034 496.019 498.009 499.999 501.989 502.984 504.974 508.959 513.947
 517.938 526.917 531.905 534.898 539.886  550.79 557.691 561.634 564.592 569.521
 575.437 577.368 580.265 583.162 585.094 587.991 591.901 594.846 597.791 601.717
 611.533 617.423 638.037 643.911 650.755 660.533 663.467 671.289 674.222 676.178
 683.083 685.069 691.027 694.006 696.985 702.943 708.901 713.866 718.832 723.796
 732.734 743.657 748.622  754.58 761.531 768.482 778.412 786.356 791.321 800.258
 803.237 812.179 824.102  832.05 839.005 844.967 846.954 855.896 861.857 867.819
 869.806  873.78 883.716 888.684 894.645 906.568 909.549
 100.079 100.093 100.065 100.135 100.194 100.138 100.214 100.207 100.141 100.159
 100.027 100.094 100.113 100.281 100.281 100.281 100.281 100.281 100.281 100.281
 100.281 100.281 100.281 100.281 100.281 100.281 100.281  100.27 100.101 100.037
 100.048  99.965   99.98  99.902  99.941  99.757  99.862  99.706  99.662  99.864
  99.767  99.819 100.076 100.052  99.861  99.944  99.841  99.915   99.81  99.941
  99.787  99.779  99.685  99.763  99.685  99.758  99.746  99.834  99.721  99.806
  99.851  99.797  99.978  99.922  99.982  99.953  99.845 100.113 100.065 100.155
  99.998 100.032  99.961  99.966  99.884  99.974  99.926  99.959  99.871  99.809
  99.886  99.852  99.867  99.941  99.851  99.888  99.963  99.974  99.869  99.914
  99.988  99.958 100.016  99.941  99.963 100.107 100.104
                                                                                
                          99.381  99.381  99.381  99.381  99.381  99.381  99.381
  99.381  99.381  99.381  99.381  99.381  99.381  99.381
                                                                                
                                                                                
                                                                                
                                                                                
                                                                                
                                                                                
                                                        
Pier Skew, UpSta & Num, DnSta & Num=  ,444.5, 2 ,459.5, 2 , 0 , 0 , 0 ,,
     2.2     2.2
       0   101.7
     2.2     2.2
       0   101.7
Pier Skew, UpSta & Num, DnSta & Num=  ,459, 2 ,474, 2 , 0 , 0 , 0 ,,
     2.2     2.2
       0   101.7
     2.2     2.2
       0   101.7
Pier Skew, UpSta & Num, DnSta & Num=  ,473.5, 2 ,488.5, 2 , 0 , 0 , 0 ,,
     2.2     2.2
       0   101.7
     2.2     2.2
       0   101.7
BR Coef=-1 , 0 , 0 ,, 0 ,,,0.8,-1,,0,
WSPro=,,,, 1 ,,,, 0 ,,,, 0 ,,,,-1 ,-1 ,-1 , 0 , 0 , 0 , 0 , 0
BC Design=,, 0 ,, 0 ,,,,,,
BC HTab HWMax=107
BC Use User HTab Curves=0
BC User HTab FreeFlow(D)= 0

Type RM Length L Ch R = 1 ,0.3658  ,32.87,57.6,73.77
BEGIN DESCRIPTION:
DS of Badger Brook T'Railway Bridge - BB01 (SEM 2016)
END DESCRIPTION:
XS GIS Cut Line= 5
  571170.5725036 5425420.6496831  570780.8770036 5425249.5959831
  570678.3962036 5425285.4941831  570587.9176036 5425318.7818831
  570436.7640036 5425354.2499831
#Sta/Elev= 30
       0   104.4    5.99  105.12    7.99  104.12   10.99  104.83   32.97   104.9
   39.96  105.53   59.94  104.67   67.93  107.17   103.9  107.34  145.86  109.11
  159.84  108.82  215.79  111.19  267.74  112.27   303.7  112.02  374.63  108.79
  390.62  104.82  399.61  100.67   404.6  100.03  414.59  100.16  422.59   97.98
  427.58   98.24  439.81   96.83   446.5    96.8451.2679  95.172  484.97  95.144
 498.109   95.42  502.29   97.18  505.84   97.26  513.25   98.63   527.2   98.62
#Mann= 3 , 0 , 0
       0     .12       0  439.81     .05       0  505.84     .06       0
Bank Sta=439.81,505.84
XS Rating Curve= 0 ,0
Exp/Cntr=0.3,0.1

Type RM Length L Ch R = 1 ,0.3082  ,113.57,308.24,88.7
BEGIN DESCRIPTION:
Beothuck St - BB01A (SEM 2019)
END DESCRIPTION:
XS GIS Cut Line= 4
  571182.8069036 5425392.3022831  570791.3750036 5425231.5079831
  570740.0146036 5425212.1882831  570686.2015036 5425193.6251831
#Sta/Elev= 30
       0  104.24   17.96  104.53   23.95  105.96   37.93  104.78    49.9  106.91
   57.89  107.17   65.87  106.92   71.86  104.43   78.85  105.59   83.84  105.28
   93.82  106.66   102.8  105.16  121.76  105.02  138.73  107.62   154.7  108.71
  176.65  108.59  211.59   110.7  293.43  112.47  374.27  108.51  382.25  106.63
  389.24  102.49  394.23  100.35  402.21  100.05  411.19   98.63  423.57   97.69
  433.67   95.68460.3101   95.22  470.13   95.58  473.65   98.07  534.97   98.87
#Mann= 3 , 0 , 0
       0     .12       0  423.57     .05       0  473.65     .06       0
Bank Sta=423.57,473.65
XS Rating Curve= 0 ,0
Exp/Cntr=0.3,0.1

River Reach=Exploits River  ,Mill to LRI
Reach XY= 30
     529505.8193    5401248.4164     530125.0998    5400855.3156
     532155.0009    5400929.5075     533038.3953    5401286.7458
     533501.0345    5402090.2031     534131.1524    5402064.6121
     534973.0846     5403053.452     535614.2245    5403222.6048
     536664.6494    5403098.4255     537363.8841    5402451.5754
     538084.2779     5402255.336      540993.903    5403913.7179
     542673.1556    5405346.8805     546066.8446    5407081.0669
     550710.0121    5407848.0469     554104.3327    5410918.9777
     556454.0355    5412066.3609     556838.0825    5412602.1751
     556928.8157    5413523.9647     558045.4887    5413966.5614
      558977.503    5414835.9172     559324.1648      5415510.92
     560936.4088     5415443.238     561861.7757    5416045.8583
     562831.9203    5416237.6579     563493.3974    5416933.4445
     564072.3281    5417119.9702     566118.8344    5420335.3585
      566960.304    5422356.5228     570472.2323    5424925.2875