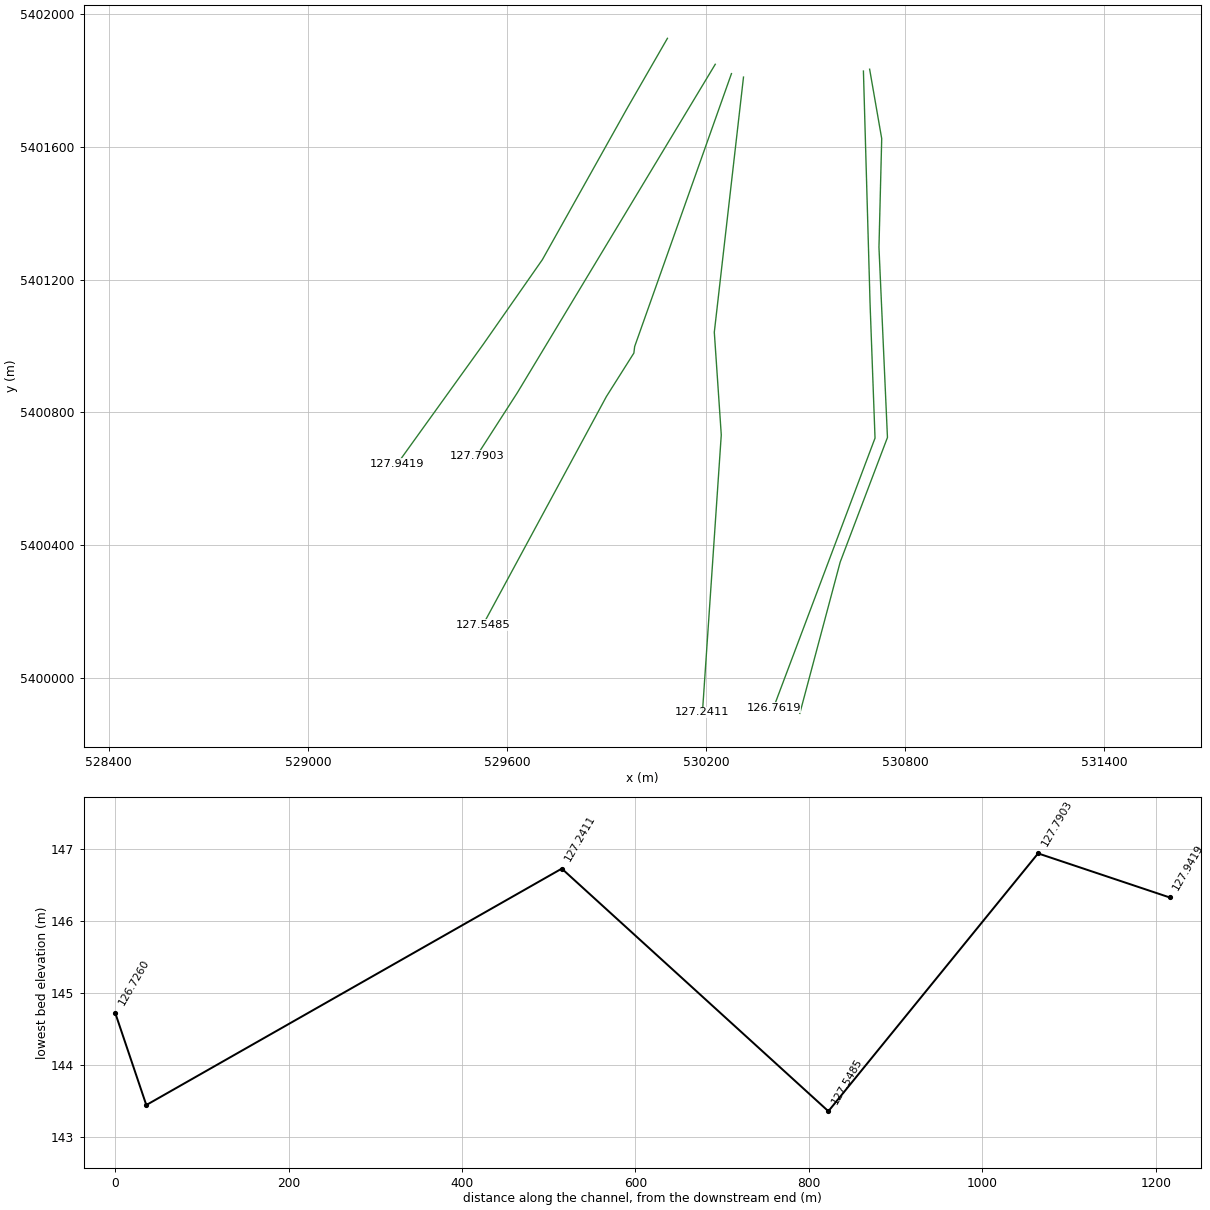
HEC-RAS study Unsteady_RAS.prj: Unsteady_RAS

--- Unsteady_RAS.g01 (geometry) --- (continued)

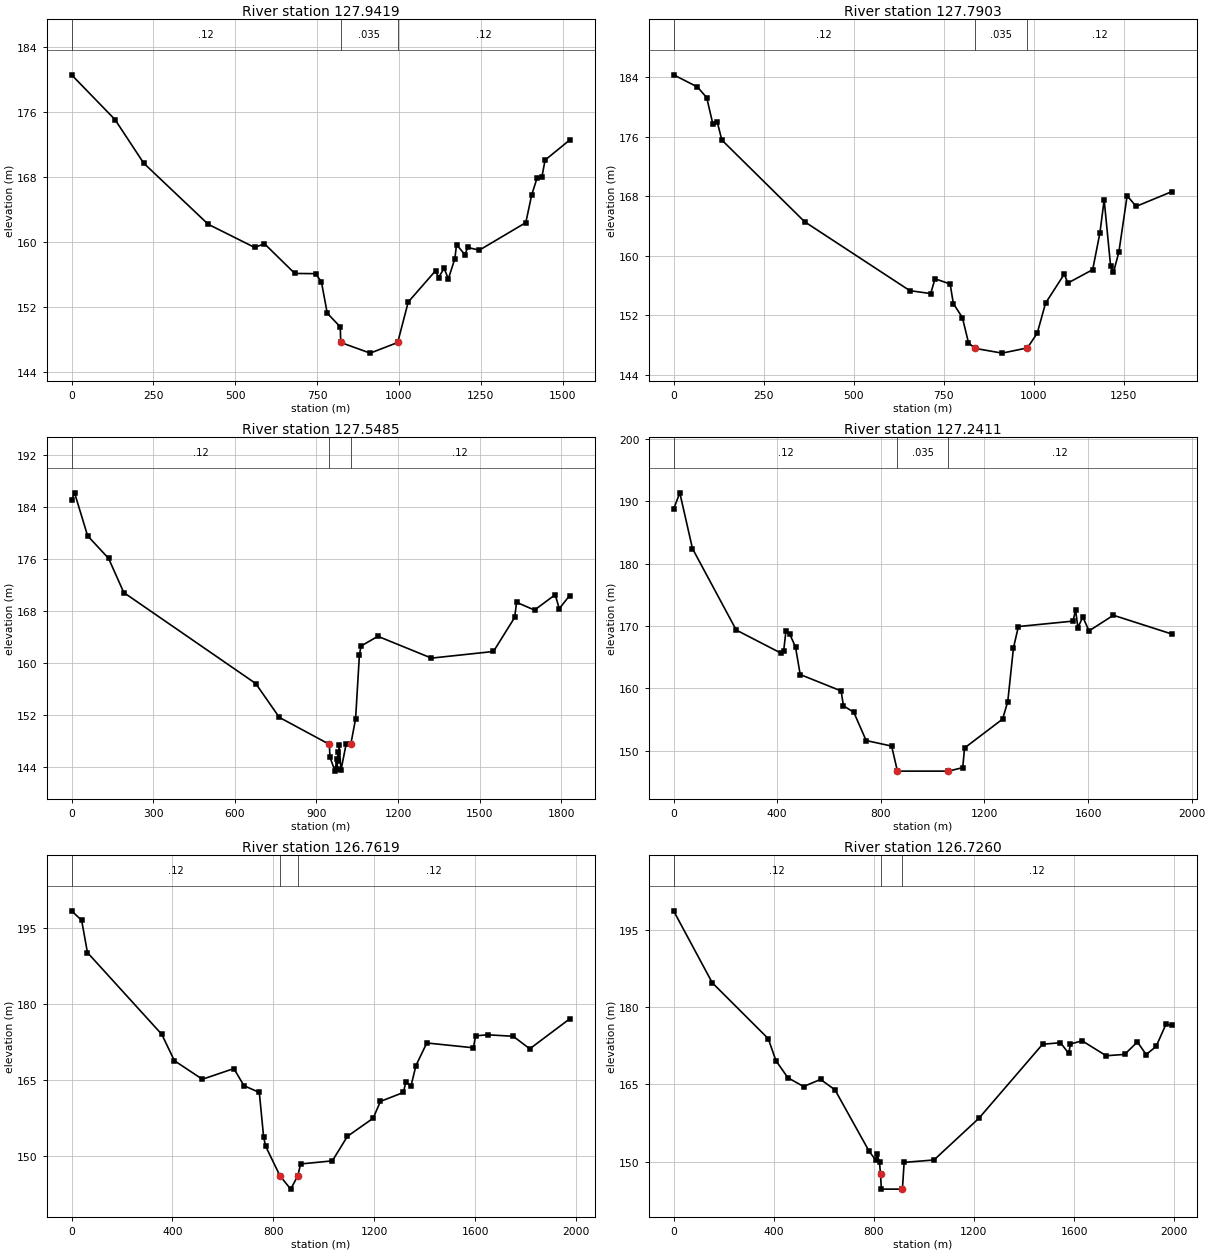
Type RM Length L Ch R = 1 ,127.9419,146.4,151.58,160.5
BEGIN DESCRIPTION:
DS of Millertown Dam
END DESCRIPTION:
XS GIS Cut Line= 6
     530083.9192    5401927.0055     529964.4462    5401719.5519
     529733.1242    5401306.5913     529706.9202    5401259.8116
     529528.2847    5401004.0531      529269.444    5400644.1052
#Sta/Elev= 30
       0   180.6  132.67  175.09  220.44  169.72  417.32   162.2  559.26  159.34
  589.25   159.8  682.03  156.14   745.5  156.11  763.37   155.1  781.25  151.24
  820.97  149.56  822.46 147.635  912.38 146.325  996.42 147.635 1028.63  152.62
 1112.27  156.48 1121.26  155.63 1138.23  156.77 1151.21  155.47 1171.18  157.97
 1176.17  159.69 1202.14  158.43 1210.12  159.34 1246.07  159.01 1387.86   162.4
 1405.84   165.8 1421.81  167.84 1436.79  167.97 1446.78   170.1 1521.67  172.56
#Mann= 3 , 0 , 0
       0     .12       0  822.46    .035       0  996.42     .12       0
Bank Sta=822.46,996.42
XS Rating Curve= 0 ,0
Exp/Cntr=0.3,0.1

Type RM Length L Ch R = 1 ,127.7903,256.39,241.84,238.63
XS GIS Cut Line= 6
     530228.0713    5401848.7729     530034.6293    5401527.7407
     529880.3172    5401271.6479     529756.9799    5401066.9604
     529631.6947    5400859.0405     529508.8178    5400668.0615
#Sta/Elev= 30
       0  184.29   65.97  182.67   91.95  181.23  108.94   177.7  120.94  178.02
  133.93  175.54  363.81  164.57   655.8  155.32  713.78  154.93  725.77  156.92
  767.74  156.21  776.74  153.58  801.72  151.71  818.71  148.34  835.69 147.585
  911.96 146.935  982.34 147.635 1009.67  149.63 1032.64  153.64 1084.58  157.54
 1094.57  156.34  1163.5  158.14 1183.42  163.03 1195.37   167.5  1213.3   158.6
 1221.27   157.8 1236.21   160.5 1259.11  168.07 1284.02  166.63 1382.62   168.6
#Mann= 3 , 0 , 0
       0     .12       0  835.69    .035       0  982.34     .12       0
Bank Sta=835.69,982.34
XS Rating Curve= 0 ,0
Exp/Cntr=0.3,0.1

Type RM Length L Ch R = 1 ,127.5485,263.94,307.43,365.77
BEGIN DESCRIPTION:
E39 (SEM 2016)
END DESCRIPTION:
XS GIS Cut Line= 6
     530276.9255    5401820.6485     530049.3458    5401178.9689
       529985.11    5400997.8514     529982.7909    5400978.3253
     529899.8657    5400847.0912     529527.6417    5400158.6539
#Sta/Elev= 30
       0  185.06      11  186.21   58.99  179.59  135.97  176.12  191.96  170.85
  676.84  156.85  763.49  151.64  947.44 147.485 949.826 145.483 968.587 143.359
 974.566 145.219 976.012 143.763 978.903 146.321 980.841 144.905  983.24 147.412
 990.385 143.5241008.937 147.467 1026.26 147.473 1043.94  151.41 1057.92   161.2
 1063.91  162.62 1125.88  164.12 1322.79  160.76 1550.69  161.78 1628.65  167.02
 1635.65  169.35 1701.62  168.16 1777.59  170.52 1792.58  168.37 1830.56  170.39
#Mann= 3 , 0 , 0
       0     .12       0  947.44    .035       0 1026.26     .12       0
Bank Sta=947.44,1026.26
XS Rating Curve= 0 ,0
Exp/Cntr=0.3,0.1

Type RM Length L Ch R = 1 ,127.2411,476.99,479.14,496.55
XS GIS Cut Line= 6
     530313.2251    5401810.2122     530225.2234    5401041.2049
     530236.9499    5400868.2961     530246.2156    5400731.6698
     530242.3029    5400674.0284      530189.454    5399895.4783
#Sta/Elev= 30
       0  188.74   23.99  191.37   72.96  182.42  241.86  169.36  413.77  165.67
  424.76  165.94  433.76  169.21  448.75  168.68  470.74  166.61  488.73  162.22
  646.64  159.59  655.63   157.2  695.61  156.17  743.25  151.63  841.75  150.74
  863.89 146.724 1061.11 146.724 1116.15  147.29 1123.12  150.44 1269.94  155.07
 1289.92  157.89  1311.9  166.49 1330.89  169.92  1541.7  170.79  1551.7  172.57
 1560.69  169.74 1579.67  171.45 1603.65  169.22 1697.57  171.73 1922.38  168.73
#Mann= 3 , 0 , 0
       0     .12       0  863.89    .035       0 1061.11     .12       0
Bank Sta=863.89,1061.11
XS Rating Curve= 0 ,0
Exp/Cntr=0.3,0.1

Type RM Length L Ch R = 1 ,126.7619,35.68,35.9,35.51
BEGIN DESCRIPTION:
02YO016 ER near Millertown - E38 (SEM 2016)
END DESCRIPTION:
XS GIS Cut Line= 4
     530674.7249    5401828.4028      530694.829    5401125.0389
     530709.7089    5400721.9466     530403.8395    5399909.5966
#Sta/Elev= 30
       0  198.35   39.98  196.47   62.97  190.11  357.82  173.98   407.8  168.78
  518.74  165.12  643.68  167.23  683.66  163.85  744.59  162.52  761.56  153.76
  769.55  151.91  826.46 146.075  868.99 143.445  897.35 146.085  908.33  148.41
 1034.13  149.02 1094.04  153.86 1195.92  157.43 1224.89  160.75 1315.79  162.51
 1325.78  164.59 1345.76  163.72 1365.74  167.82 1408.69  172.28 1593.49  171.33
 1602.48  173.69 1650.43  173.89 1751.32   173.6 1817.24  171.13 1975.07  177.02
#Mann= 3 , 0 , 0
       0     .12       0  826.46    .035       0  897.35     .12       0
Bank Sta=826.46,897.35
XS Rating Curve= 0 ,0
Exp/Cntr=0.3,0.1

Type RM Length L Ch R = 1 ,126.7260,17.2,15.76,16.12
BEGIN DESCRIPTION:
US of Exploits Bridge
END DESCRIPTION:
XS GIS Cut Line= 6
     530693.4413    5401833.9417      530729.852    5401624.7316
     530721.5725    5401296.8047     530747.1622    5400723.8137
     530604.6773    5400348.1683     530483.0029    5399892.1187
#Sta/Elev= 30
       0  198.65  154.53  184.71  378.07  173.89  408.94  169.61  456.74   166.3
  519.47  164.61  587.16  165.98  644.89  163.96  781.19  152.06  806.95  150.39
  812.88  151.49  822.77   149.9  826.73  147.56 830.144 144.725 914.189 144.725
  921.09  149.91 1040.19  150.37  1219.6  158.44 1474.06  172.79 1545.64   173.1
 1578.57  171.02 1585.56  172.85 1632.46  173.46 1728.25  170.57  1802.1  170.83
 1852.99  173.25 1887.92   170.8 1927.83  172.37 1966.75  176.64  1989.7  176.48
#Mann= 3 , 0 , 0
       0     .12       0  826.73    .035       0 914.189     .12       0
Bank Sta=826.73,914.189
XS Rating Curve= 0 ,0
Exp/Cntr=0.3,0.1

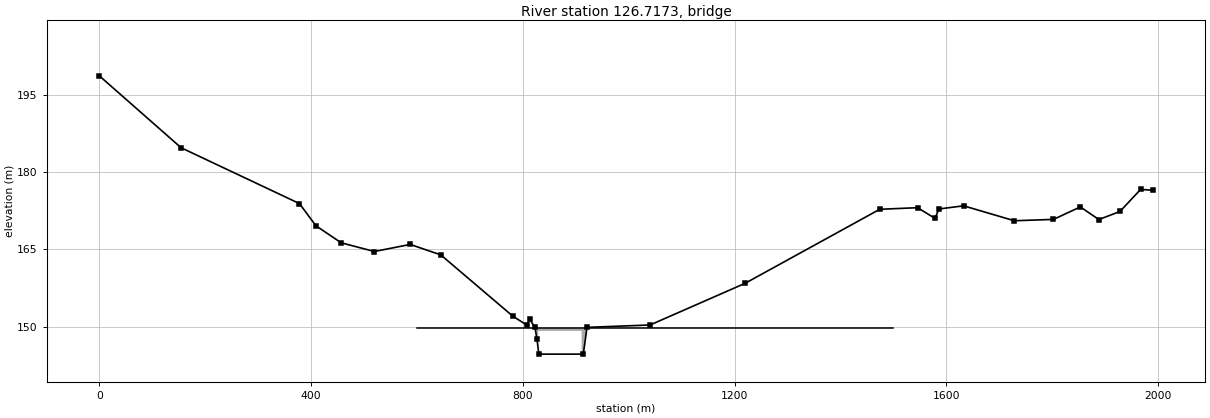
Type RM Length L Ch R = 3 ,126.7173,,,
BEGIN DESCRIPTION:
Exploits Bailey Bridge
END DESCRIPTION:
Bridge Culvert--1,0,-1,-1, 0
Deck Dist Width WeirC Skew NumUp NumDn MinLoCord MaxHiCord MaxSubmerge Is_Ogee
3.3,7.8,1.4,0, 6, 6, , , 0.98, 0, 0,0,,
     600     829     829     911     911    1500
 149.725 149.725 149.725 149.725 149.725 149.725
       0       0 149.225 149.225       0       0
     600  834.49  834.49     911     911    1500
 149.725 149.725 149.725 149.725 149.725 149.725
       0       0 149.225 149.225       0       0
BR Coef=-1 , 0 , 0 ,, 0 ,,,0.8,-1,,0,
WSPro=,,,, 1 ,,,, 0 ,,,, 0 ,,,,-1 ,-1 ,-1 , 0 , 0 , 0 , 0 , 0
BC Design=,, 0 ,, 0 ,,,,,,
BC HTab HWMax=164
BC Use User HTab Curves=0
BC User HTab FreeFlow(D)= 0