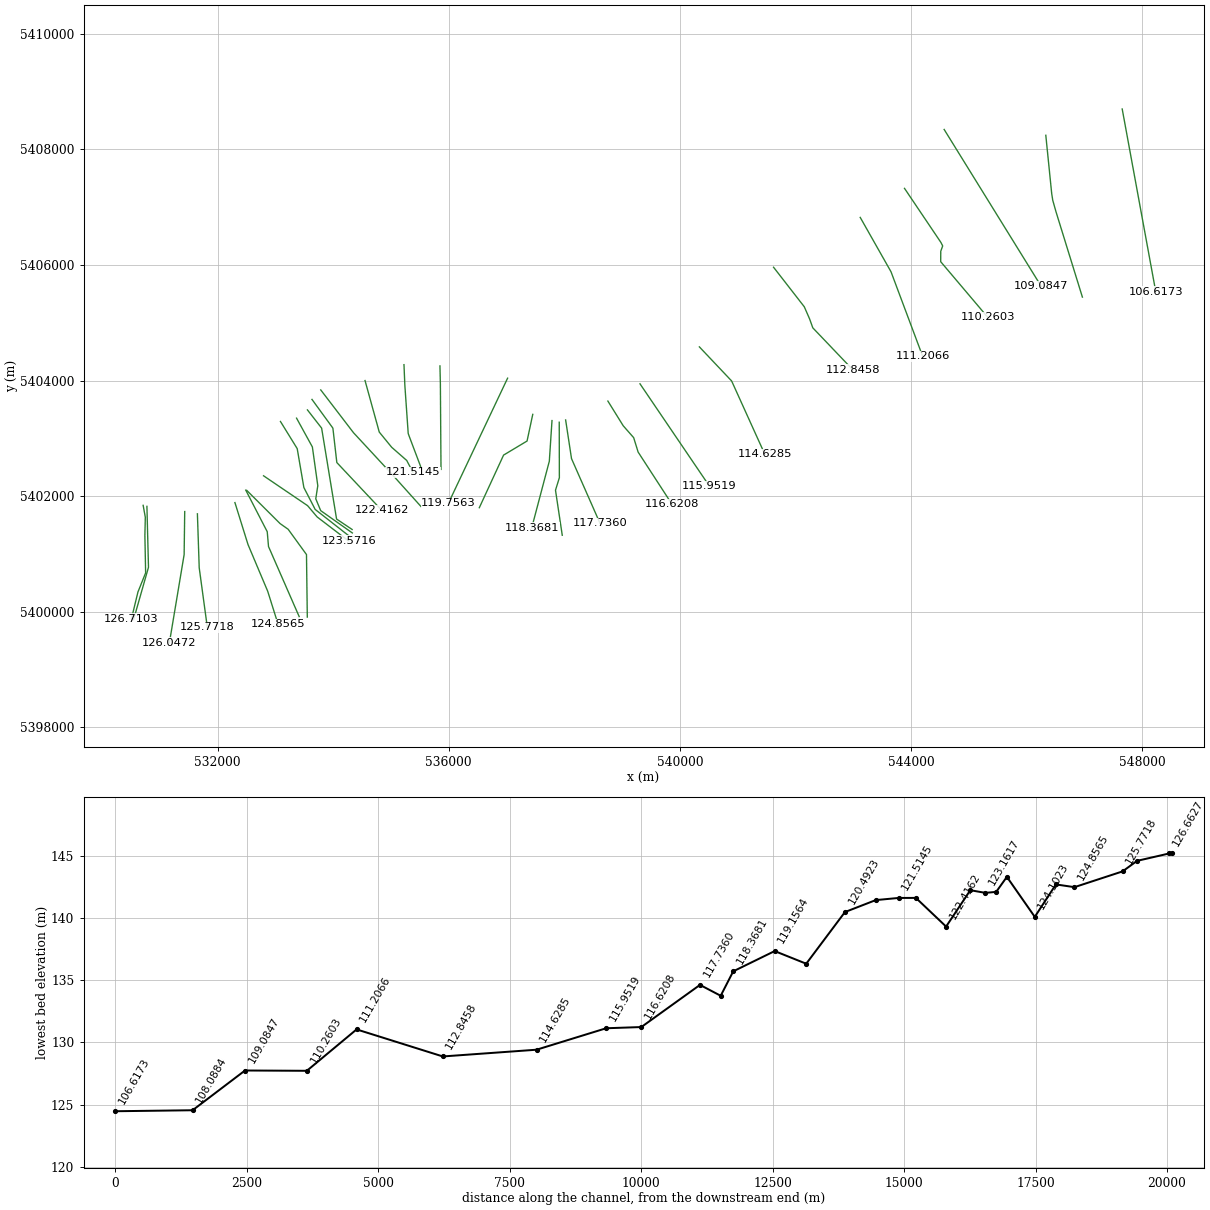
HEC-RAS study Unsteady_RAS.prj: Unsteady_RAS

--- Unsteady_RAS.g01 (geometry) --- (continued)

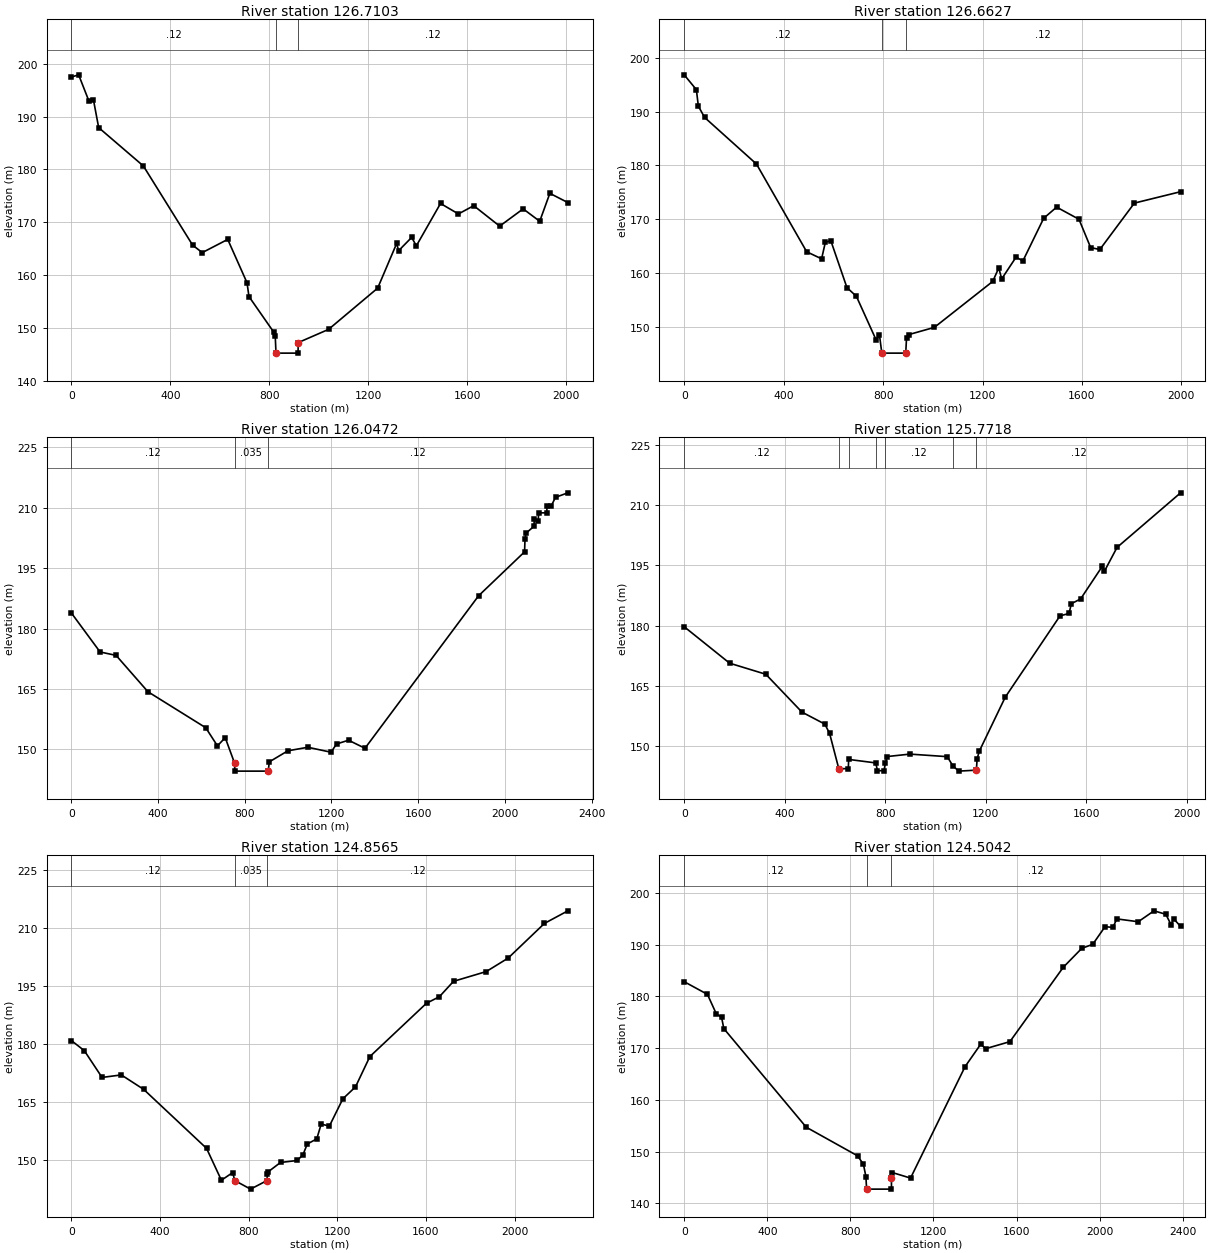
Type RM Length L Ch R = 1 ,126.7103,47.22,47.56,47.15
BEGIN DESCRIPTION:
DS of Exploits Bridge
END DESCRIPTION:
XS GIS Cut Line= 6
     530712.6945    5401840.7123     530750.1104    5401634.2396
     530742.7448    5401318.4032     530755.5081    5400671.5793
     530622.7564    5400341.2659     530510.0752    5399877.1315
#Sta/Elev= 30
       0  197.49   28.98   197.9   70.94  192.88   88.93  193.14  109.91  187.91
  290.65  180.65   489.9  165.66  528.78  164.25  631.73  166.75  709.66  158.55
  717.63  155.93  817.74   149.2 823.845 148.429  826.87 145.225 915.866 145.225
  916.98 147.225 1039.41  149.72 1237.99  157.53 1314.71  165.98 1322.67  164.61
 1375.41  167.13 1394.32  165.53 1492.06  173.55 1564.42  171.57 1626.37  173.13
 1731.28  169.26  1826.2  172.53 1893.15  170.18 1934.12  175.47 2007.06  173.72
#Mann= 3 , 0 , 0
       0     .12       0  826.87    .035       0  916.98     .12       0
Bank Sta=826.87,916.98
XS Rating Curve= 0 ,0
Exp/Cntr=0.3,0.1

Type RM Length L Ch R = 1 ,126.6627,636.49,615.55,614.09
XS GIS Cut Line= 3
     530777.8506    5401823.3022     530804.9257    5400768.2052
     530546.9935     5399862.792
#Sta/Elev= 30
       0   196.8   48.97  194.05   56.97  190.99   81.96  188.91  290.85  180.26
  492.74  164.01  552.71   162.7   567.7  165.74  589.69  166.08  654.66  157.37
  692.64  155.76   771.6  147.72  785.59  148.56  795.01 145.225  891.13 145.225
  894.53   148.1  903.53  148.66 1006.47     150 1241.33  158.52 1265.32  161.02
 1277.31  158.99 1335.28  163.03 1362.26  162.29 1446.21  170.22 1498.18  172.28
 1588.12  170.03  1635.1  164.78 1672.07  164.43 1810.99  173.03 1996.88  175.14
#Mann= 3 , 0 , 0
       0     .12       0  795.01    .035       0  891.13     .12       0
Bank Sta=795.01,891.13
XS Rating Curve= 0 ,0
Exp/Cntr=0.3,0.1

Type RM Length L Ch R = 1 ,126.0472,263.67,275.39,451.09
XS GIS Cut Line= 6
     531431.9082     5401732.948     531423.0495    5401069.4261
     531421.9701    5400988.5859     531405.4493    5400889.6454
     531363.2926    5400637.1753     531167.2506    5399463.1203
#Sta/Elev= 30
       0  183.85  131.92  174.21  205.87  173.36  352.78  164.34  619.61   155.4
  673.56   150.9  709.49  152.93  752.37  146.66 753.848 144.625  908.26 144.625
  912.73  146.92  998.72  149.67 1090.71  150.55 1197.65  149.32 1223.63  151.37
  1278.6   152.3 1354.55   150.3 1879.23  188.18 2091.11  199.07 2093.11  202.29
  2098.1  203.72 2134.08  205.39 2136.08  207.18 2154.07  206.82 2156.07  208.75
 2193.05  208.75 2195.05  210.37 2213.04  210.37 2234.03  212.61    2291  213.72
#Mann= 3 , 0 , 0
       0     .12       0  752.37    .035       0  908.26     .12       0
Bank Sta=752.37,908.26
XS Rating Curve= 0 ,0
Exp/Cntr=0.3,0.1

Type RM Length L Ch R = 1 ,125.7718,856.73,915.26,1015.11
XS GIS Cut Line= 6
     531651.5385    5401693.5439     531671.3391    5401103.2408
     531678.8104    5400880.4983     531682.8283    5400760.7109
     531697.0695    5400656.0296     531823.3568     5399727.734
#Sta/Elev= 30
       0   179.7  180.89  170.63   324.8  167.88  468.71  158.46  559.65  155.48
  578.64  153.19 615.273 144.401 653.281 144.382   654.6  146.69  762.54  145.82
 769.305 143.874 795.287 143.894  800.51  145.73  808.51  147.41   898.4  148.01
 1047.01  147.38    1069  145.141092.522 143.7771163.047 144.022 1165.99  146.88
 1174.99  148.79 1277.97  162.18 1495.94  182.41 1531.93     183 1540.93  185.44
 1577.93  186.62 1663.91  194.71 1672.91  193.54 1722.91  199.44 1975.87  213.02
#Mann= 7 ,-1 , 0
       0     .12       0 615.273    .035       0   654.6     .12       0
  762.54    .035       0  800.51     .12       0    1069    .035       0
1163.047     .12       0
Bank Sta=615.273,1163.047
XS Rating Curve= 0 ,0
Exp/Cntr=0.3,0.1

Type RM Length L Ch R = 1 ,124.8565,379.59,352.29,333.1
XS GIS Cut Line= 6
     532300.8986    5401888.1507     532527.3127    5401162.0206
     532551.2177    5401105.3231     532619.6728    5400942.9625
     532868.0471    5400353.8708     533049.1264    5399778.5236
#Sta/Elev= 30
       0  180.84   57.98  178.25  137.94  171.34   224.9  171.99  325.86  168.26
  609.74  153.03  676.69   144.8  727.64  146.78  737.06 144.727  808.31 142.507
  883.01 144.727  883.87  146.32  886.85  146.93   943.6  149.39 1019.33   149.9
  1045.3  151.42 1064.28  154.15 1107.23  155.48 1127.21   159.3 1164.17  158.78
 1225.11  165.83 1282.05   168.9 1346.98  176.73 1602.71   190.5 1660.64  192.17
 1724.56  196.15 1872.35  198.67 1971.21  202.15 2134.99   211.1 2240.85  214.35
#Mann= 3 , 0 , 0
       0     .12       0  737.06    .035       0  883.01     .12       0
Bank Sta=737.06,883.01
XS Rating Curve= 0 ,0
Exp/Cntr=0.3,0.1

Type RM Length L Ch R = 1 ,124.5042,337.4,401.89,491.22
XS GIS Cut Line= 6
     532488.5325     5402103.292     532820.9539    5401459.7091
     532859.8394    5401384.4248     532882.2562    5401127.6003
     532909.2417    5401065.9085     533412.4003    5399915.6244
#Sta/Elev= 30
       0  182.83   111.9  180.38  154.86  176.59  179.84  175.96  190.83  173.76
  587.49   154.7     835  149.16   862.9  147.52  874.85  145.14  878.09 142.728
 997.775 142.728  997.91 144.881 1002.27  145.93 1089.68  144.86 1352.16  166.41
 1427.13  170.72 1452.12  169.89 1568.08  171.24 1824.99  185.62 1913.96  189.27
 1966.94  190.06 2025.92  193.46  2063.9  193.33 2082.89  194.97 2185.85  194.42
 2261.82  196.53  2318.8  195.86 2343.79  193.85 2356.78  194.98 2389.77  193.51
#Mann= 3 , 0 , 0
       0     .12       0  878.09    .035       0  997.91     .12       0
Bank Sta=878.09,997.91
XS Rating Curve= 0 ,0
Exp/Cntr=0.3,0.1

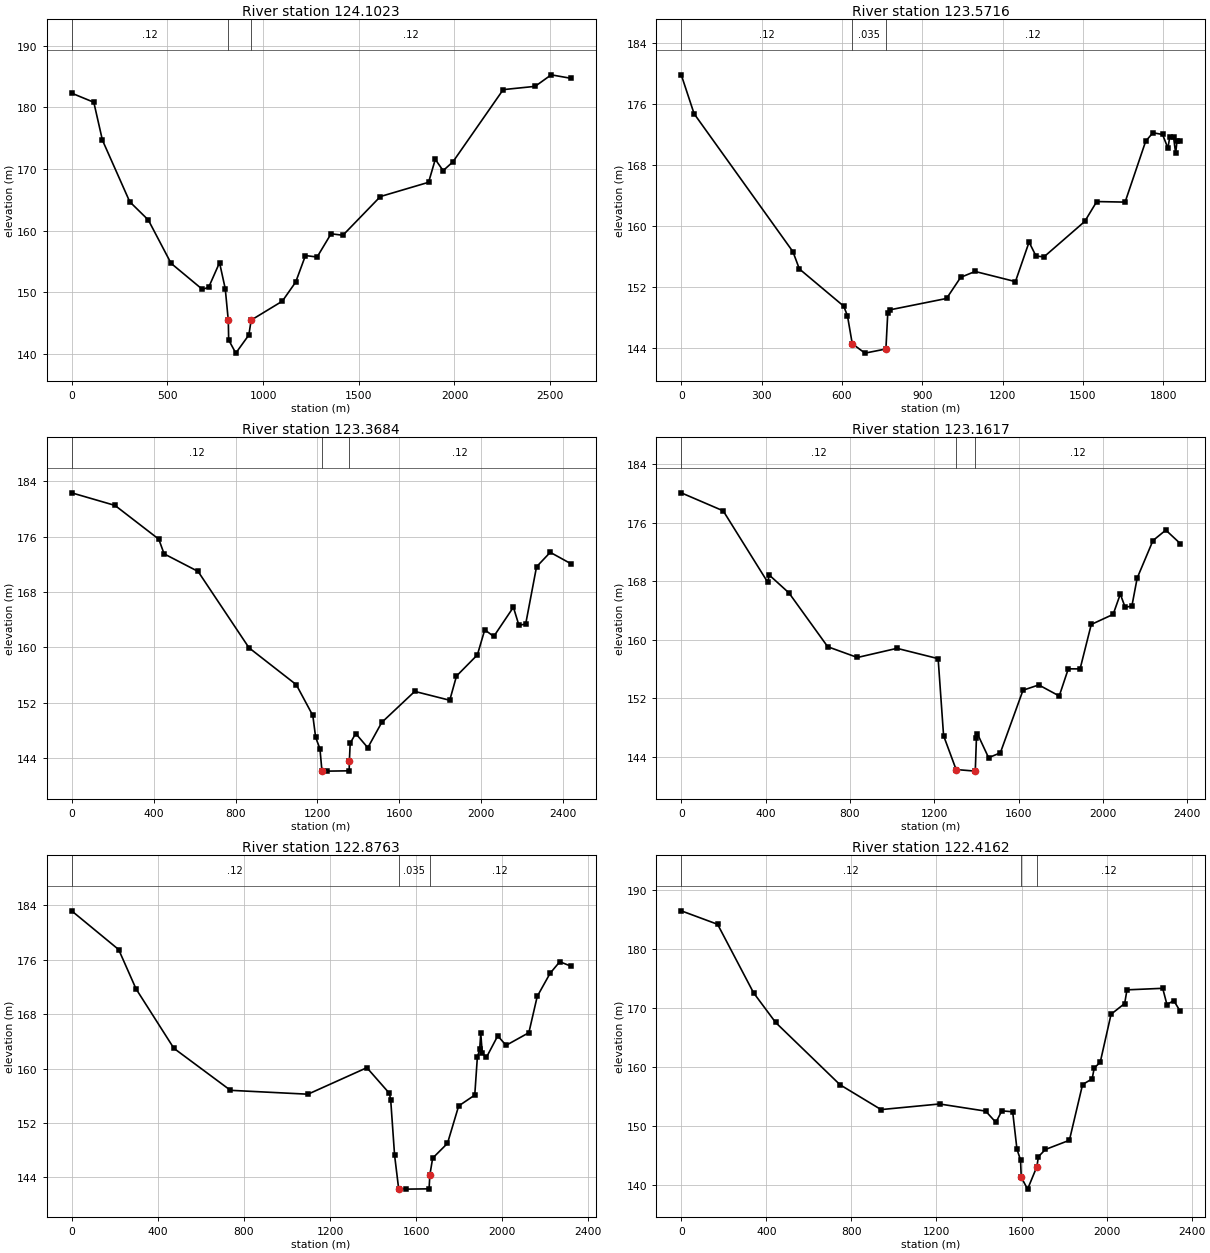
Type RM Length L Ch R = 1 ,124.1023,533.43,530.75,532.18
BEGIN DESCRIPTION:
E37 (SEM 2016)
END DESCRIPTION:
XS GIS Cut Line= 6
     532505.7291    5402099.0737     532987.0839    5401619.7142
     533081.4557    5401525.7334     533222.4342    5401426.0061
     533539.2532    5400988.9358     533553.4569    5399906.6829
#Sta/Elev= 30
       0  182.28  115.89   180.8  160.84  174.66   303.7  164.66   400.6  161.71
  519.49  154.68  683.31  150.45  716.11   150.8  772.76  154.79  802.57  150.56
   818.5 145.409 820.455 142.252  857.68 140.115 925.866 143.056  937.91  145.47
 1100.74  148.54 1170.62  151.64 1221.54  155.94 1282.43   155.7 1355.31  159.47
  1417.2  159.23 1612.96  165.51 1864.81  167.82 1899.79  171.54 1940.77  169.71
 1991.74  171.13 2254.56  182.85 2421.44  183.38 2505.38  185.25 2607.31  184.69
#Mann= 3 , 0 , 0
       0     .12       0   818.5    .035       0  937.91     .12       0
Bank Sta=818.5,937.91
XS Rating Curve= 0 ,0
Exp/Cntr=0.3,0.1

Type RM Length L Ch R = 1 ,123.5716,239.58,203.22,170.46
BEGIN DESCRIPTION:
Harpoon Brook
END DESCRIPTION:
XS GIS Cut Line= 6
     532796.3526    5402351.7543     533234.9884    5402054.2969
     533558.6234    5401834.8259     533723.0683    5401640.1773
     534261.7597     5401228.239      534271.281     5401228.364
#Sta/Elev= 30
       0  179.81      48  174.71  416.99  156.63  440.99  154.37  606.64  149.49
  620.58  148.23   638.5  144.57 685.855 143.337  764.16  143.88  771.15  148.65
  779.15  149.01  990.52   150.5 1043.32  153.27 1097.12  154.04 1247.74  152.71
 1298.68  157.89 1324.64  156.05 1354.61  155.96 1506.41  160.59 1551.36   163.2
 1657.22  163.13 1734.12  171.11 1761.09  172.22 1797.04  171.99 1817.02  170.21
 1824.01  171.65 1837.99  171.69 1845.98  169.52 1850.97   171.1 1863.49  171.14
#Mann= 3 , 0 , 0
       0     .12       0   638.5    .035       0  764.16     .12       0
Bank Sta=638.5,764.16
XS Rating Curve= 0 ,0
Exp/Cntr=0.3,0.1

Type RM Length L Ch R = 1 ,123.3684,254.4,206.7,170.81
XS GIS Cut Line= 6
     533088.7417    5403292.0131     533378.7206    5402822.0506
     533494.1975    5402148.2367     533664.7161    5401818.1051
     533689.6226    5401769.8849     534299.0118    5401292.2143
#Sta/Elev= 30
       0  182.35   211.7  180.53   425.4  175.65  451.37  173.53  617.14  170.99
   865.8  159.95 1096.49  154.62 1177.17  150.17  1191.1     147 1211.99  145.36
1221.809 142.151 1247.39 142.1271354.721 142.172 1355.71  143.62  1359.7  146.18
 1386.67  147.56 1445.61  145.51 1513.53  149.16 1674.69  153.65 1845.53  152.37
  1878.5  155.87 1980.41  158.93 2016.38  162.55 2060.34  161.59 2156.25  165.82
 2183.22   163.2 2216.19  163.39 2269.14  171.66 2336.07  173.75 2435.97  172.12
#Mann= 3 , 0 , 0
       0     .12       01221.809    .035       0 1355.71     .12       0
Bank Sta=1221.809,1355.71
XS Rating Curve= 0 ,0
Exp/Cntr=0.3,0.1

Type RM Length L Ch R = 1 ,123.1617,264.8,285.33,341.35
XS GIS Cut Line= 6
     533367.3243    5403349.6339     533641.1778    5402850.9695
     533735.0284    5402179.9669     533699.9013    5401954.1298
     533785.1272    5401748.9184     534333.0067    5401362.4953
#Sta/Elev= 30
       0  180.06  198.97   177.6  409.94  167.86  417.94  168.82  510.92  166.39
  694.77  159.04   835.6  157.57 1023.37  158.82 1218.67  157.41 1244.47  146.89
1303.947 142.265 1394.82 142.048 1400.36  146.57 1405.34  147.13 1458.08  143.88
 1513.79  144.55 1621.31   153.1 1696.21  153.82 1793.13  152.31 1836.09  156.02
 1892.04  156.01    1945  162.08 2048.91  163.46 2082.89  166.23 2105.87  164.42
 2137.85   164.6 2162.83  168.41 2237.77  173.54 2298.72  174.97 2367.67  173.12
#Mann= 3 , 0 , 0
       0     .12       01303.947    .035       0 1394.82     .12       0
Bank Sta=1303.947,1394.82
XS Rating Curve= 0 ,0
Exp/Cntr=0.3,0.1

Type RM Length L Ch R = 1 ,122.8763,427.62,460.15,513.31
XS GIS Cut Line= 6
     533555.9164    5403491.7797     533801.2509    5403177.0837
      533942.971    5402315.2208     534014.0772    5401882.7897
     534060.0289    5401603.3343     534329.0414    5401422.7552
#Sta/Elev= 30
       0  183.21  218.47  177.51  299.27  171.72  474.98  162.98  737.81   156.8
 1097.57  156.23 1371.23  160.13 1475.98  156.35 1481.96  155.35 1499.92  147.25
 1518.83 142.3171554.886 142.2631660.065 142.306 1663.73  144.35 1676.72  146.82
 1745.62     149 1797.47   154.5 1872.26   156.1 1884.22  161.63 1895.19  162.87
 1900.18  165.21 1907.16  162.22 1926.11  161.63 1978.96  164.81 2017.84  163.42
 2123.51  165.28 2162.39  170.62 2222.21  174.02 2267.07  175.72 2317.91  175.08
#Mann= 3 , 0 , 0
       0     .12       0 1518.83    .035       0 1663.73     .12       0
Bank Sta=1518.83,1663.73
XS Rating Curve= 0 ,0
Exp/Cntr=0.3,0.1

Type RM Length L Ch R = 1 ,122.4162,604.52,574.75,568.14
BEGIN DESCRIPTION:
E36 (SEM 2016)
END DESCRIPTION:
XS GIS Cut Line= 6
     533634.1548    5403673.7426     533996.2002     5403176.955
     534064.3351    5402581.0789     534137.6282    5402503.1736
     534460.8021    5402159.6619     534840.1703    5401756.4189
#Sta/Elev= 30
       0  186.42  170.92  184.14  339.84  172.56  443.79  167.53  746.66  156.99
  939.58  152.79 1214.47  153.74 1431.42  152.53 1479.42  150.63 1507.41  152.58
 1558.41  152.42 1578.41   146.1  1595.4  144.251598.605  141.341628.516 139.333
 1672.31  143.15 1679.29  144.82 1712.23  146.04 1825.06   147.6 1887.02  157.03
 1931.99  157.99 1941.98  159.84 1969.97  160.79 2020.93  168.92 2084.89  170.74
 2095.89  173.05 2263.79  173.31 2283.78  170.56 2315.76  171.23 2346.74  169.39
#Mann= 3 , 0 , 0
       0     .12       01598.605    .035       0 1672.31     .12       0
Bank Sta=1598.605,1672.31
XS Rating Curve= 0 ,0
Exp/Cntr=0.3,0.1

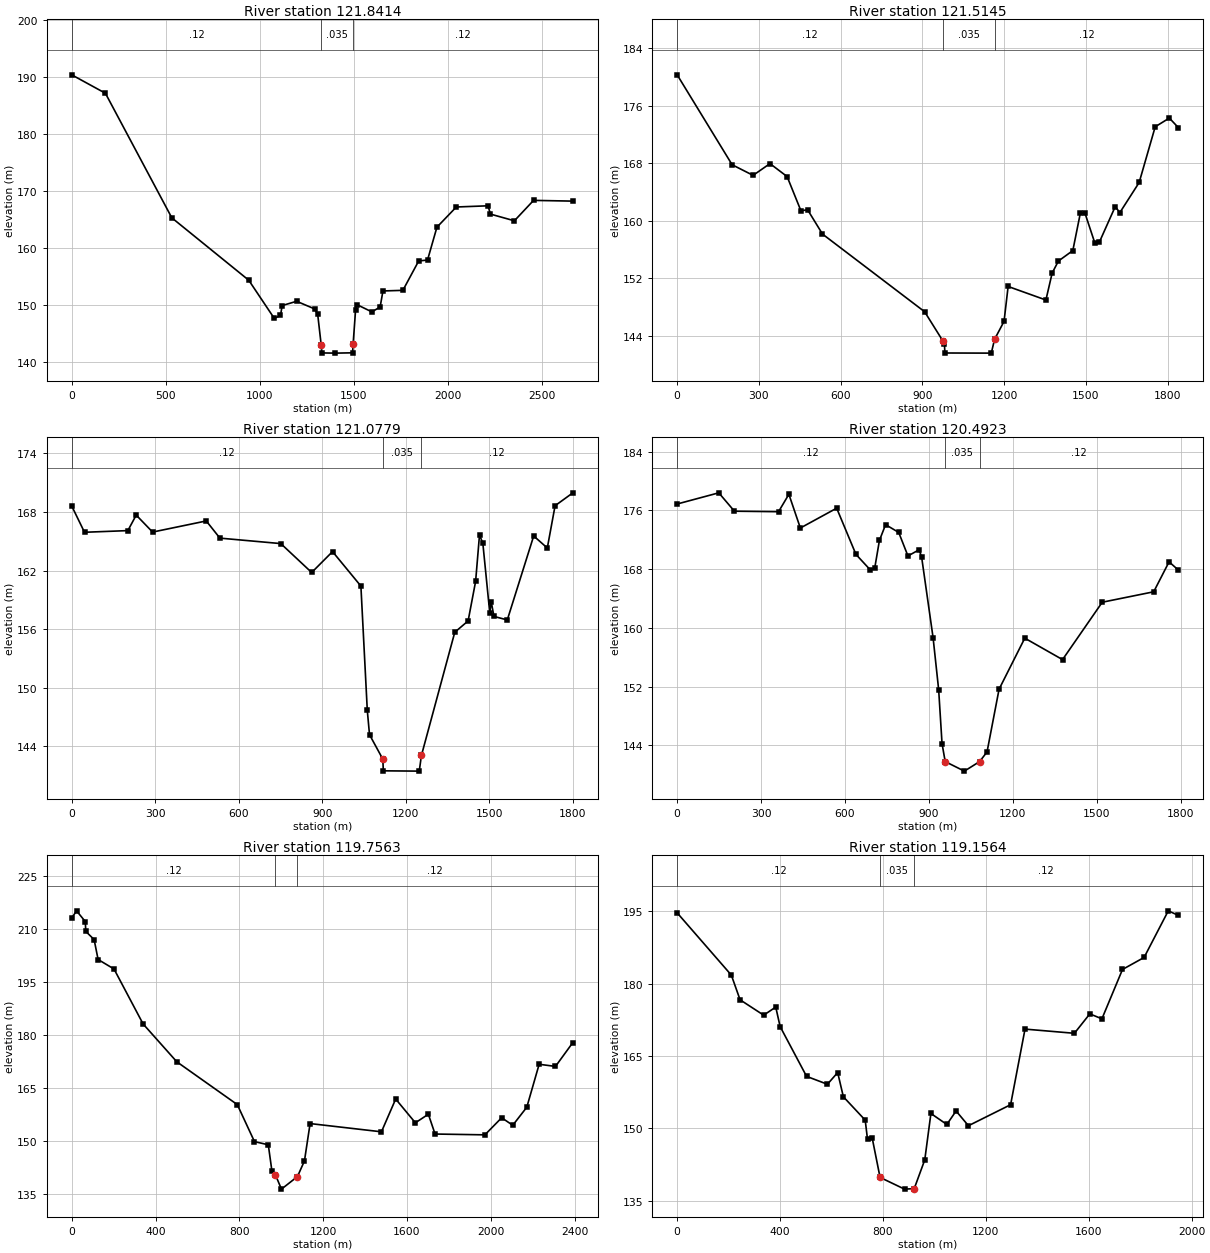
Type RM Length L Ch R = 1 ,121.8414,339.5,326.96,323.17
XS GIS Cut Line= 6
     533786.2744    5403837.6298     534351.4758    5403099.0873
     534675.5884    5402749.0947     534825.7921    5402586.8972
     535036.3437    5402359.5329     535521.1549    5401819.8444
#Sta/Elev= 30
       0  190.43     179   187.2     532  165.36  940.96  154.42 1076.56  147.73
 1109.47  148.24 1118.44  149.98 1195.32  150.73 1291.18  149.39 1307.15  148.47
 1326.13     1431329.318 141.6781400.997 141.6421492.582 141.697 1495.63  143.28
 1508.57  149.19 1515.54  150.15  1595.2  148.87 1639.06  149.73 1654.05  152.54
 1760.01  152.65 1843.98   157.8 1890.96  157.96 1940.94  163.72 2043.87  167.26
 2212.74  167.47 2224.74  166.02 2352.64  164.84 2454.57  168.42 2663.41  168.29
#Mann= 3 , 0 , 0
       0     .12       0 1326.13    .035       0 1495.63     .12       0
Bank Sta=1326.13,1495.63
XS Rating Curve= 0 ,0
Exp/Cntr=0.3,0.1

Type RM Length L Ch R = 1 ,121.5145,510.63,436.62,421.87
XS GIS Cut Line= 6
     534552.3254    5404000.0554     534761.8651    5403242.2098
     534798.9354    5403108.1363     535012.9942    5402846.0645
     535274.1189    5402617.0239     535380.6256    5402414.7812
#Sta/Elev= 30
       0  180.26  201.82  167.78  278.75  166.31  340.69  167.94  403.63  166.14
  454.58  161.37  478.56  161.55  533.51  158.16   908.5  147.38  975.07  143.35
  981.03  142.96 982.801 141.658 1153.16 141.639 1165.12  143.55    1200  146.05
 1214.95  150.89 1353.61  149.01 1376.56  152.75 1399.52  154.42 1452.42  155.87
 1480.37  161.13 1497.33  161.03 1533.26  156.92 1550.23  157.07 1608.12  161.97
 1625.09  161.14 1695.96  165.32 1754.84  173.05 1806.75  174.26 1839.68  172.94
#Mann= 3 , 0 , 0
       0     .12       0  975.07    .035       0 1165.12     .12       0
Bank Sta=975.07,1165.12
XS Rating Curve= 0 ,0
Exp/Cntr=0.3,0.1

Type RM Length L Ch R = 1 ,121.0779,586.92,585.54,574.22
XS GIS Cut Line= 6
     535226.5108    5404275.0156      535241.194    5403923.7687
     535289.0529    5403236.9187      535299.743    5403083.4973
     535311.2315    5403050.6979     535513.5933    5402515.5628
#Sta/Elev= 30
       0  168.62   45.94  165.93  201.74   166.1  231.71  167.69  290.63  165.95
  483.46  167.09  532.43  165.33  751.27  164.77   862.2  161.81  937.14  163.95
 1039.07  160.42 1062.02   147.7    1070   145.2 1117.88  142.691119.606 141.496
1248.716 141.465 1256.57  143.07 1376.39  155.69 1424.31  156.85 1451.27   160.9
 1465.25  165.66 1477.23   164.8 1502.19  157.66 1507.18  158.83 1517.17  157.31
 1565.09  156.95 1659.94  165.55 1708.87  164.32 1736.82  168.65 1800.72  169.97
#Mann= 3 , 0 , 0
       0     .12       0 1117.88    .035       0 1256.57     .12       0
Bank Sta=1117.88,1256.57
XS Rating Curve= 0 ,0
Exp/Cntr=0.3,0.1

Type RM Length L Ch R = 1 ,120.4923,772.66,736.03,708.52
XS GIS Cut Line= 6
     535848.9593     5404253.562     535856.4625    5403936.2585
     535860.9884    5403310.9812     535861.5221    5403237.2468
      535862.131    5403153.1104     535867.3515     5402462.492
#Sta/Elev= 30
       0  176.86  148.72  178.38  204.61  175.88  362.34  175.81   399.3  178.18
  440.25  173.59  570.11  176.29  639.03     170  690.97  167.86  705.95   168.1
  722.93   171.9  744.91  174.05  791.86  172.99  824.82  169.79  864.77  170.63
  873.76  169.64  914.72  158.66   934.7  151.56  946.67  144.26  957.94 141.802
 1026.51 140.502 1081.07 141.802 1107.56  143.12 1150.53  151.65 1242.48   158.6
 1377.41  155.68 1519.33  163.49 1703.23  164.91  1758.2  168.99 1791.18  167.87
#Mann= 3 , 0 , 0
       0     .12       0  957.94    .035       0 1081.07     .12       0
Bank Sta=957.94,1081.07
XS Rating Curve= 0 ,0
Exp/Cntr=0.3,0.1

Type RM Length L Ch R = 1 ,119.7563,652.27,599.9,552.88
BEGIN DESCRIPTION:
E35 (SEM 2016)
END DESCRIPTION:
XS GIS Cut Line= 5
     537019.7128    5404041.3418     536623.6031    5403204.2395
     536582.5958    5403117.5784     536486.2617    5402913.9953
     535996.7578    5401879.5279
#Sta/Elev= 30
       0  213.08   22.98  215.13   64.94  212.08   66.93  209.32  106.89  206.99
  125.88  201.35   201.8  198.66  340.66   183.1  501.51  172.39  790.23  160.27
  872.15  149.79  938.08   148.9  955.06  141.61  972.04   140.41000.847 136.342
 1077.31   139.9 1110.67  144.34 1137.57   154.9 1478.08  152.57 1546.05  161.85
    1640  155.12 1701.97  157.55 1733.95  151.94 1971.83  151.71 2051.79  156.55
 2104.76  154.42 2171.73  159.53  2230.7  171.69 2308.66  171.08 2391.62  177.85
#Mann= 3 , 0 , 0
       0     .12       0  972.04    .035       0 1077.31     .12       0
Bank Sta=972.04,1077.31
XS Rating Curve= 0 ,0
Exp/Cntr=0.3,0.1

Type RM Length L Ch R = 1 ,119.1564,743.23,788.29,842.46
XS GIS Cut Line= 6
      537455.139    5403414.9229     537356.4462    5402953.3491
     537100.0565    5402799.7469     536950.1532    5402709.9404
     536928.5618     5402663.122     536530.3932    5401799.7467
#Sta/Elev= 30
       0  194.66  210.56  181.75  244.49  176.63  336.29  173.44  383.19  175.12
  400.16  171.08  502.99  160.75  583.96  159.11  623.94  161.54  645.93  156.52
   730.9  151.67  739.89  147.68  757.89  148.02  788.66  139.79 883.784 137.361
  921.47 137.465  962.48  143.44  986.28  153.05 1048.17  150.77 1084.16  153.57
 1132.15  150.51 1296.11  154.87  1352.1  170.55 1544.05  169.68 1604.03  173.71
 1651.02  172.68    1731  182.92 1814.98  185.41 1908.96  195.08 1947.95  194.14
#Mann= 3 , 0 , 0
       0     .12       0  788.66    .035       0  921.47     .12       0
Bank Sta=788.66,921.47
XS Rating Curve= 0 ,0
Exp/Cntr=0.3,0.1

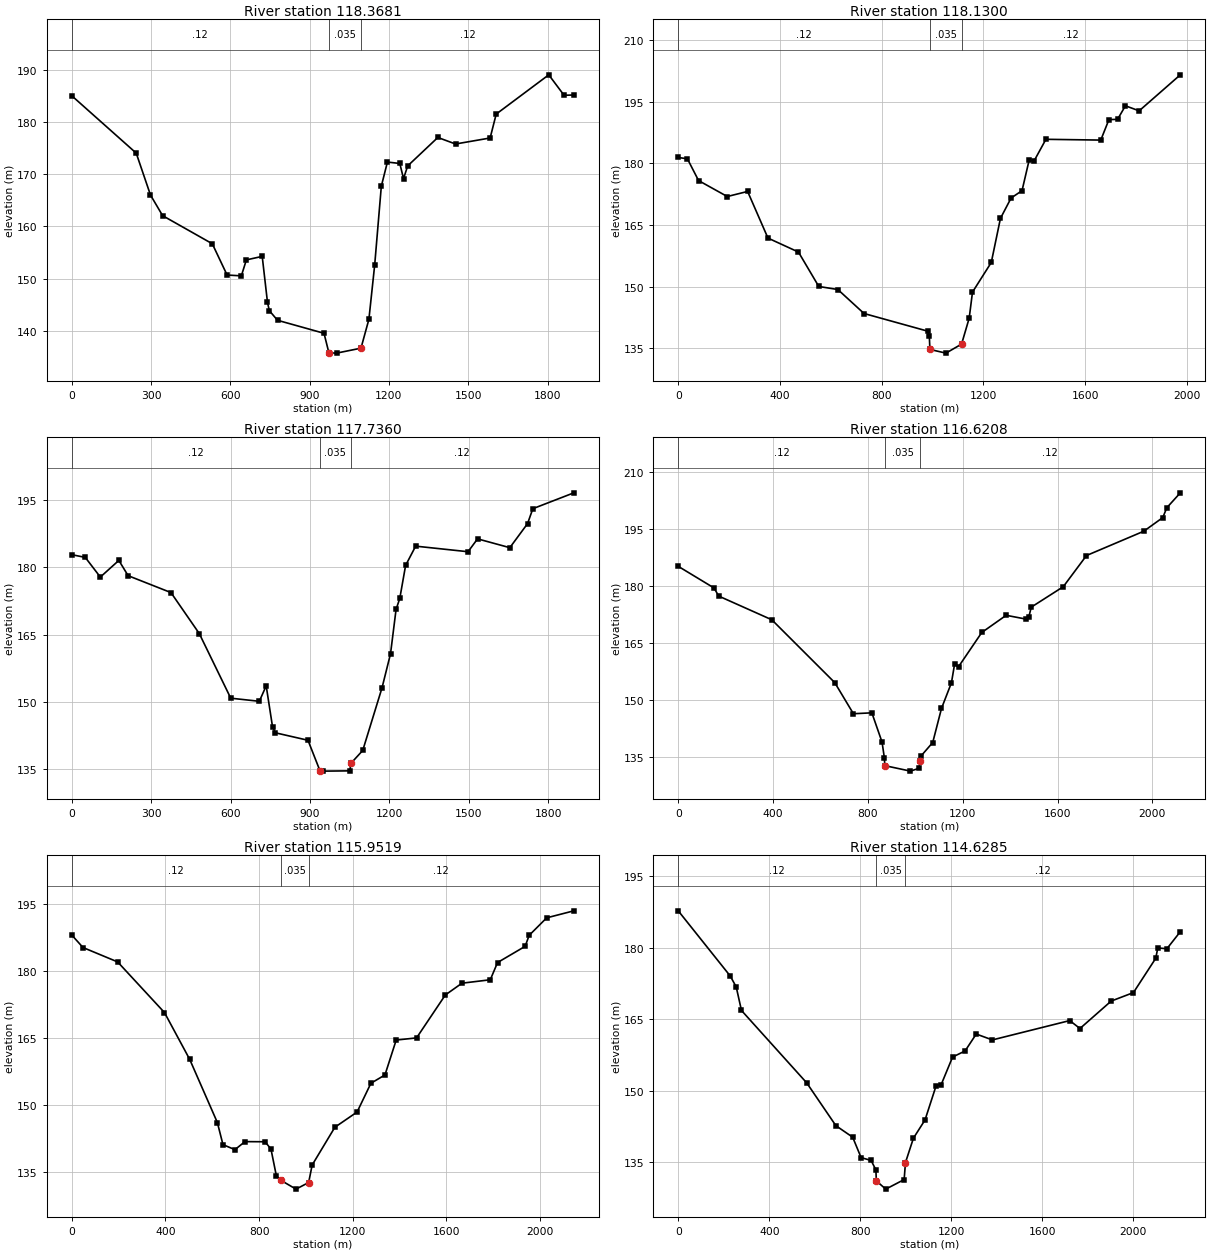
Type RM Length L Ch R = 1 ,118.3681,240.68,238.12,238.92
XS GIS Cut Line= 3
     537788.0069     5403307.416      537741.781    5402604.3679
     537436.5626    5401448.9923
#Sta/Elev= 30
       0  185.03  243.85  174.04  297.82  166.01  343.79  162.06  531.67  156.68
  587.64  150.69   641.6  150.53  660.59  153.59  720.55  154.26  740.53  145.43
  747.53  143.86   778.5  142.02  954.36  139.53  972.88 135.7771001.852 135.729
 1094.25  136.68 1124.22  142.22  1146.2  152.68 1171.18   167.7 1194.17  172.33
 1241.13  172.06 1255.12  169.16  1271.1   171.6 1385.01  177.04 1451.96  175.79
 1582.85  176.94 1605.83  181.52 1804.67  189.04 1862.62  185.12 1899.59  185.18
#Mann= 3 , 0 , 0
       0     .12       0  972.88    .035       0 1094.25     .12       0
Bank Sta=972.88,1094.25
XS Rating Curve= 0 ,0
Exp/Cntr=0.3,0.1

Type RM Length L Ch R = 1 ,118.1300,354.68,394.02,459.66
BEGIN DESCRIPTION:
E34 (SEM 2016)
END DESCRIPTION:
XS GIS Cut Line= 4
     537913.4622    5403278.5398     537915.5012    5402317.9797
     537848.4943     5402102.515     537965.5614    5401322.8757
#Sta/Elev= 30
       0  181.46   35.98  181.14   79.96  175.83  192.91  171.94  272.88  173.18
  352.84  161.81  472.79   158.4  552.75  150.01  627.71  149.27  730.67  143.42
  982.03   139.1  987.52  137.83 989.738 134.6621052.836 133.761 1114.31  135.96
 1144.27  142.29 1157.24  148.64 1231.16  155.87 1267.13   166.6  1309.1  171.58
 1352.06  173.37 1380.04  180.82 1399.03  180.56 1445.99  185.89 1661.81   185.7
 1693.79  190.69 1727.76  190.76 1758.73  194.06 1812.69  192.83 1974.56  201.61
#Mann= 3 , 0 , 0
       0     .12       0 989.738    .035       0 1114.31     .12       0
Bank Sta=989.738,1114.31
XS Rating Curve= 0 ,0
Exp/Cntr=0.3,0.1

Type RM Length L Ch R = 1 ,117.7360,1127.18,1115.18,1111.76
XS GIS Cut Line= 3
     538024.0447    5403318.0837     538125.7692    5402649.1274
      538617.848    5401532.2877
#Sta/Elev= 30
       0  182.78   50.97  182.18  107.94   177.8  177.91  181.51  212.89  178.11
   374.8  174.35  481.75  165.24  600.68  150.86  708.63  150.17  734.62  153.61
  758.61  144.48   769.6  143.16  892.55   141.5 937.786 134.721 948.293 134.637
 1050.55 134.697 1054.48  136.35 1099.46  139.24 1172.42   153.2 1204.41  160.75
  1225.4  170.62 1239.39  173.05 1261.38  180.39 1299.36  184.68 1497.27  183.44
 1533.25   186.3 1655.19  184.34 1722.16  189.69 1742.15  193.01 1897.08  196.54
#Mann= 3 , 0 , 0
       0     .12       0 937.786    .035       0 1054.48     .12       0
Bank Sta=937.786,1054.48
XS Rating Curve= 0 ,0
Exp/Cntr=0.3,0.1

Type RM Length L Ch R = 1 ,116.6208,638.24,668.89,689.51
BEGIN DESCRIPTION:
E33 (SEM 2016)
END DESCRIPTION:
XS GIS Cut Line= 5
      538755.331    5403644.5839      539021.716    5403215.8555
     539201.5247    5403011.6316       539278.44    5402762.5032
     539866.5513     5401856.146
#Sta/Elev= 30
       0  185.19  150.92  179.49  170.91  177.35   394.8  171.11  660.24  154.56
  738.98  146.36  816.81   146.6  859.77  138.89  869.76  134.67 871.295 132.691
 979.709 131.2431015.152 131.984  1021.6  133.83  1024.6  135.26 1073.56  138.78
 1110.55  147.76 1152.52  154.52 1165.52  159.33 1182.51  158.75 1280.46  167.76
  1383.4  172.29 1465.36  171.31 1479.35  171.96 1489.35  174.44 1624.28  179.82
 1722.22  188.03 1964.09  194.44 2044.05  198.03 2061.05  200.62 2118.02  204.55
#Mann= 3 , 0 , 0
       0     .12       0 871.295    .035       0  1021.6     .12       0
Bank Sta=871.295,1021.6
XS Rating Curve= 0 ,0
Exp/Cntr=0.3,0.1

Type RM Length L Ch R = 1 ,115.9519,1338.41,1323.34,1310.4
XS GIS Cut Line= 2
     539310.9367    5403943.4952     540515.0906    5402168.9735
#Sta/Elev= 30
       0  188.13   47.99  185.33  195.95   182.1  395.91  170.75  503.88  160.23
  621.86  146.08  645.85  141.12  696.84     140  739.83   141.8  825.81  141.77
  850.81  140.13   873.8  134.15  892.34 133.146  957.79 131.146 1011.77 132.626
 1026.77  136.55 1123.75  145.02 1218.72  148.44 1277.71  154.89 1337.69  156.75
 1385.68  164.58 1472.66  165.06 1595.63  174.69 1666.61  177.33 1787.58   178.1
 1818.57  181.96 1936.54   185.6 1953.54  188.06 2028.52  191.99 2144.49  193.56
#Mann= 3 , 0 , 0
       0     .12       0  892.34    .035       0 1011.77     .12       0
Bank Sta=892.34,1011.77
XS Rating Curve= 0 ,0
Exp/Cntr=0.3,0.1

Type RM Length L Ch R = 1 ,114.6285,1781.96,1782.74,1777.07
BEGIN DESCRIPTION:
E32 (SEM 2016)
END DESCRIPTION:
XS GIS Cut Line= 3
     540338.6514    5404582.5478     540896.6122    5403993.0967
     541471.9812    5402722.4448
#Sta/Elev= 30
       0  187.69   228.9  174.02  254.89  171.74  277.88  166.83  564.75  151.66
   692.7  142.71  766.66  140.29  803.65  136.01  847.49  135.43  868.64  133.45
 870.591 131.144 912.063 129.418 992.822 131.422  998.62  134.98 1033.62  140.09
 1084.61  143.91 1133.61  151.11  1155.6   151.3  1205.6  157.07 1260.59  158.35
 1309.59  161.89 1380.58  160.66 1720.54  164.71 1765.54  163.05 1902.52  168.79
 2000.51  170.57  2098.5  177.75  2107.5  179.92  2147.5  179.75 2206.49  183.32
#Mann= 3 , 0 , 0
       0     .12       0 870.591    .035       0  998.62     .12       0
Bank Sta=870.591,998.62
XS Rating Curve= 0 ,0
Exp/Cntr=0.3,0.1

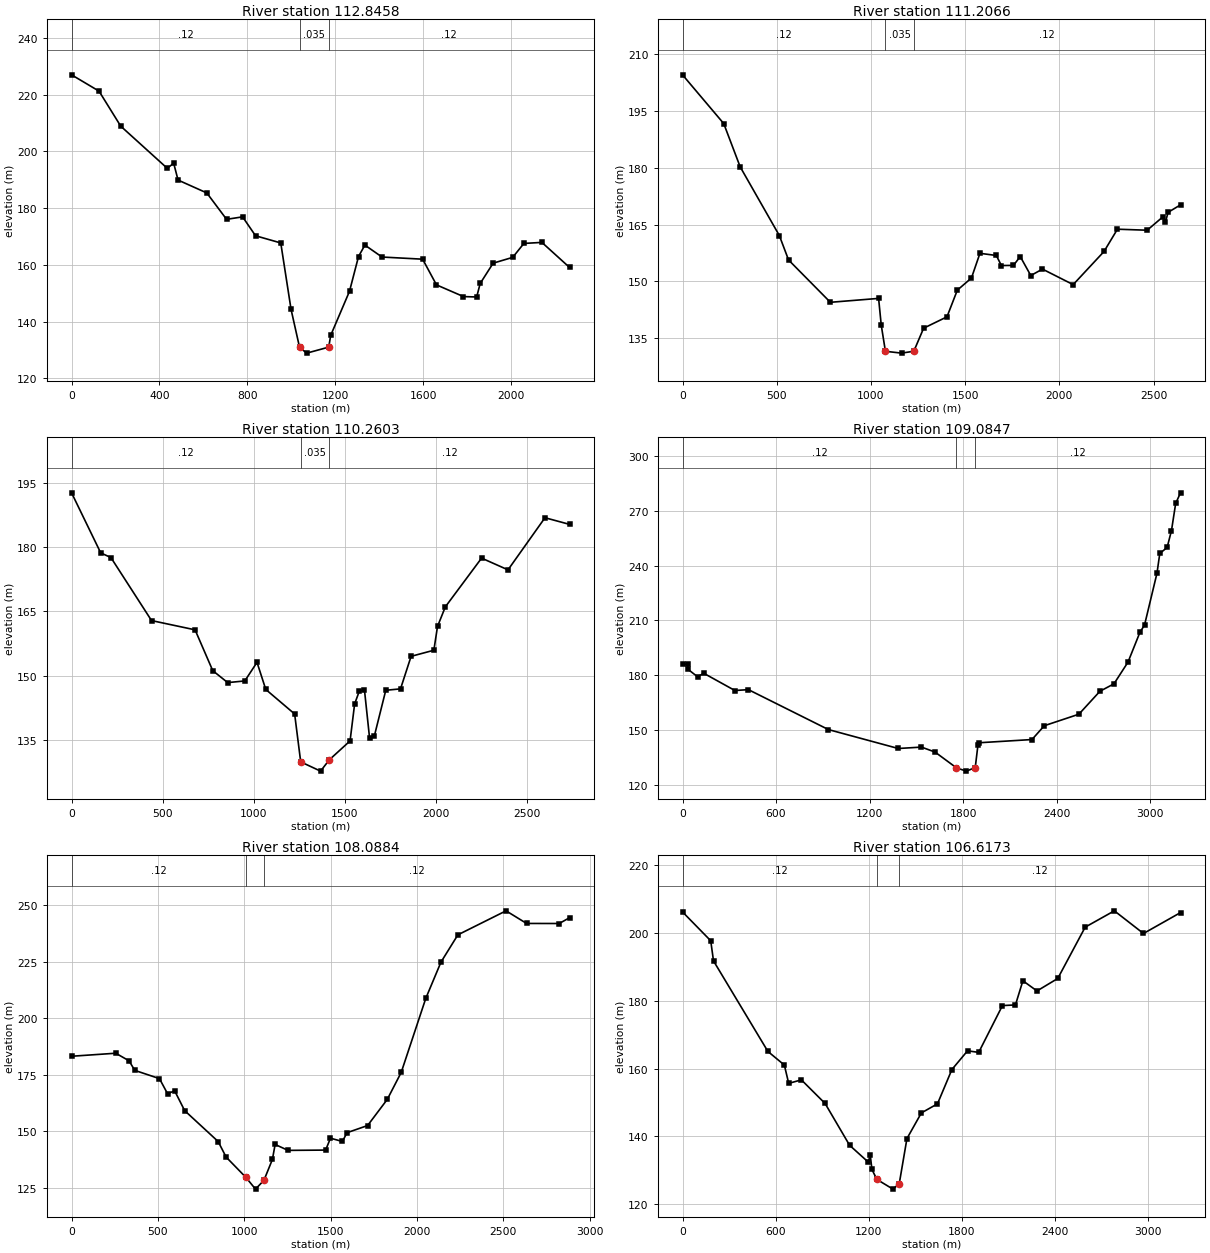
Type RM Length L Ch R = 1 ,112.8458,1633.09,1639.21,1638.27
BEGIN DESCRIPTION:
E31 (SEM 2016)
END DESCRIPTION:
XS GIS Cut Line= 5
     541622.4561    5405960.9932     542154.4075    5405276.2596
     542246.2378     5405066.233     542301.3958    5404912.5037
     542995.9474    5404184.4592
#Sta/Elev= 30
       0  227.04  124.87  221.29  223.76  208.93  435.54  194.06  464.51  195.88
  484.49  189.92  615.35  185.38  705.25  176.07  778.18  176.94  837.11  170.27
   951.8  167.74  998.64  144.311037.426 130.8811069.952 128.8751170.041  130.99
 1178.97  135.12 1264.63   150.7  1305.6  162.95 1334.58  166.98 1412.52  162.77
 1597.38  162.01 1660.33  152.95 1783.24  148.82 1843.19  148.68 1859.18  153.44
 1918.14  160.61 2007.07  162.65 2058.03  167.57 2139.97  167.93 2265.87  159.09
#Mann= 3 , 0 , 0
       0     .12       01037.426    .035       01170.041     .12       0
Bank Sta=1037.426,1170.041
XS Rating Curve= 0 ,0
Exp/Cntr=0.3,0.1

Type RM Length L Ch R = 1 ,111.2066,968.71,946.26,942.59
XS GIS Cut Line= 3
     543122.0861    5406823.4679     543655.0429    5405882.3909
     544202.4767    5404420.4283
#Sta/Elev= 30
       0  204.57   218.9  191.68  305.86  180.27  513.77  162.12  562.75  155.66
  784.65  144.48 1040.54  145.51 1054.53  138.46 1076.66  131.541162.176 131.053
 1227.44  131.55 1279.41  137.64 1403.34  140.64 1458.31  147.69 1533.26   150.9
 1578.24  157.42 1665.19  156.85 1692.17  154.19 1756.14  154.23 1792.12  156.57
 1848.09  151.55 1910.05  153.25 2072.96  149.15 2236.86  157.91 2307.82  163.79
 2465.72  163.52 2550.67  167.12 2562.67  165.66 2576.66  168.25 2642.62  170.22
#Mann= 3 , 0 , 0
       0     .12       0 1076.66    .035       0 1227.44     .12       0
Bank Sta=1076.66,1227.44
XS Rating Curve= 0 ,0
Exp/Cntr=0.3,0.1

Type RM Length L Ch R = 1 ,110.2603,1132.18,1175.64,1233.62
BEGIN DESCRIPTION:
E30 (SEM 2016)
END DESCRIPTION:
XS GIS Cut Line= 6
     543888.3727     5407326.105     544518.0009    5406391.0309
     544549.4521    5406330.1575     544515.7532    5406237.3407
     544514.7692    5406057.0446     545327.0652    5405097.5456
#Sta/Elev= 30
       0  192.64   159.9  178.63  215.87  177.54  438.73  162.84  677.57  160.68
  774.51  151.16  856.46  148.37   950.4  148.76 1017.36   153.1 1065.33  146.78
 1223.74  141.05    1257  129.881365.895  127.72 1414.25  130.37 1527.81  134.77
 1552.79  143.38 1578.78  146.42 1606.76  146.66 1634.74  135.47 1661.72  136.03
 1723.67  146.58 1804.62  146.91 1862.58   154.5 1987.49  155.92 2007.47  161.46
 2050.44  166.04 2249.31  177.41 2394.21  174.67 2597.07  186.83 2731.97  185.28
#Mann= 3 , 0 , 0
       0     .12       0    1257    .035       0 1414.25     .12       0
Bank Sta=1257,1414.25
XS Rating Curve= 0 ,0
Exp/Cntr=0.3,0.1

Type RM Length L Ch R = 1 ,109.0847,1038.86,996.34,970.72
XS GIS Cut Line= 2
      544574.635    5408345.1461     546255.7539    5405628.7522
#Sta/Elev= 30
       0   186.4      33  186.04   34.99  183.34   96.99  179.23  135.98  181.18
  335.95  171.76  422.94  172.22  935.87  150.43  1383.8   140.1 1532.78  140.86
 1619.76  138.16 1757.28 129.534 1820.36 127.744 1877.72 129.674 1894.72  141.79
 1899.72  143.22 2241.65  144.99 2320.63  152.53 2542.58  158.82 2677.55  171.35
 2767.52   175.4  2857.5  187.25 2934.48  203.61 2963.48  207.46 3043.46  235.79
 3061.45  246.57 3108.44  249.85 3136.44  259.06 3163.43  273.93 3194.42  279.68
#Mann= 3 , 0 , 0
       0     .12       0 1757.28    .035       0 1877.72     .12       0
Bank Sta=1757.28,1877.72
XS Rating Curve= 0 ,0
Exp/Cntr=0.3,0.1

Type RM Length L Ch R = 1 ,108.0884,1472.46,1471.09,1474.86
BEGIN DESCRIPTION:
E29 (SEM 2016)
END DESCRIPTION:
XS GIS Cut Line= 5
     546333.6993    5408244.5183     546435.9397    5407234.9086
     546453.8595    5407120.1978      546509.894    5406921.6061
     546966.8596    5405444.2896
#Sta/Elev= 30
       0   183.2  255.94  184.54  332.93  181.19  365.92  176.97  508.89  173.33
  555.88  166.65  596.87  167.95  654.85   159.2  848.81  145.56   894.8  138.71
 1008.77  129.781065.053 124.544    1114  128.45 1162.77  137.63 1178.72  144.26
 1253.48  141.65 1471.15  141.78 1499.14  147.03 1568.11  145.58  1595.1  149.46
 1714.05  152.61    1828  164.15 1908.97  176.11 2050.91  208.73 2138.88  224.75
 2236.84   236.8 2515.74   247.4  2634.7  241.83 2823.63   241.8  2883.6  244.36
#Mann= 3 , 0 , 0
       0     .12       0 1008.77    .035       0    1114     .12       0
Bank Sta=1008.77,1114
XS Rating Curve= 0 ,0
Exp/Cntr=0.3,0.1

Type RM Length L Ch R = 1 ,106.6173,1956.56,1954.42,1973.2
BEGIN DESCRIPTION:
E28 (SEM 2016)
END DESCRIPTION:
XS GIS Cut Line= 2
     547655.8825    5408699.5296     548236.2092     5405539.685
#Sta/Elev= 30
       0  206.15  181.98  197.65  199.98  191.71  550.95  165.03  656.94  161.03
  684.93  155.63  766.92  156.66  919.91   149.7 1077.89  137.39 1198.89   132.4
 1210.88  134.65 1221.88  130.26 1253.88  127.331357.594 124.4641398.168 126.067
 1447.87  139.36 1540.87  146.92 1644.86   149.6 1737.86  159.71 1838.85  165.22
 1910.85  164.76 2063.84  178.55 2147.83  178.74 2195.82  185.86 2286.81  182.86
  2420.8  186.54 2597.78  201.66 2785.76  206.47 2973.74  199.79 3212.72  205.95
#Mann= 3 , 0 , 0
       0     .12       0 1253.88    .035       01398.168     .12       0
Bank Sta=1253.88,1398.168
XS Rating Curve= 0 ,0
Exp/Cntr=0.3,0.1