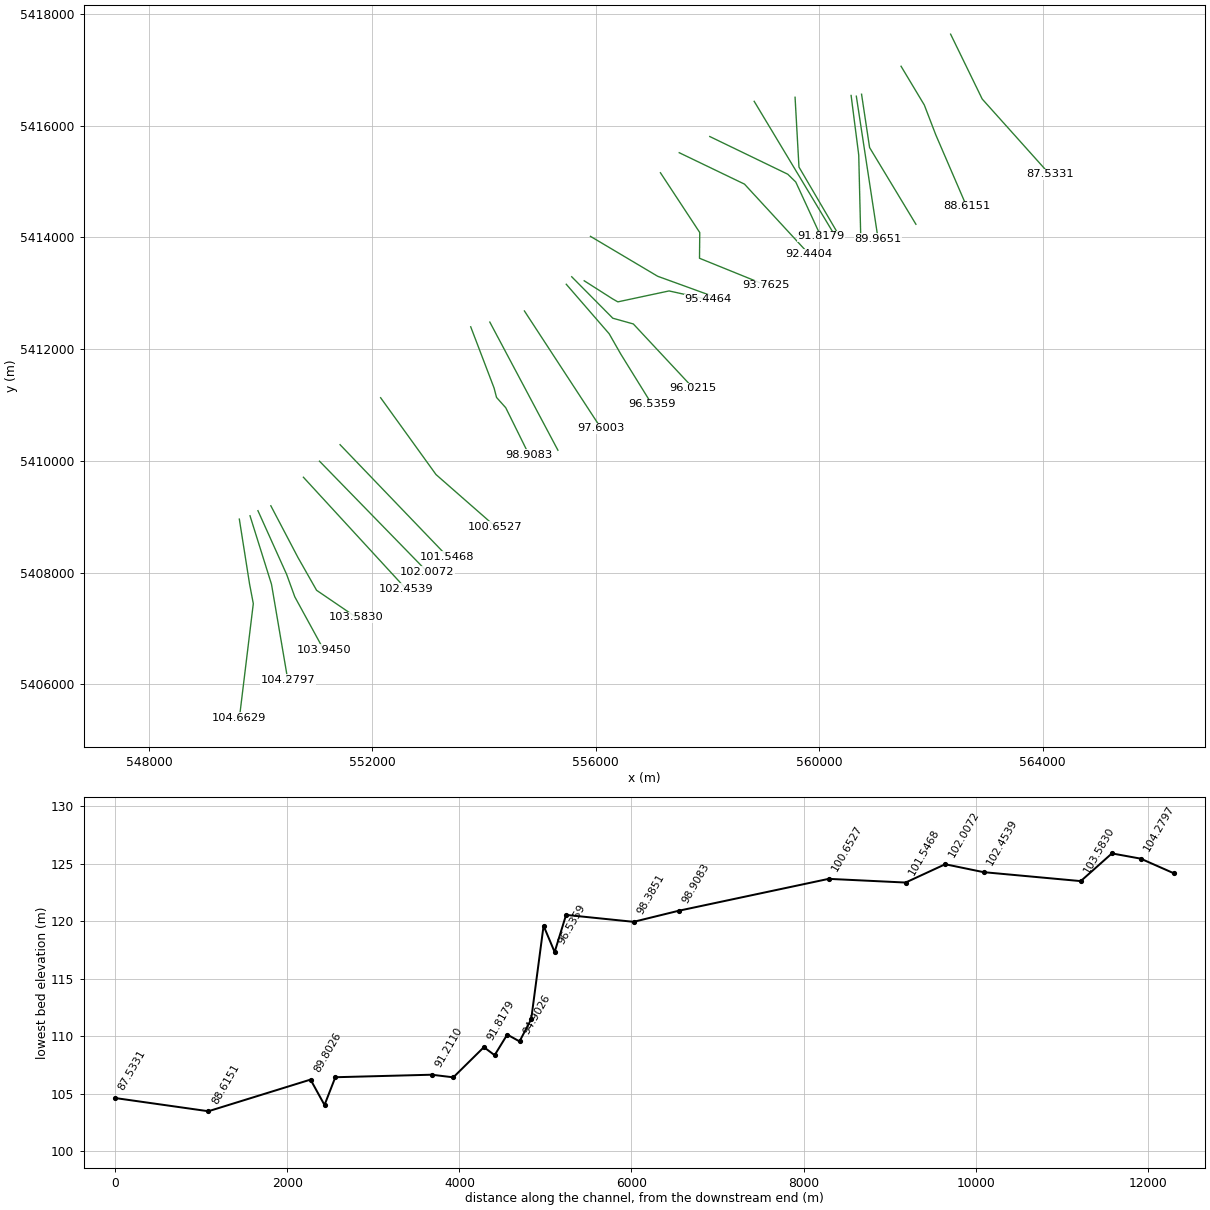
HEC-RAS study Unsteady_RAS.prj: Unsteady_RAS

--- Unsteady_RAS.g01 (geometry) --- (continued)

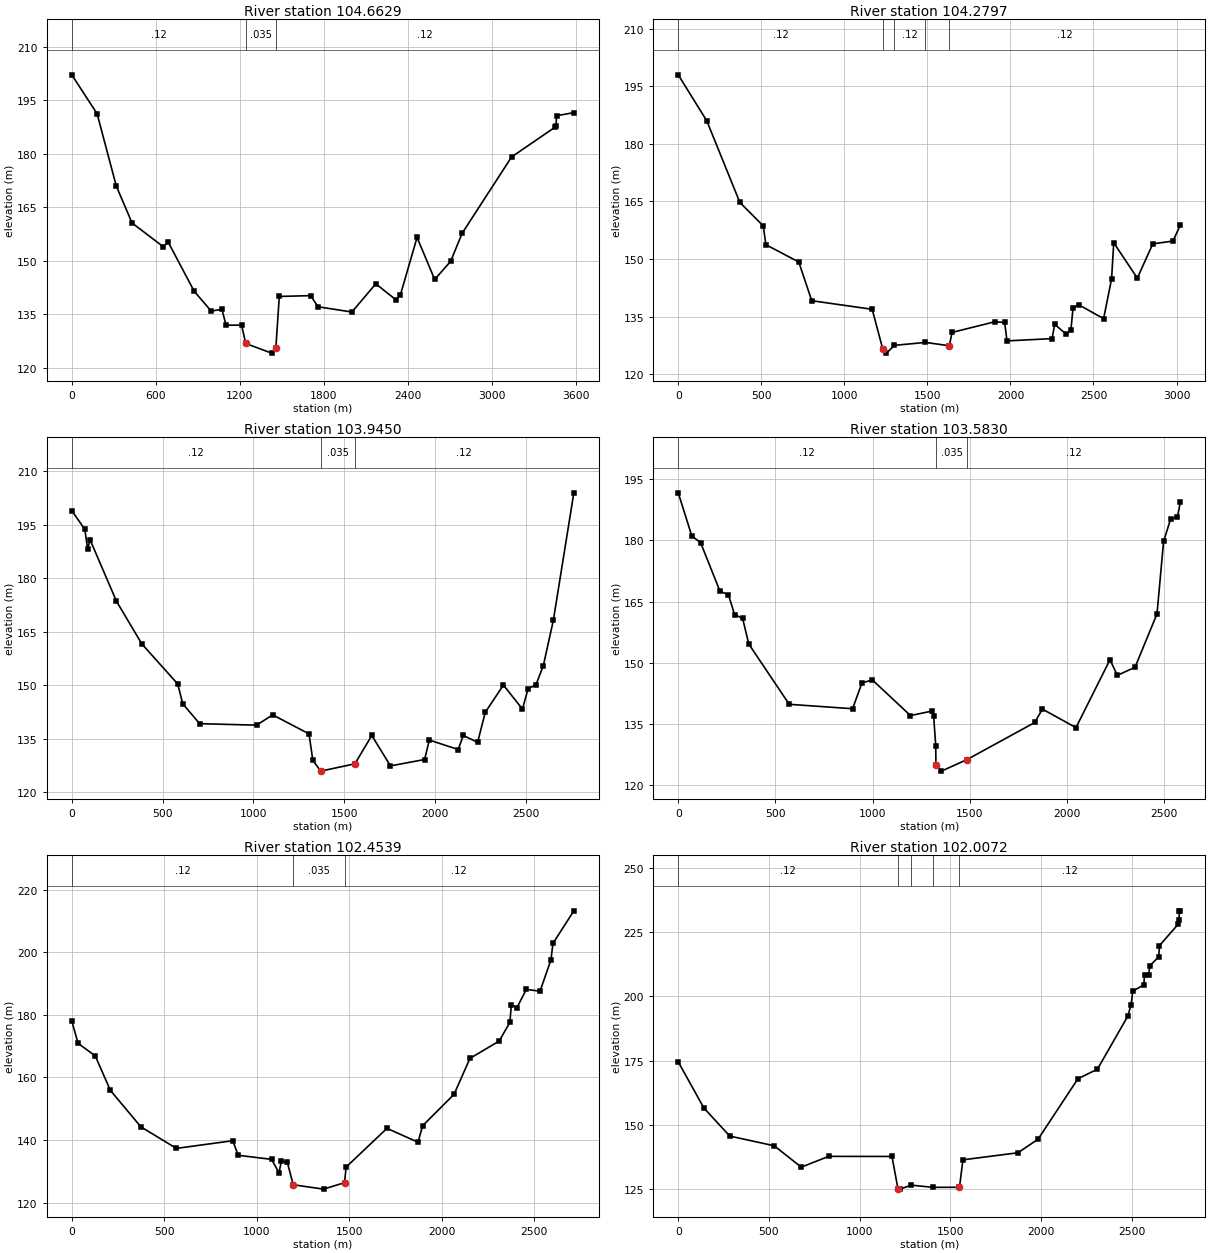
Type RM Length L Ch R = 1 ,104.6629,381.74,383.17,410.51
BEGIN DESCRIPTION:
E27 (SEM 2016)
END DESCRIPTION:
XS GIS Cut Line= 4
     549617.3781    5408956.9241     549800.8356    5407793.9656
     549867.5497    5407443.6106     549619.4807    5405404.6342
#Sta/Elev= 30
       0  202.08   180.9   191.2  317.82  170.99  430.76  160.61  652.63  154.01
  688.61   155.3   874.5  141.52  996.43  135.96 1073.39  136.45 1102.37     132
  1213.3  132.03 1243.27  126.891427.933 124.1871458.398 125.598 1483.03  140.05
 1706.89  140.28 1759.87  137.16 2001.75  135.69 2172.67  143.59  2316.6  139.11
 2347.58  140.37 2467.52  156.57 2593.46  144.81 2707.41  149.87 2789.36  157.71
 3143.19   179.1 3452.04  187.38 3461.04  187.76 3464.04  190.63 3587.97   191.5
#Mann= 3 , 0 , 0
       0     .12       0 1243.27    .035       01458.398     .12       0
Bank Sta=1243.27,1458.398
XS Rating Curve= 0 ,0
Exp/Cntr=0.3,0.1

Type RM Length L Ch R = 1 ,104.2797,330.77,334.7,388.73
XS GIS Cut Line= 3
     549808.6149    5409016.4732      550193.652    5407788.8907
     550485.1929    5406077.4632
#Sta/Elev= 30
       0  198.01  171.94  186.01  370.87  164.75  511.82  158.62  527.82  153.72
  725.75  149.21  803.72  139.12 1167.59  136.88 1230.57  126.621253.718 125.453
 1301.54  127.48 1488.45  128.24 1632.37  127.38 1648.37  130.85 1905.23  133.62
  1965.2  133.45 1979.19  128.64 2251.05  129.24 2266.05  132.98 2337.01  130.33
    2364  131.53 2376.99  137.27 2409.97  138.09 2560.89  134.44 2608.87  144.81
 2621.86  154.24 2763.79     145 2856.74  153.93 2978.68  154.68 3022.65  158.84
#Mann= 5 ,-1 , 0
       0     .12       0 1230.57    .035       0 1301.54     .12       0
 1488.45    .035       0 1632.37     .12       0
Bank Sta=1230.57,1632.37
XS Rating Curve= 0 ,0
Exp/Cntr=0.3,0.1

Type RM Length L Ch R = 1 ,103.9450,347.77,362,388.94
XS GIS Cut Line= 4
     549950.6288    5409107.3847     550464.4224    5407966.8424
     550610.4564    5407565.2158     551130.9313    5406612.8083
#Sta/Elev= 30
       0  198.93      72  193.64      87  188.21  100.99  190.72  245.99  173.52
  385.98  161.54  582.97  150.35  610.97  144.77  703.96  139.21 1016.94  138.79
 1105.93  141.68 1305.84  136.35 1326.81  128.96 1370.34 125.909 1558.46  127.96
 1651.32   135.9 1754.23  127.38 1942.12  129.16  1968.1  134.62 2127.01  131.96
 2154.99   135.9 2233.94  133.99 2275.92  142.37 2375.86  150.03 2480.79   143.3
 2511.77  149.02 2554.75  150.07 2595.72  155.48 2650.69  168.15 2763.62   203.9
#Mann= 3 , 0 , 0
       0     .12       0 1370.34    .035       0 1558.46     .12       0
Bank Sta=1370.34,1558.46
XS Rating Curve= 0 ,0
Exp/Cntr=0.3,0.1

Type RM Length L Ch R = 1 ,103.5830,1112.46,1129.1,1151.32
BEGIN DESCRIPTION:
Noel Pauls Brook - E26 (SEM 2016)
END DESCRIPTION:
XS GIS Cut Line= 4
     550181.3612    5409195.5247     550667.0741    5408269.4761
     551000.5337    5407682.3974     551712.5564    5407197.5705
#Sta/Elev= 30
       0  191.64   69.98  181.05  114.97  179.45  214.94  167.51  257.93  166.72
  289.92  161.79   330.9  160.94   362.9  154.62  570.84  139.86  896.74  138.78
  944.73  145.09  998.71  145.82 1194.52   137.1 1306.38  138.22 1313.37  137.11
 1324.36  129.761325.299 125.0951353.652   123.5 1485.16  126.33  1833.8  135.41
 1872.77  138.69 2045.65  134.15 2220.53  150.77  2258.5  146.95 2349.43  148.93
 2462.35     162 2496.33  179.76  2532.3  185.21 2567.28  185.64 2582.27  189.37
#Mann= 3 , 0 , 0
       0     .12       01325.299    .035       0 1485.16     .12       0
Bank Sta=1325.299,1485.16
XS Rating Curve= 0 ,0
Exp/Cntr=0.3,0.1

Type RM Length L Ch R = 1 ,102.4539,446.11,446.73,454.81
XS GIS Cut Line= 2
     550764.5705    5409706.2411     552602.3674    5407707.2283
#Sta/Elev= 30
       0  178.05   33.99   170.9  126.97  166.86  208.96  155.83  373.92  144.18
  565.88   137.3  870.82  139.75  899.82   135.1 1080.78  133.79 1120.77  129.49
 1133.77  133.27 1165.76  132.85 1197.64  125.681361.442 124.278 1475.18 126.338
 1483.68  131.32 1704.63  143.71 1872.59  139.27 1897.59  144.55 2067.55  154.58
 2153.53  166.08 2311.49   171.6 2369.48  177.59 2377.48  183.19 2407.47  182.26
 2458.46  188.14 2532.44  187.54 2591.43  197.55 2602.43  202.83  2715.4  213.24
#Mann= 3 , 0 , 0
       0     .12       0 1197.64    .035       0 1475.18     .12       0
Bank Sta=1197.64,1475.18
XS Rating Curve= 0 ,0
Exp/Cntr=0.3,0.1

Type RM Length L Ch R = 1 ,102.0072,467.27,460.36,459.14
XS GIS Cut Line= 2
     551052.8398    5409993.6098     552983.5166    5408012.7473
#Sta/Elev= 30
       0  174.54  140.95  156.59  283.91  145.62  528.83  141.85  677.78  133.52
  828.72  137.72 1177.61  137.69  1210.6 125.0651221.752 124.967 1283.58  126.53
 1402.54  125.66 1549.49  125.68 1568.49  136.38 1871.39  139.12 1982.36   144.4
  2202.3  167.97 2309.27  171.65 2476.23  192.24 2495.22  196.79 2504.22  202.05
 2565.21  204.52  2569.2  208.25  2592.2  208.25  2597.2  211.88 2647.18   215.4
 2651.18  219.78 2753.16  228.02 2759.16  229.92 2761.15  233.33 2766.15  233.33
#Mann= 5 ,-1 , 0
       0     .12       0  1210.6    .035       0 1283.58     .12       0
 1402.54    .035       0 1549.49     .12       0
Bank Sta=1210.6,1549.49
XS Rating Curve= 0 ,0
Exp/Cntr=0.3,0.1

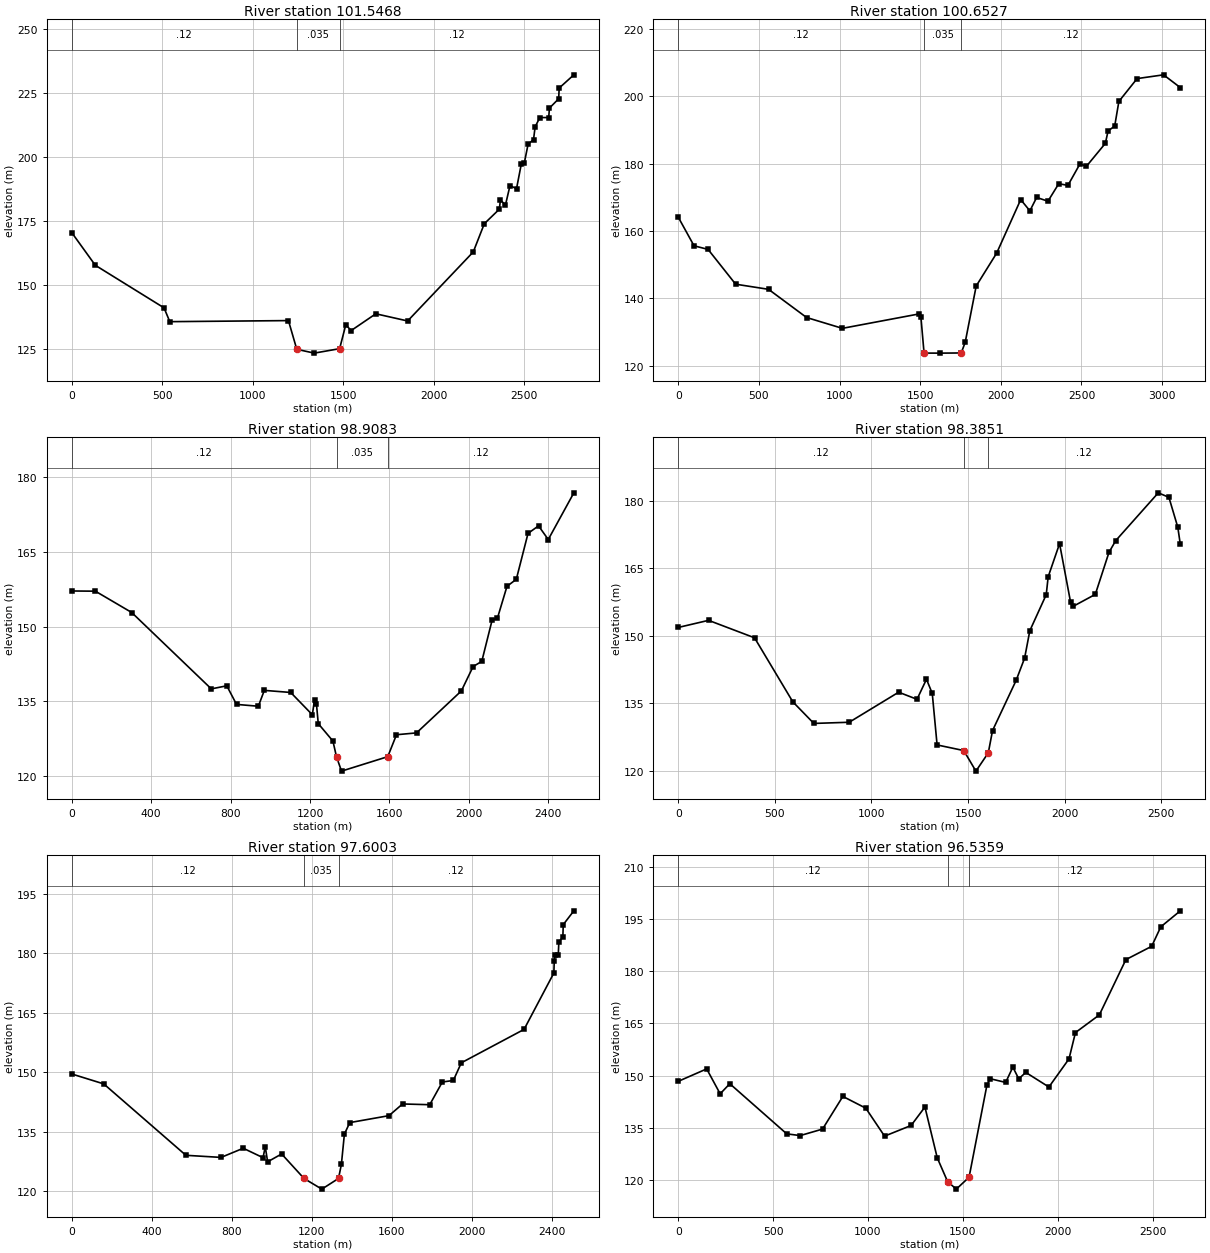
Type RM Length L Ch R = 1 ,101.5468,909.18,894.07,898.57
BEGIN DESCRIPTION:
E25 (SEM 2016)
END DESCRIPTION:
XS GIS Cut Line= 2
     551420.3214    5410289.3998     553342.8148    5408287.2667
#Sta/Elev= 30
       0   170.5  129.99  157.74  509.94  141.09  541.94  135.68 1197.87   136.1
 1243.86  124.881340.551 123.375 1480.84  125.12 1514.84  134.44 1544.83  132.21
 1680.82  138.76  1856.8  135.95 2219.76  162.96 2280.75  173.99 2363.75  179.66
 2369.74  183.26 2397.74  181.32 2422.74  188.91 2458.74  187.66 2484.74  197.17
 2501.73  197.68 2522.73  205.09 2552.73  206.86 2561.73  211.89 2587.73   215.5
 2636.72   215.5 2640.72   219.2 2691.72  222.84 2694.71  227.05  2775.7  232.21
#Mann= 3 , 0 , 0
       0     .12       0 1243.86    .035       0 1480.84     .12       0
Bank Sta=1243.86,1480.84
XS Rating Curve= 0 ,0
Exp/Cntr=0.3,0.1

Type RM Length L Ch R = 1 ,100.6527,1731.24,1744.38,1770.48
XS GIS Cut Line= 3
     552146.8385    5411129.6135     553138.4007    5409754.3654
     554204.5836      5408820.28
#Sta/Elev= 30
       0  164.11   97.97  155.59  184.94  154.52  355.88  144.18  559.81  142.66
  795.73  134.28 1017.65  131.06  1491.5  135.33  1504.5  134.461524.111 123.708
1625.879 123.6961754.732 123.746  1779.4  126.96 1847.38  143.65 1974.33  153.42
 2123.27  169.32 2180.25  165.98 2222.23  169.96  2292.2  168.84 2359.18  174.04
 2416.15  173.55 2491.12  179.97 2530.11  179.18 2648.06  186.03 2665.05  189.71
 2706.03  191.18 2732.02   198.5 2844.98  205.28 3008.91   206.4 3112.87  202.61
#Mann= 3 , 0 , 0
       0     .12       01524.111    .035       01754.732     .12       0
Bank Sta=1524.111,1754.732
XS Rating Curve= 0 ,0
Exp/Cntr=0.3,0.1

Type RM Length L Ch R = 1 ,98.9083 ,596.7,523.2,496.56
BEGIN DESCRIPTION:
DS of 02YO011 ER below NP Brook - E24 (SEM 2016)
END DESCRIPTION:
XS GIS Cut Line= 5
     553759.6838    5412399.4191     554178.1701    5411302.7808
     554221.8514    5411134.8619     554386.8006    5410950.5432
     554801.0484    5410113.1202
#Sta/Elev= 30
       0  157.15  118.98  157.11  301.94  152.82  702.86  137.46  780.85  138.08
  829.84  134.34  939.82  133.97  969.81  137.16 1102.79  136.74 1211.67  132.26
 1222.64   135.2 1232.61  134.36 1241.58  130.47 1315.37  126.97 1333.56  123.78
1358.799  120.92 1591.63  123.83 1635.59  128.24 1736.51  128.61 1962.34  137.05
 2021.29  141.94 2065.26     143 2117.22  151.29  2144.2   151.7 2192.17  158.09
 2239.13   159.5 2298.09  168.73 2351.05  170.25 2400.02   167.5 2528.92  176.89
#Mann= 3 , 0 , 0
       0     .12       0 1333.56    .035       0 1591.63     .12       0
Bank Sta=1333.56,1591.63
XS Rating Curve= 0 ,0
Exp/Cntr=0.3,0.1

Type RM Length L Ch R = 1 ,98.3851 ,801.76,784.8,779.52
XS GIS Cut Line= 2
     554101.4056    5412484.3301     555320.9233    5410189.3732
#Sta/Elev= 30
       0  151.89  156.99  153.47  394.98  149.59  592.97  135.37  701.96  130.56
  884.95  130.82 1140.94   137.5 1235.93  135.92 1284.93  140.38 1314.92  137.22
 1339.92  125.78 1478.01 124.529  1540.8 119.959  1604.9 124.019  1626.9  128.97
 1748.89  140.11 1792.89  145.07 1819.88  151.16 1904.88  159.18 1914.88  163.15
 1973.87  170.52 2030.87   157.5 2045.87  156.62 2158.87  159.24 2229.87  168.61
 2264.87   171.2 2484.87  181.81 2539.87  180.81 2585.87  174.16 2598.87  170.36
#Mann= 3 , 0 , 0
       0     .12       0 1478.01    .035       0  1604.9     .12       0
Bank Sta=1478.01,1604.9
XS Rating Curve= 0 ,0
Exp/Cntr=0.3,0.1

Type RM Length L Ch R = 1 ,97.6003 ,137.83,133.04,131.81
XS GIS Cut Line= 2
     554720.9829    5412682.9408     556094.5787     5410580.473
#Sta/Elev= 30
       0   149.6  159.96   147.1  570.86  129.09  746.82  128.56  857.79  130.87
  956.77  128.49  967.76  131.26  979.76  127.45 1049.74  129.43 1161.75  123.25
 1250.82  120.56 1334.24  123.25 1348.67  126.82 1363.67  134.44 1390.66  137.34
 1586.62  139.09  1654.6  142.04 1790.57  141.85 1853.56  147.58 1908.54  147.96
 1948.53  152.42 2262.46  160.85 2411.42  175.07 2413.42  178.16 2417.42  179.54
 2433.42  179.54 2436.42  182.92 2456.41  184.14 2458.41  187.27  2511.4  190.75
#Mann= 3 , 0 , 0
       0     .12       0 1161.75    .035       0 1334.24     .12       0
Bank Sta=1161.75,1334.24
XS Rating Curve= 0 ,0
Exp/Cntr=0.3,0.1

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
Type RM Length L Ch R = 1 ,96.5359 ,121.35,128.61,131.24
BEGIN DESCRIPTION:
E23 (SEM 2016)
END DESCRIPTION:
XS GIS Cut Line= 4
     555469.8749    5413161.3214     556238.4071    5412274.6128
     556446.8978    5411909.6474     557000.9595    5411014.8591
#Sta/Elev= 30
       0  148.35  149.92  151.93  220.89  144.76  271.86  147.66  571.71  133.24
  642.68  132.74  760.62  134.61  867.57  144.01  988.51  140.63 1087.46  132.58
 1227.33  135.65 1300.22  140.96 1365.11  126.34 1419.72 119.4921465.579 117.331
 1532.85  120.76 1626.73   147.2 1643.72  149.11 1725.68  148.04 1763.66  152.44
 1794.64  149.07 1831.62  150.92 1953.55  146.72  2059.5  154.81 2093.48  162.38
 2219.41  167.47 2359.34  183.38 2495.27  187.21 2543.25  192.81 2646.19  197.42
#Mann= 3 , 0 , 0
       0     .12       0 1419.72    .035       0 1532.85     .12       0
Bank Sta=1419.72,1532.85
XS Rating Curve= 0 ,0
Exp/Cntr=0.3,0.1

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
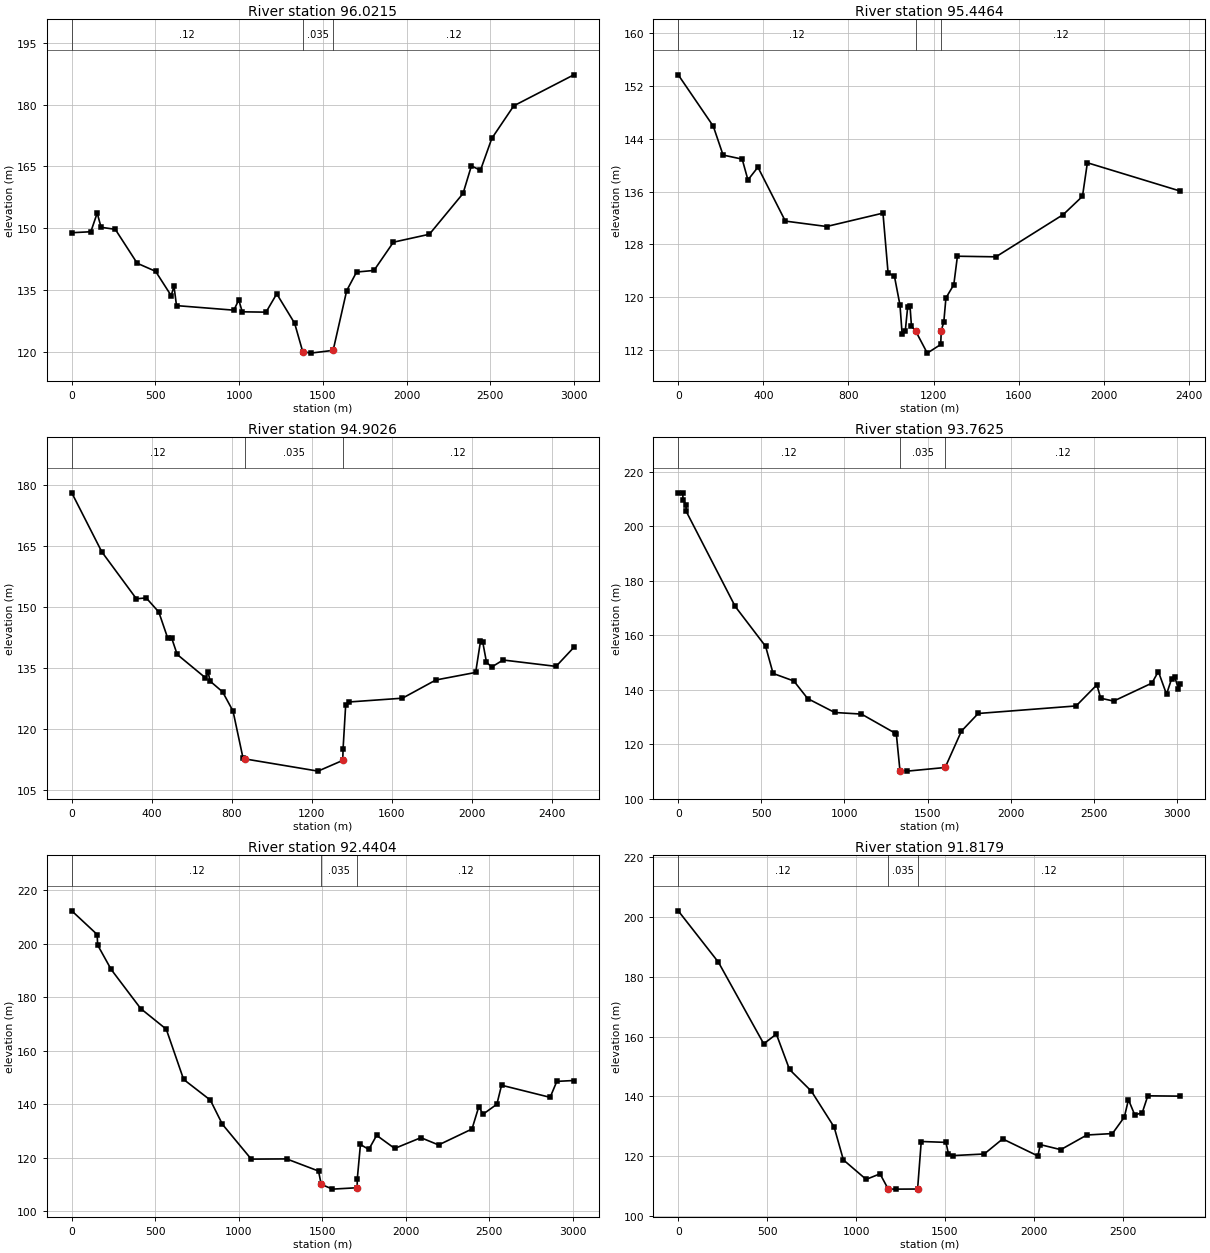
Type RM Length L Ch R = 1 ,96.0215 ,123.43,143.77,169.66
XS GIS Cut Line= 4
     555567.9158    5413295.1012     556303.2225    5412553.2616
      556671.028    5412450.3883     557744.2909    5411300.5327
#Sta/Elev= 30
       0  148.89  113.95  149.13  151.93  153.68  174.92  150.21  259.88  149.72
  390.82  141.47  500.77  139.51  593.72   133.6  610.71  135.86  625.71  131.17
  968.55  130.06  997.53  132.56 1018.52  129.66 1160.49  129.58 1224.48  134.03
 1331.46  126.87 1379.45  120.01 1426.81 119.617 1561.44  120.29 1642.44  134.82
 1701.44  139.33 1805.44  139.72 1921.44  146.59 2136.43  148.52 2337.43  158.43
 2387.43  165.14 2441.43  164.07 2509.43  171.83 2640.43  179.74 2999.43  187.28
#Mann= 3 , 0 , 0
       0     .12       0 1379.45    .035       0 1561.44     .12       0
Bank Sta=1379.45,1561.44
XS Rating Curve= 0 ,0
Exp/Cntr=0.3,0.1

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
Type RM Length L Ch R = 1 ,95.4464 ,190.23,135.95,113.68
BEGIN DESCRIPTION:
Red Indian Falls
END DESCRIPTION:
XS GIS Cut Line= 5
      555791.468    5413223.1929     556299.3981    5412899.7288
     556393.2222    5412845.9387      557310.269    5413041.6158
     558005.2837    5412888.2945
#Sta/Elev= 30
       0  153.71  164.78  145.91  210.71  141.54  300.59  140.92  327.56  137.76
  374.49   139.7  503.32  131.52  697.43   130.7  962.25  132.73  986.24  123.67
 1016.23  123.14 1042.23  118.77 1052.22  114.44 1067.22  114.89 1078.21  118.44
 1089.21  118.71 1096.21  115.57  1115.2  114.881170.494  111.491233.718   112.8
 1236.17  114.92 1248.17  116.21 1258.16  119.86 1295.15  121.87 1312.15  126.19
 1493.09   126.1 1809.98  132.52 1899.95  135.28 1922.94  140.37 2359.77  136.07
#Mann= 3 , 0 , 0
       0     .12       0  1115.2    .035       0 1236.17     .12       0
Bank Sta=1115.2,1236.17
XS Rating Curve= 0 ,0
Exp/Cntr=0.3,0.1

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
Type RM Length L Ch R = 1 ,94.9026 ,168.99,142.51,118.79
BEGIN DESCRIPTION:
E22 (SEM 2016)
END DESCRIPTION:
XS GIS Cut Line= 3
     555903.3233    5414018.7943     557105.7759    5413304.4824
     558149.2571    5412925.5934
#Sta/Elev= 30
       0  178.08  149.96  163.56  322.91  151.99   371.9  152.21  434.88  148.73
  478.87  142.38  499.86  142.22  526.86  138.28  667.82  132.54  681.82  133.87
  690.82  131.73   753.8  129.07  805.79  124.34  855.78  112.75  863.89  112.58
 1230.48 109.5611354.122 112.205 1355.65  115.04 1368.64  125.83 1386.64  126.59
 1652.44  127.52  1819.3     132 2018.15  133.86 2042.13  141.48 2053.12  141.45
  2072.1  136.41 2098.09  135.18 2155.04  136.92 2419.85  135.35 2508.78  140.03
#Mann= 3 , 0 , 0
       0     .12       0  863.89    .035       01354.122     .12       0
Bank Sta=863.89,1354.122
XS Rating Curve= 0 ,0
Exp/Cntr=0.3,0.1

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
Type RM Length L Ch R = 1 ,93.7625 ,137.08,146.91,159.07
BEGIN DESCRIPTION:
E21 (SEM 2016)
END DESCRIPTION:
XS GIS Cut Line= 4
     557156.0479     5415157.159     557860.0022    5414086.8477
     557855.4735     5413626.493     559040.6031    5413146.0574
#Sta/Elev= 30
       0  212.33   26.98  212.33   28.98  209.79   46.97  207.92   47.96  205.52
  342.75  170.61  525.62  155.97  570.58  146.02  695.49  143.24  778.43   136.8
  941.31  131.68 1102.19   131.1 1305.02  124.08 1312.01  123.741333.947 110.233
1378.023 110.155 1605.62  111.49 1703.49  124.84 1804.43  131.32 2393.32  134.09
 2518.29  141.84 2541.28  136.92 2619.27  135.87 2849.21  142.47 2888.21  146.72
 2937.19  138.38 2968.19  144.12 2986.18  144.82 3009.18  140.29 3020.18  142.23
#Mann= 3 , 0 , 0
       0     .12       01333.947    .035       0 1605.62     .12       0
Bank Sta=1333.947,1605.62
XS Rating Curve= 0 ,0
Exp/Cntr=0.3,0.1

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
Type RM Length L Ch R = 1 ,92.4404 ,117.01,124.5,132.94
BEGIN DESCRIPTION:
E20 (SEM 2016)
END DESCRIPTION:
XS GIS Cut Line= 3
      557492.581    5415516.0646     558660.5478    5414953.8789
      559819.038    5413697.0079
#Sta/Elev= 30
       0   212.4  151.91  203.55  154.91  199.61  235.86  190.48  412.75  175.85
  565.66  168.15   669.6  149.37   829.5  141.64  901.46  132.62 1074.36  119.58
 1286.23  119.66 1477.16  115.12 1493.15  110.151560.567 108.361  1708.3 108.879
 1709.07  112.14 1728.06  125.05 1778.04   123.2 1825.02  128.47 1932.98  123.57
 2089.92  127.59 2195.87  124.88 2395.77  130.84 2436.75  139.22 2461.74  136.35
  2544.7   140.1 2572.69   147.2 2863.56  142.67 2903.54  148.64 3005.49  148.97
#Mann= 3 , 0 , 0
       0     .12       0 1493.15    .035       0  1708.3     .12       0
Bank Sta=1493.15,1708.3
XS Rating Curve= 0 ,0
Exp/Cntr=0.3,0.1

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
Type RM Length L Ch R = 1 ,91.8179 ,420.96,355.52,291.8
XS GIS Cut Line= 4
     558039.5376    5415805.7839     559435.0019     5415131.463
     559579.0629    5414991.1417      560028.681    5414016.7805
#Sta/Elev= 30
       0  201.97  225.98  184.82  480.95  157.57  551.95  160.82  625.94     149
  748.93  141.75  876.92  129.78  928.91  118.82  1056.9  112.31 1134.89  114.16
 1181.09 109.0851224.629  109.06 1346.32 109.092 1366.86  124.96 1505.84  124.67
 1519.84  120.84 1543.84  120.25 1721.08  120.79 1824.89  125.82 2022.72  120.14
 2036.71  123.91 2151.62  122.24 2298.49  127.13 2442.37  127.61 2509.31  133.13
 2532.29  138.93 2568.26  133.77 2610.23  134.62  2641.2  140.21 2824.05   140.1
#Mann= 3 , 0 , 0
       0     .12       0 1181.09    .035       0 1346.32     .12       0
Bank Sta=1181.09,1346.32
XS Rating Curve= 0 ,0
Exp/Cntr=0.3,0.1

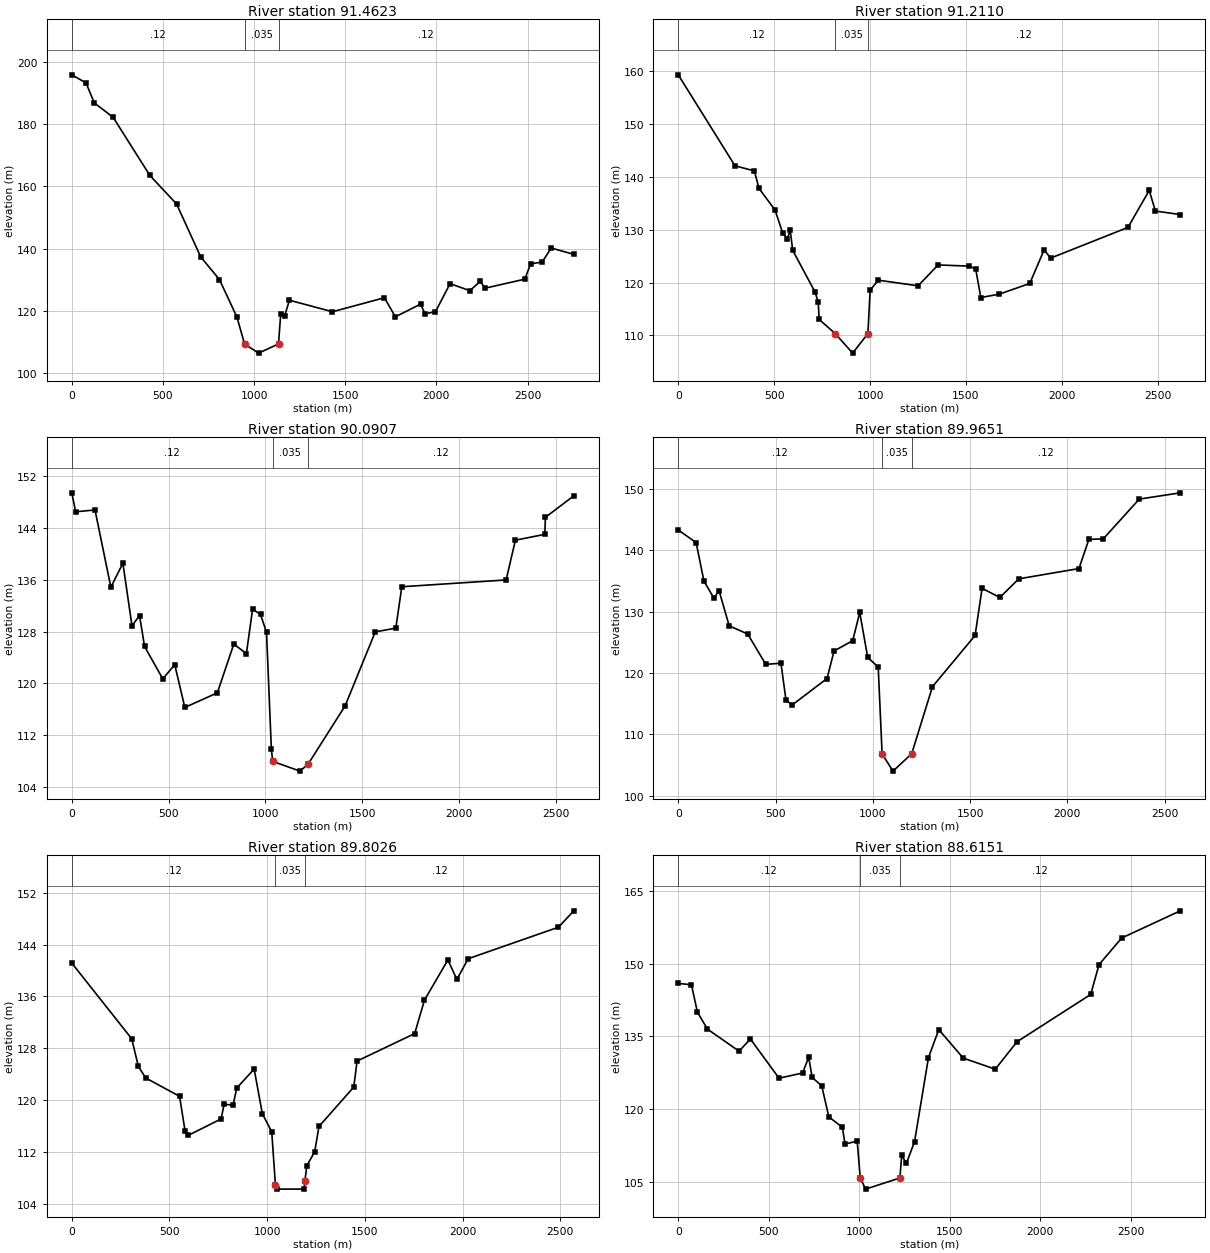
Type RM Length L Ch R = 1 ,91.4623 ,303.52,251.36,212.34
BEGIN DESCRIPTION:
E19 (SEM 2016)
END DESCRIPTION:
XS GIS Cut Line= 2
     558834.3882    5416435.7852     560253.7216    5414075.7224
#Sta/Elev= 30
       0  195.75      78  193.16     124  186.72     227  182.11     428  163.49
     575  154.29  706.99  137.34  809.99  130.05  905.99  117.99  947.99  109.34
1024.777 106.436 1133.99  109.38 1145.99  118.89 1167.99  118.47 1193.99  123.41
 1429.99  119.72 1714.98  124.21 1774.98   118.1 1912.98  122.15 1937.98  119.07
 1994.98  119.74 2074.98  128.72 2183.98  126.48 2239.98  129.44 2267.98  127.29
 2484.98  130.17 2516.98  135.09 2579.98  135.66 2629.98  140.17 2753.98  138.13
#Mann= 3 , 0 , 0
       0     .12       0  947.99    .035       0 1133.99     .12       0
Bank Sta=947.99,1133.99
XS Rating Curve= 0 ,0
Exp/Cntr=0.3,0.1

Type RM Length L Ch R = 1 ,91.2110 ,1131.72,1120.2,1130.16
XS GIS Cut Line= 3
     559566.2041    5416508.3709     559635.9532    5415259.6026
     560326.9877     5414080.171
#Sta/Elev= 30
       0  159.23  295.93  142.05  396.91  141.08   420.9  137.79  504.88  133.68
  543.88  129.42  567.87  128.24  583.87  129.83  596.86  126.08  712.84  118.23
  729.83  116.33  734.83  113.02  818.48 110.354  909.35 106.664  988.78 110.354
 1000.77  118.55 1042.76  120.44 1250.72  119.38 1354.72  123.32 1515.72   123.1
 1550.72  122.58 1577.72  117.17 1672.72  117.79 1832.72  119.82 1907.72  126.18
 1941.72  124.61 2344.72  130.41 2455.72   137.4 2487.72   133.5 2617.72  132.84
#Mann= 3 , 0 , 0
       0     .12       0  818.48    .035       0  988.78     .12       0
Bank Sta=818.48,988.78
XS Rating Curve= 0 ,0
Exp/Cntr=0.3,0.1

Type RM Length L Ch R = 1 ,90.0907 ,125.2,125.64,135.28
XS GIS Cut Line= 3
     560569.4322    5416541.1423     560705.8655    5415475.0354
     560743.0881    5413957.2947
#Sta/Elev= 30
       0  149.47      20  146.54  119.98  146.82  201.96  134.87  263.95  138.59
  310.94  128.91  349.93  130.49  375.93  125.72  469.91  120.72   531.9  122.89
  583.89  116.29  751.86  118.55  836.84  126.09  901.83  124.61  933.82  131.48
  974.81  130.67  1005.8   127.9  1030.8  109.86  1037.8  107.951178.618 106.445
 1220.71  107.53 1411.61  116.53 1567.53  127.98 1673.48  128.54 1704.46  134.95
 2243.18     136 2291.16  142.15 2443.09  143.05 2446.08  145.68 2593.01  149.01
#Mann= 3 , 0 , 0
       0     .12       0  1037.8    .035       0 1220.71     .12       0
Bank Sta=1037.8,1220.71
XS Rating Curve= 0 ,0
Exp/Cntr=0.3,0.1

Type RM Length L Ch R = 1 ,89.9651 ,130.8,162.48,192.3
BEGIN DESCRIPTION:
E18 (SEM 2016)
END DESCRIPTION:
XS GIS Cut Line= 2
     560662.7215    5416528.0841     561051.8143    5413976.6972
#Sta/Elev= 30
       0  143.32      92  141.26  131.99     135  182.99  132.22  209.99  133.41
  261.99   127.7  356.98  126.37  449.98  121.42  527.98  121.61  553.98  115.58
  585.97  114.81  764.97  119.12  800.97   123.6  896.96  125.29  932.96  129.88
  973.96  122.56 1027.96  120.98 1047.96  106.841103.852 104.029 1199.94  106.85
 1306.93  117.79 1525.91  126.13 1561.91  133.81  1652.9  132.32 1750.89  135.36
 2059.87  137.03 2110.87  141.78 2184.87  141.87 2369.87  148.35 2580.87  149.37
#Mann= 3 , 0 , 0
       0     .12       0 1047.96    .035       0 1199.94     .12       0
Bank Sta=1047.96,1199.94
XS Rating Curve= 0 ,0
Exp/Cntr=0.3,0.1

Type RM Length L Ch R = 1 ,89.8026 ,1217.88,1187.52,1165.32
XS GIS Cut Line= 3
     560756.4358    5416563.1777     560900.2033     5415608.496
     561729.4406    5414235.1136
#Sta/Elev= 30
       0  141.14  306.82  129.45   340.8  125.18  378.78  123.39  551.68  120.57
  579.67  115.25  595.66  114.53  764.56  117.08  779.55  119.33  825.53  119.22
  844.52  121.84  933.47  124.78  975.44  117.88 1023.42  115.09 1042.42  106.85
1050.695 106.2391188.907 106.251 1193.35  107.56 1203.35  109.87 1243.33  112.01
 1265.32  115.92 1443.25  121.99 1460.24  126.01 1755.11  130.25 1805.09  135.41
 1925.04  141.62 1971.02  138.61    2029  141.81 2490.77  146.67 2569.73   149.2
#Mann= 3 , 0 , 0
       0     .12       0 1042.42    .035       0 1193.35     .12       0
Bank Sta=1042.42,1193.35
XS Rating Curve= 0 ,0
Exp/Cntr=0.3,0.1

Type RM Length L Ch R = 1 ,88.6151 ,1054.24,1081.96,1119.36
BEGIN DESCRIPTION:
E17 (SEM 2016)
END DESCRIPTION:
XS GIS Cut Line= 4
     561463.5271    5417063.8699     561880.0633    5416369.7731
     562085.4953    5415835.4598     562636.1641    5414558.3531
#Sta/Elev= 30
       0  145.93   72.95  145.65  105.93     140   160.9  136.51  335.79  131.95
  398.75  134.45  556.65  126.37  686.56  127.44  720.54  130.69  739.53  126.53
   792.5  124.79  831.46  118.41  906.39  116.23  921.38  112.78  988.31  113.41
 1005.11  105.791034.612 103.488 1224.08  105.79 1234.07  110.46 1260.04   108.8
    1305  113.28 1381.92  130.63 1438.91   136.4 1573.89  130.52 1750.87  128.23
 1870.85  133.89 2277.78  143.65 2323.77   149.8 2448.75  155.29 2772.68   160.9
#Mann= 3 , 0 , 0
       0     .12       0 1005.11    .035       0 1224.08     .12       0
Bank Sta=1005.11,1224.08
XS Rating Curve= 0 ,0
Exp/Cntr=0.3,0.1

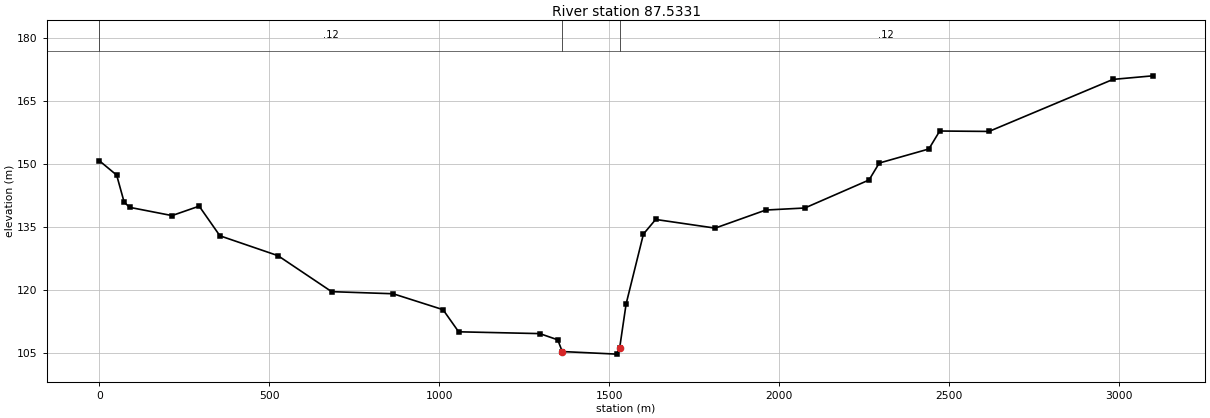
Type RM Length L Ch R = 1 ,87.5331 ,1263.46,1218.22,1177.28
XS GIS Cut Line= 3
     562350.6952     5417638.073     562916.2065    5416477.3041
     564123.2949    5415130.2685
#Sta/Elev= 30
       0  150.68   50.97  147.26   72.95  140.84   88.94  139.59  213.87  137.62
  293.82  139.87  354.78  132.81  525.67  128.08  683.57  119.51  864.46  119.01
 1011.37  115.22 1057.34  109.95 1296.19  109.52    1349  108.04 1362.18  105.25
1522.643 104.634 1531.16  106.12 1550.16  116.58 1601.15  133.23 1637.14   136.7
 1812.12  134.64 1961.09  138.94 2076.08  139.43 2265.04   146.1 2295.03  150.13
 2441.01  153.48    2473  157.76 2617.97  157.66  2982.9  170.05 3099.88   170.9
#Mann= 3 , 0 , 0
       0     .12       0 1362.18    .035       0 1531.16     .12       0
Bank Sta=1362.18,1531.16
XS Rating Curve= 0 ,0
Exp/Cntr=0.3,0.1