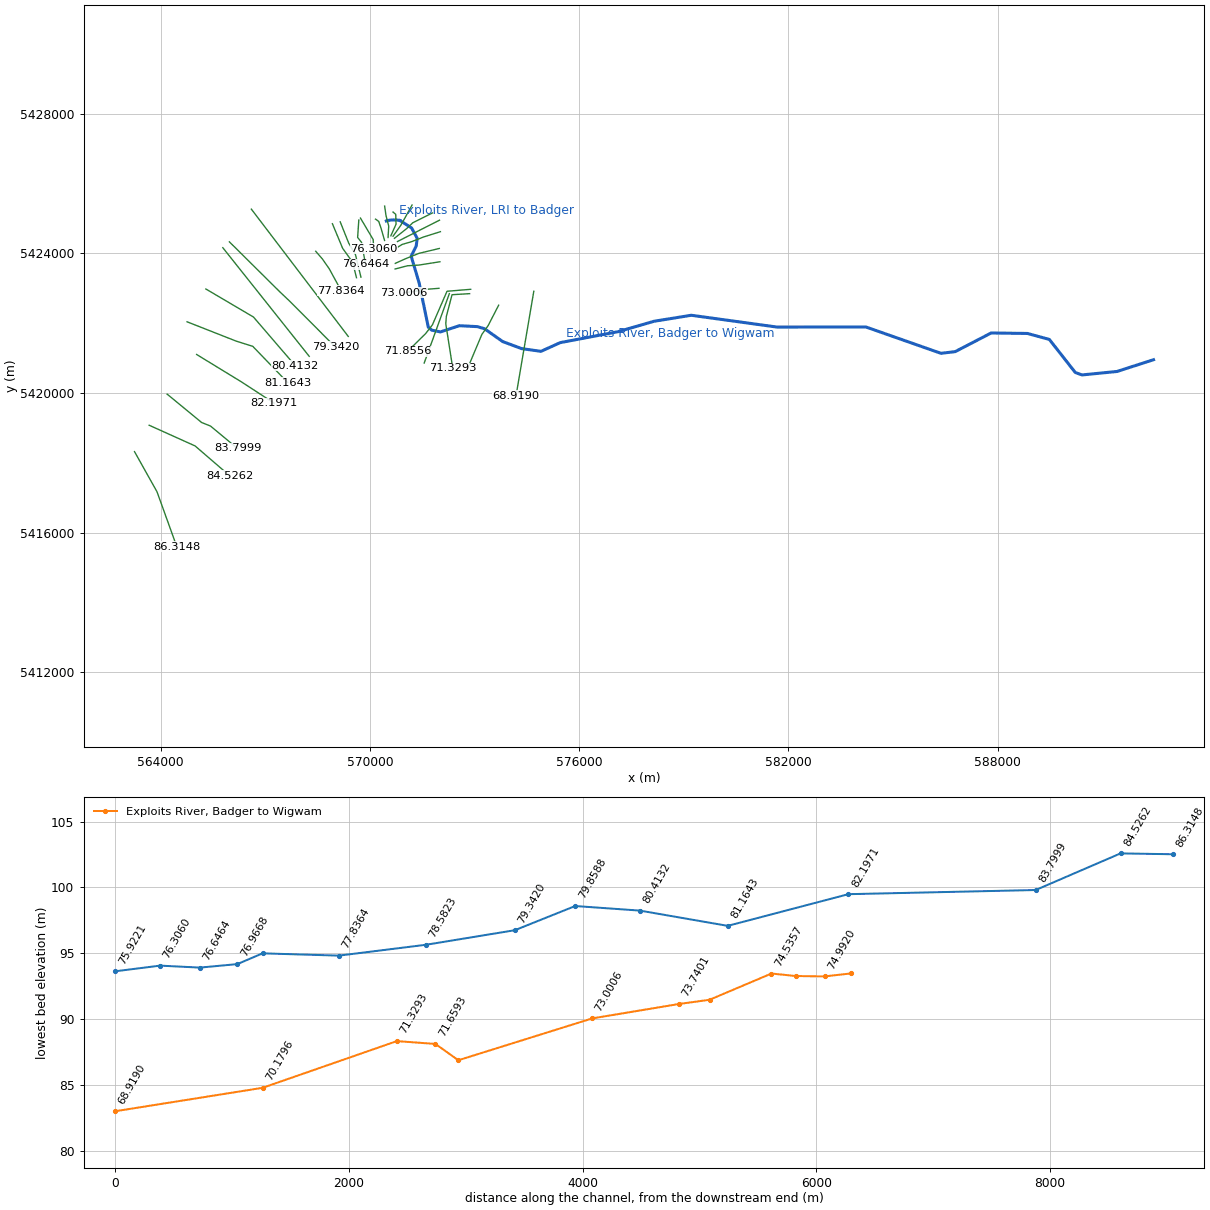
HEC-RAS study Unsteady_RAS.prj: Unsteady_RAS

--- Unsteady_RAS.g01 (geometry) --- (continued)

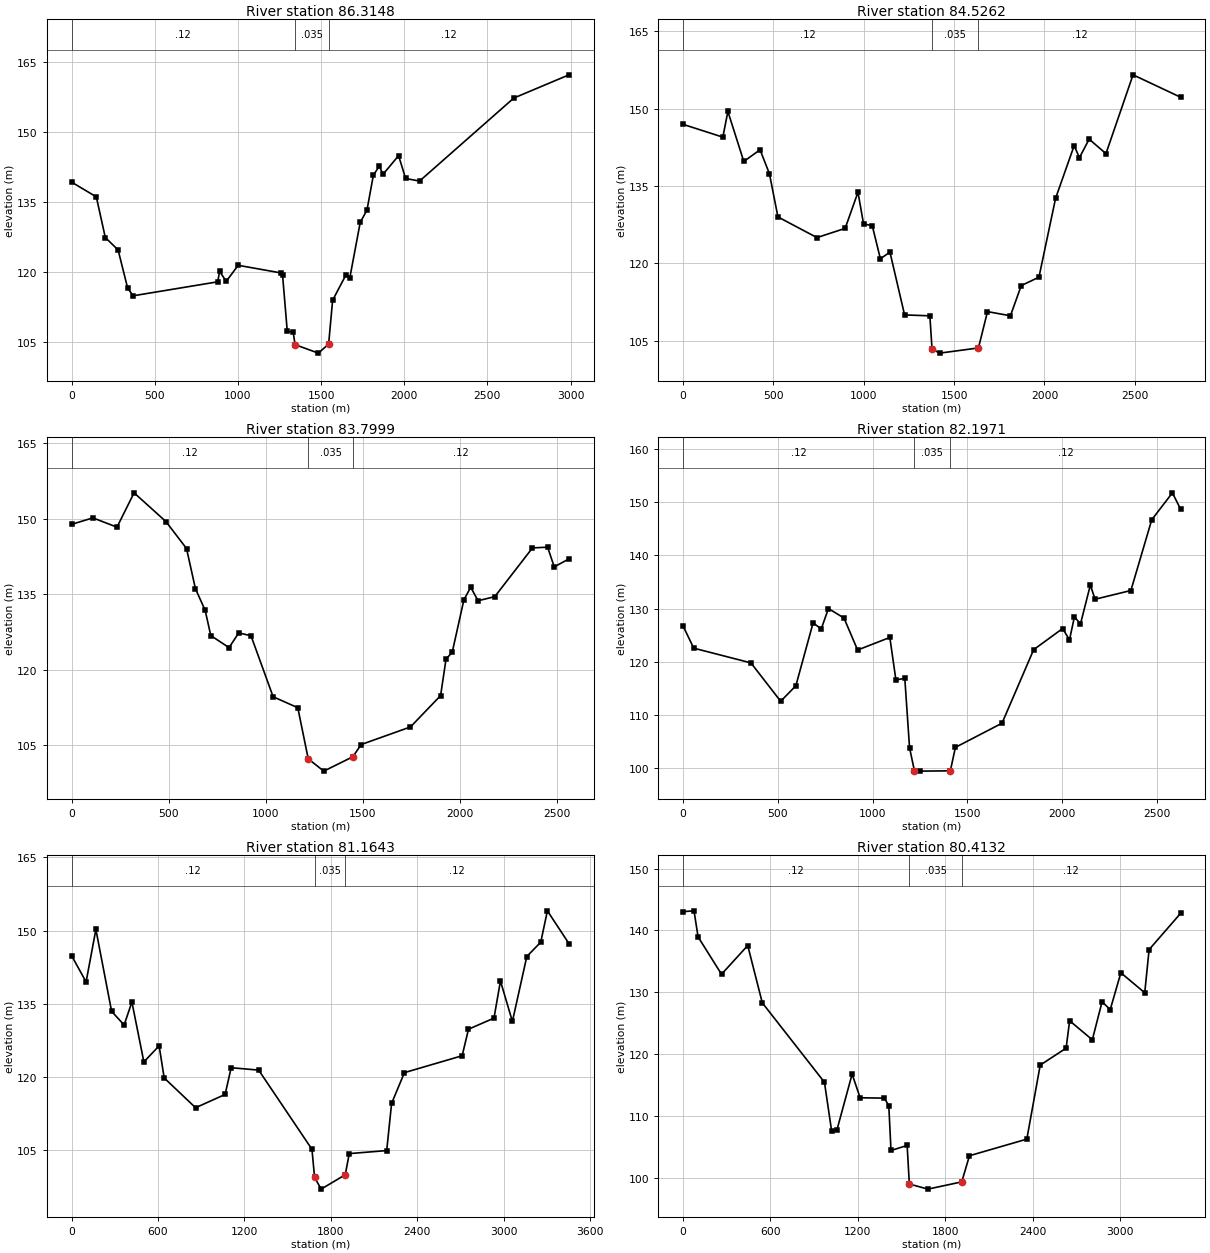
Type RM Length L Ch R = 1 ,86.3148 ,433.98,447.165,461.88
BEGIN DESCRIPTION:
E16 (SEM 2016)
END DESCRIPTION:
XS GIS Cut Line= 4
     563252.2873    5418318.6907     563897.3454    5417168.5059
     564018.3756    5416833.1237     564464.7747     5415596.118
#Sta/Elev= 30
       0  139.19  148.97  136.03  202.96  127.31  279.94  124.64  336.93  116.51
  369.92  114.81  878.82  117.81  889.81  120.06   929.8  117.91 1001.79  121.35
 1256.73  119.73 1268.73  119.17 1296.72  107.23 1332.46     107 1343.69  104.34
1483.394  102.52 1545.43  104.45  1569.4  113.85  1650.3  119.35 1672.27  118.56
 1735.22  130.53 1776.19  133.22 1814.16  140.64 1850.14  142.63 1872.12  140.85
 1966.05  144.86 2008.02  139.97 2091.96  139.41 2658.55  157.21  2990.3  162.19
#Mann= 3 , 0 , 0
       0     .12       0 1343.69    .035       0 1545.43     .12       0
Bank Sta=1343.69,1545.43
XS Rating Curve= 0 ,0
Exp/Cntr=0.3,0.1

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
Type RM Length L Ch R = 1 ,84.5262 ,725.12,726.32,775.44
XS GIS Cut Line= 3
      563673.558     5419073.411      564989.238    5418481.2199
     565982.4579    5417626.5917
#Sta/Elev= 30
       0  146.97  219.97  144.49  247.97  149.47  335.96  139.77  425.95  142.04
  477.94  137.38  524.93  129.01   740.9     125  896.88  126.79  967.87   133.8
  998.86  127.64 1046.86  127.33 1091.85  120.89 1144.84  122.18 1225.83     110
  1365.8  109.82  1377.8  103.371420.519 102.584  1634.7  103.59 1684.67  110.64
 1811.61  109.83 1871.58  115.69 1969.53  117.32 2061.48  132.61 2164.43  142.85
 2193.42   140.5 2247.39   144.1 2340.35  141.29 2490.27  156.58 2753.15  152.24
#Mann= 3 , 0 , 0
       0     .12       0  1377.8    .035       0  1634.7     .12       0
Bank Sta=1377.8,1634.7
XS Rating Curve= 0 ,0
Exp/Cntr=0.3,0.1

Type RM Length L Ch R = 1 ,83.7999 ,1609.06,1602.76,1572.5
BEGIN DESCRIPTION:
E15 (SEM 2016)
END DESCRIPTION:
XS GIS Cut Line= 4
      564188.264    5419964.8066      565176.696    5419152.4458
     565432.0035    5419049.9886     566206.5571    5418408.3497
#Sta/Elev= 30
       0  148.87  109.95  150.16   233.9  148.31  321.86  155.14  485.78  149.43
  591.74  144.07  637.72  136.07  687.69  131.78  716.68  126.76  810.64  124.36
  860.62  127.29  923.59  126.72 1037.54  114.59 1164.48  112.41  1218.2  102.25
1298.319  99.803 1447.87  102.66 1490.73  105.09 1744.49  108.59 1899.46  114.82
 1927.45  122.08 1959.44  123.45 2019.43  133.88 2054.43  136.36 2092.42  133.68
  2178.4   134.5 2372.35  144.19 2450.33  144.33 2484.32  140.42 2560.31     142
#Mann= 3 , 0 , 0
       0     .12       0  1218.2    .035       0 1447.87     .12       0
Bank Sta=1218.2,1447.87
XS Rating Curve= 0 ,0
Exp/Cntr=0.3,0.1

Type RM Length L Ch R = 1 ,82.1971 ,999.58,1032.8,1057.66
XS GIS Cut Line= 3
     565033.3076    5421100.5843     566318.6765    5420315.1438
     567255.9261    5419706.3444
#Sta/Elev= 30
       0  126.75   55.98  122.59  357.85  119.82  514.78  112.61  594.74  115.52
  685.71  127.34  728.69   126.2  766.67  130.03  848.64  128.25  920.61  122.24
 1090.54   124.6 1122.52  116.62  1169.5  116.92 1194.49  103.891220.415  99.509
1251.135  99.4871409.744  99.543 1436.38  103.95 1682.29  108.49 1849.24  122.31
 2002.19  126.28 2038.17  124.14 2064.17  128.47 2096.15  127.14 2148.14  134.43
 2173.13  131.78 2362.06  133.42 2472.03  146.71 2580.99  151.77 2623.97  148.72
#Mann= 3 , 0 , 0
       0     .12       01220.415    .035       01409.744     .12       0
Bank Sta=1220.415,1409.744
XS Rating Curve= 0 ,0
Exp/Cntr=0.3,0.1

Type RM Length L Ch R = 1 ,81.1643 ,817.36,751.12,671.84
BEGIN DESCRIPTION:
E14 (SEM 2016)
END DESCRIPTION:
XS GIS Cut Line= 4
     564758.8564    5422036.7916     566167.6463    5421483.1889
     566642.4197    5421334.0585     567643.0346    5420297.0325
#Sta/Elev= 30
       0  144.88  100.98  139.49  168.96  150.23  277.94  133.48  364.92  130.67
  418.91  135.38  501.89  123.12  607.86  126.41  642.86  119.84   860.8  113.74
 1065.76  116.46 1107.75  121.93  1298.7  121.44 1668.54  105.23 1686.53   99.49
1732.304  97.081 1899.39  100.02 1927.37  104.35 2187.18  104.97 2221.16  114.63
 2310.09  120.92 2710.81  124.38 2754.77  129.81 2931.65  132.08 2976.61  139.68
 3059.55   131.4 3159.48  144.69 3256.41  147.63 3302.38  154.04 3452.27  147.32
#Mann= 3 , 0 , 0
       0     .12       0 1686.53    .035       0 1899.39     .12       0
Bank Sta=1686.53,1899.39
XS Rating Curve= 0 ,0
Exp/Cntr=0.3,0.1

Type RM Length L Ch R = 1 ,80.4132 ,601.92,554.4,538.26
XS GIS Cut Line= 3
     565298.3235    5422976.1352     566663.3482    5422172.9678
     567858.3196    5420783.4488
#Sta/Elev= 30
       0  143.04   74.99  143.17  102.99  138.96  263.96  132.93  443.94  137.57
  543.93  128.32  970.87  115.49 1019.87  107.67 1056.86  107.82 1160.84  116.81
 1215.84  112.99 1381.81  112.93 1412.81  111.72 1427.81  104.48 1538.79  105.29
 1553.79   99.071680.919  98.239 1913.73   99.41 1966.72  103.63 2360.64  106.31
 2452.62  118.26 2630.58     121 2654.58  125.42 2810.54  122.35 2877.53  128.49
 2933.52  127.22  3006.5  133.17 3170.46  129.94 3200.46  136.91 3416.41  142.75
#Mann= 3 , 0 , 0
       0     .12       0 1553.79    .035       0 1913.73     .12       0
Bank Sta=1553.79,1913.73
XS Rating Curve= 0 ,0
Exp/Cntr=0.3,0.1

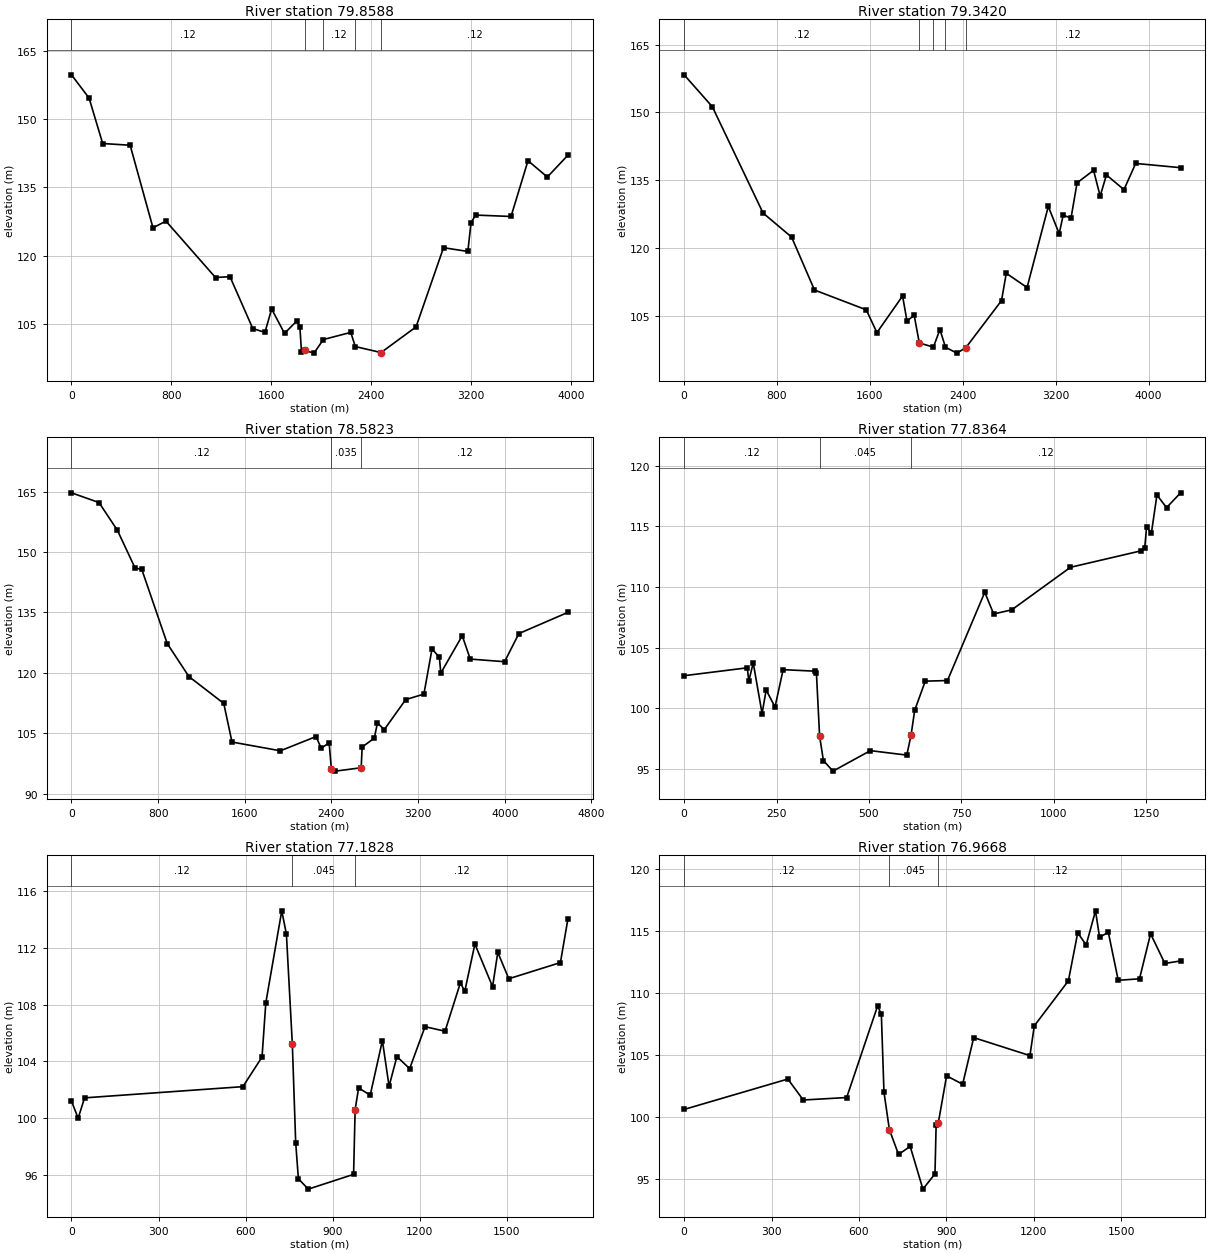
Type RM Length L Ch R = 1 ,79.8588 ,508.08,516.72,560.22
BEGIN DESCRIPTION:
Three Mile Island
END DESCRIPTION:
XS GIS Cut Line= 3
     565784.1097    5424158.5421     567047.5055    5422571.6628
     568261.1888    5421046.9442
#Sta/Elev= 30
       0  159.67  140.96  154.57  249.92  144.59  469.86  144.22   652.8   126.1
  756.77  127.56 1153.65  115.18 1269.61  115.37 1452.56  103.97 1549.53  103.15
 1603.52  108.27 1706.49  102.92 1805.46  105.66 1829.45  104.42 1842.45   98.86
 1867.44   99.181942.703  98.588  2017.4  101.57 2237.36  103.14 2273.36  100.03
2480.009  98.715 2760.27  104.35 2980.23  121.73  3175.2   120.9 3200.19  127.15
 3237.18  128.89 3521.13  128.58 3657.11  140.82 3812.08  137.24 3977.05  142.04
#Mann= 5 ,-1 , 0
       0     .12       0 1867.44    .035       0  2017.4     .12       0
 2273.36    .035       02480.009     .12       0
Bank Sta=1867.44,2480.009
XS Rating Curve= 0 ,0
Exp/Cntr=0.3,0.1

Type RM Length L Ch R = 1 ,79.3420 ,800.24,759.76,736.16
BEGIN DESCRIPTION:
E14A (SEM 2019)
END DESCRIPTION:
XS GIS Cut Line= 4
     565972.4243    5424327.1012       567406.25     5422906.711
     567706.6702    5422621.4408     569008.5241    5421316.7983
#Sta/Elev= 30
       0  158.31  242.91  151.25  679.75  127.74  925.65  122.41 1122.58  110.71
 1568.42  106.33 1660.39  101.29 1881.31  109.39  1919.3  103.85 1981.27  105.13
 2025.27      99 2146.77   98.08 2202.94  101.97 2250.93   98.05 2348.35   96.75
 2425.98   97.95  2733.4  108.37 2774.38  114.42  2953.3  111.26 3136.21  129.19
 3230.16  123.17 3264.14  127.24 3332.11  126.65 3384.09  134.42 3526.02  137.18
 3582.99  131.49 3636.96  136.16 3787.89  132.92 3888.84  138.71 4275.65  137.77
#Mann= 5 ,-1 , 0
       0     .12       0 2025.27    .035       0 2146.77     .12       0
 2250.93    .035       0 2425.98     .12       0
Bank Sta=2025.27,2425.98
XS Rating Curve= 0 ,0
Exp/Cntr=0.3,0.1

Type RM Length L Ch R = 1 ,78.5823 ,760.72,745.92,739.52
BEGIN DESCRIPTION:
E13 (SEM 2016)
END DESCRIPTION:
XS GIS Cut Line= 2
      566602.275     5425263.202     569380.3512    5421617.3471
#Sta/Elev= 30
       0  164.68  253.98  162.27  423.97  155.38  586.96  146.02  648.95  145.69
  883.94  127.29 1083.92  119.11  1405.9  112.44 1481.89  102.86 1928.86  100.69
 2257.84  104.22 2305.83  101.31 2378.83  102.682399.238  96.1872437.042  95.645
 2674.61  96.484  2683.8  101.62 2795.79  103.83 2824.79  107.59 2887.78  105.94
 3085.76  113.39 3253.75  114.75 3328.74  125.96 3396.74  123.88 3409.74  119.96
 3607.72  129.24 3681.71  123.44 3998.69  122.79 4130.68  129.77 4583.68  135.03
#Mann= 3 , 0 , 0
       0     .12       02399.238    .035       0 2674.61     .12       0
Bank Sta=2399.238,2674.61
XS Rating Curve= 0 ,0
Exp/Cntr=0.3,0.1

Type RM Length L Ch R = 1 ,77.8364 ,653.66,653.59,657.02
BEGIN DESCRIPTION:
E13A (SEM 2019)
END DESCRIPTION:
XS GIS Cut Line= 4
      568447.439     5424057.046      568641.432     5423832.493
       568840.31      5423545.85      569174.016      5422932.61
#Sta/Elev= 30
       0  102.69  170.92  103.34  174.92  102.24  186.91  103.75   210.9   99.57
   221.9  101.51  245.88  100.11  267.87  103.19  354.85  103.06  357.85  102.95
  366.51   97.71  376.77   95.69  402.73   94.82503.9301   96.51  602.45   96.14
   613.9   97.78  623.82   99.84  652.46  102.24  712.44  102.29   813.4  109.57
  837.39  107.78  886.37  108.12 1045.31  111.63 1235.23  112.98 1246.23  113.26
 1251.22  114.95 1264.22  114.46 1279.21  117.59  1305.2  116.55 1343.19  117.77
#Mann= 3 , 0 , 0
       0     .12       0  366.51    .045       0   613.9     .12       0
Bank Sta=366.51,613.9
XS Rating Curve= 0 ,0
Exp/Cntr=0.3,0.1

Type RM Length L Ch R = 1 ,77.1828 ,225.12,216.02,208.8
BEGIN DESCRIPTION:
E12-1 (SEM 2016)
END DESCRIPTION:
XS GIS Cut Line= 4
  568925.2588036 5424845.8462831  569219.3729036 5424140.9509831
  569503.9473036 5423744.7087831  569616.0697036 5423298.9281831
#Sta/Elev= 30
       0   101.2   22.99   99.99   44.99  101.43  590.84  102.22  656.82  104.31
  669.82  108.13   724.8  114.62   740.8  112.98  761.19  105.25  772.79   98.28
782.1189  95.723 816.272  94.993972.3989  96.035  977.72   100.6  989.72  102.13
 1029.71  101.62 1071.69  105.47 1094.69  102.25 1121.68  104.34 1165.66  103.49
 1218.65  106.45 1287.61  106.13 1340.57  109.54 1355.56  108.94 1390.53  112.28
 1451.49  109.27 1469.47  111.69 1507.44  109.83 1685.31  110.97 1711.29  114.06
#Mann= 3 , 0 , 0
       0     .12       0  761.19    .045       0  977.72     .12       0
Bank Sta=761.19,977.72
XS Rating Curve= 0 ,0
Exp/Cntr=0.3,0.1

Type RM Length L Ch R = 1 ,76.9668 ,323.67,320.44,331.82
BEGIN DESCRIPTION:
Gull Rocks - E12-2 (SEM 2016)
END DESCRIPTION:
XS GIS Cut Line= 4
  569149.5033036 5424900.2187831  569394.4403036 5424287.6522831
  569586.6854036 5423960.0336831  569743.9005036 5423314.9675831
#Sta/Elev= 30
       0   100.6  355.85  103.05  408.83  101.36  557.76  101.56  663.72  108.93
  676.72  108.28  685.71     102  704.22   98.98  735.69   96.97  775.68   97.62
819.3459  94.176  860.77  95.408  864.64   99.31  872.03    99.5  900.63  103.31
  955.61  102.63  993.59  106.39 1186.57  104.94 1201.57  107.34 1318.56  110.97
 1350.56  114.84 1379.56  113.86 1411.56  116.61 1425.56  114.48 1455.56  114.88
 1489.55  111.01 1562.55  111.13 1600.55  114.76 1649.55  112.37 1703.54  112.57
#Mann= 3 , 0 , 0
       0     .12       0  704.22    .045       0  872.03     .12       0
Bank Sta=704.22,872.03
XS Rating Curve= 0 ,0
Exp/Cntr=0.3,0.1

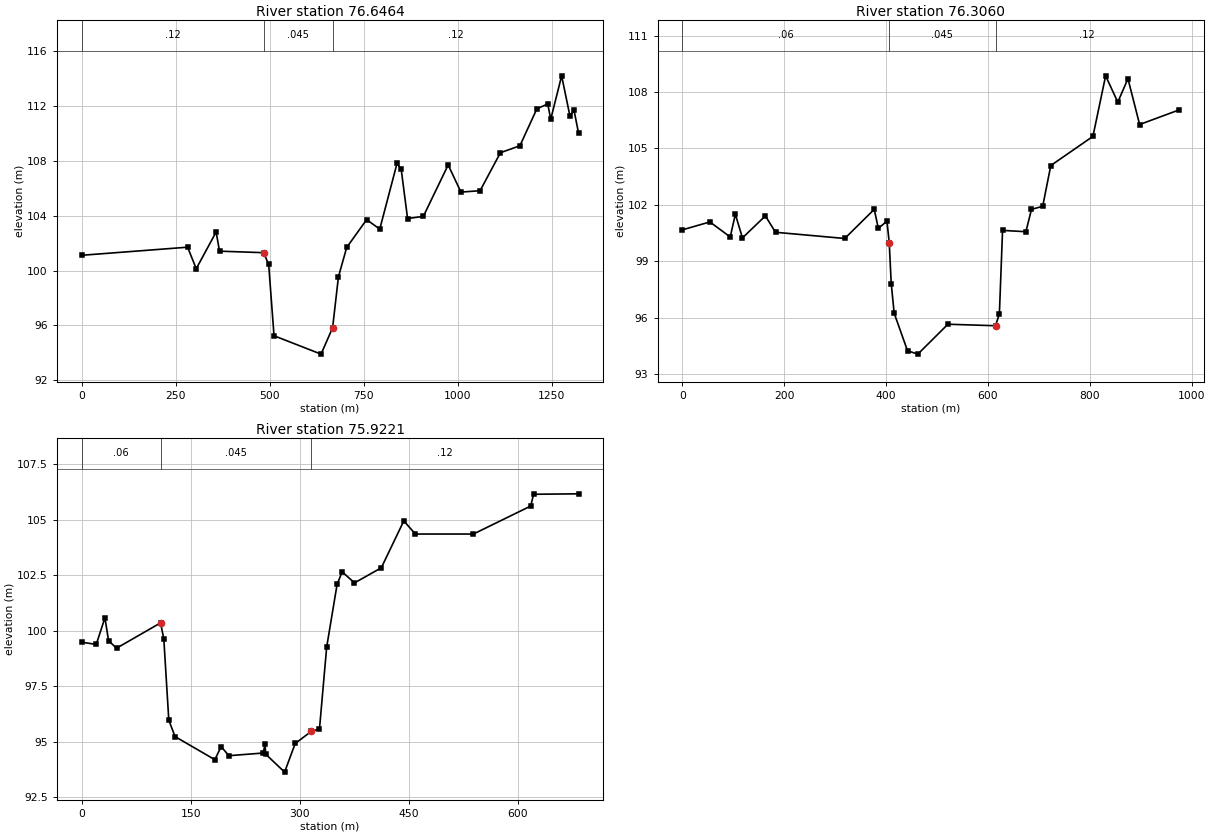
Type RM Length L Ch R = 1 ,76.6464 ,344.31,340.33,331.62
BEGIN DESCRIPTION:
E12-2A (SEM 2019)
END DESCRIPTION:
XS GIS Cut Line= 4
  569682.8194036 5424951.4605831  569648.5690036 5424453.4489831
  569761.0250036 5424310.9259831  569874.5592036 5423680.3881831
#Sta/Elev= 30
       0  101.12  281.54  101.71   304.5  100.14  357.42  102.82   366.4  101.42
  483.81  101.31  497.19  100.45  511.39   95.25  636.48   93.91  667.22   95.83
  682.73   99.55  704.72  101.69  757.69  103.72  792.67  103.03  838.65  107.83
  849.64   107.4  866.64   103.8  908.61  103.96  974.58  107.71 1008.56  105.73
 1059.54  105.83 1113.51   108.6 1165.48  109.11 1210.46   111.8 1239.44  112.16
 1247.44  111.04 1276.42  114.21 1298.41  111.29 1309.41  111.69  1321.4  110.03
#Mann= 3 , 0 , 0
       0     .12       0  483.81    .045       0  667.22     .12       0
Bank Sta=483.81,667.22
XS Rating Curve= 0 ,0
Exp/Cntr=0.3,0.1

Type RM Length L Ch R = 1 ,76.3060 ,405.18,383.92,369.84
BEGIN DESCRIPTION:
E12-2B (SEM 2019)
END DESCRIPTION:
XS GIS Cut Line= 3
  569729.4079036 5425007.8385831  570093.9820036 5424393.3684831
  570112.7272036 5424132.9387831
#Sta/Elev= 30
       0  100.67   53.96  101.09   93.93  100.29  103.93   101.5  117.91  100.24
  162.88  101.41  182.87  100.54  318.77  100.21  376.73  101.76  384.72  100.75
  401.71  101.13  406.13   99.99  410.08   97.81  415.81   96.24  442.04   94.24
  462.37   94.06  521.39   95.65  614.85   95.57  622.47    96.2   628.7  100.64
  674.51  100.57  685.51  101.76  707.49  101.92  723.45  104.09  806.17  105.64
  831.09  108.86     855  107.46  874.94  108.71  897.86  106.27  975.59  107.05
#Mann= 3 , 0 , 0
       0     .06       0  406.13    .045       0  614.85     .12       0
Bank Sta=406.13,614.85
XS Rating Curve= 0 ,0
Exp/Cntr=0.3,0.1

Type RM Length L Ch R = 1 ,75.9221 ,106.86,249,204.55
BEGIN DESCRIPTION:
US of Little Red Indian Brook - E12-2C (SEM 2019)
END DESCRIPTION:
XS GIS Cut Line= 4
  570161.2672036 5424977.7247831  570253.5810036 5424911.4469831
  570325.7540036 5424697.5249831  570420.8113036 5424366.6182831
#Sta/Elev= 30
       0   99.48   19.94   99.38    31.9  100.58   36.88   99.55   47.85   99.21
  108.48  100.35  112.94   99.62  119.79   95.97  128.42   95.23  183.17   94.19
  191.83   94.78  202.43   94.37  249.67   94.49  252.28    94.9  253.11   94.44
  279.16   93.63  293.74   94.92  316.08   95.47  327.14   95.57  337.07   99.26
  351.39  102.08  358.37  102.65  375.34  102.15  412.26  102.83   443.2  104.94
  459.16  104.35     539  104.35  617.84  105.61  621.83  106.14   683.7  106.16
#Mann= 3 , 0 , 0
       0     .06       0  108.48    .045       0  316.08     .12       0
Bank Sta=108.48,316.08
XS Rating Curve= 0 ,0
Exp/Cntr=0.3,0.1

River Reach=Exploits River  ,LRI to Badger
Reach XY= 28
     570472.2323    5424925.2875     570490.7337      5424932.56
     570502.6744     5424934.647     570537.9381    5424940.7905
     570545.8987    5424942.1751     570556.8618    5424944.0892
     570568.4135     5424946.101     570585.3222    5424949.0433
     570600.1174     5424949.998     570619.2382    5424951.2296
      570629.548    5424951.8853     570639.6579    5424952.5383
     570656.0815    5424953.5945     570665.1825    5424954.1743
     570668.2194    5424954.3742     570670.1597    5424954.3298
     570694.2533    5424953.7772     570700.6342    5424953.6312
     570714.3464    5424953.3119     570729.1385    5424952.9767
        570738.5    5424952.7601     570753.4519    5424951.6772
     570774.0483    5424950.1986      570787.329    5424949.2337
      570793.694    5424948.7776     570807.9854     5424947.746
     570858.7335    5424937.4359      570864.899    5424936.1873

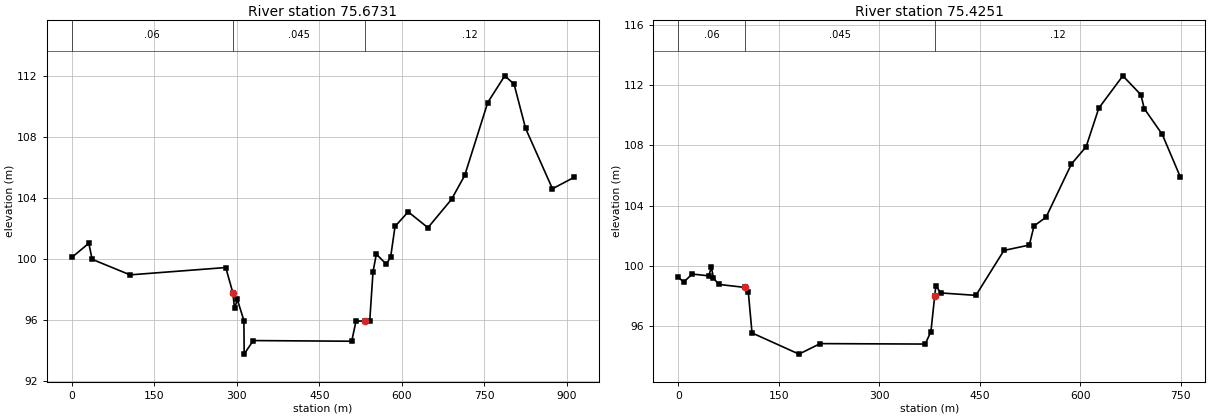
Type RM Length L Ch R = 1 ,75.6731 ,278.05,248.06,223.48
BEGIN DESCRIPTION:
Badger Arena - E11 (SEM 2016)
END DESCRIPTION:
XS GIS Cut Line= 4
  570423.0008036 5425350.7759831  570461.6157036 5425082.6362831
  570539.7153036 5424776.7940831  570521.3532036 5424451.2851831
#Sta/Elev= 30
       0   100.1   30.99  101.03   36.99   99.98  105.96   98.96   279.9   99.44
  292.72   97.79  295.88   96.76  300.87   97.35  312.86   95.97313.3711  93.767
329.8301  94.655508.8269  94.612  516.64   95.93   533.3   95.94  541.61   95.96
   547.6   99.17   553.6  100.32  571.58   99.66  579.57  100.12  587.56  102.13
  611.49  103.09  647.38  102.05  690.25  103.91  714.18  105.47  756.06  110.25
  786.96     112  803.91  111.46  824.85  108.56  873.71   104.6  912.59  105.34
#Mann= 3 , 0 , 0
       0     .06       0  292.72    .045       0   533.3     .12       0
Bank Sta=292.72,533.3
XS Rating Curve= 0 ,0
Exp/Cntr=0.3,0.1

Type RM Length L Ch R = 1 ,75.4251 ,161.39,206.16,116.29
BEGIN DESCRIPTION:
02YO013 ER at Badger - E11A (SEM 2019)
END DESCRIPTION:
XS GIS Cut Line= 4
  570663.1789036 5425180.1249831  570740.8700036 5425115.5109831
  570749.9510036 5424832.1089831  570600.7284036 5424498.9102831
#Sta/Elev= 30
       0   99.25    7.93   98.89    20.8   99.44   45.57   99.32   49.53    99.9
   52.51   99.18   60.43   98.75    99.3   98.55  104.68   98.22  110.17   95.52
  180.29   94.11  211.99   94.81  368.75   94.78  377.29   95.61  382.94   97.97
   384.6   98.63  392.58   98.18  444.45   98.02  486.34  101.01  524.25  101.37
  531.23  102.64  549.19  103.22  587.09  106.76  609.03  107.91  627.99  110.48
   663.9  112.63  690.83  111.37  695.82  110.45  722.75  108.73  749.68   105.9
#Mann= 3 , 0 , 0
       0     .06       0    99.3    .045       0  382.94     .12       0
Bank Sta=99.3,382.94
XS Rating Curve= 0 ,0
Exp/Cntr=0.3,0.1

River Reach=Exploits River  ,Badger to Wigwam
Reach XY= 30
      570864.899    5424936.1873     571195.2498    5424724.2801
      571356.624    5424426.7302     571328.2006     5424207.099
     571183.0068    5423918.2107     571411.6234    5423151.0869
     571674.9089    5421879.9746     571773.3615    5421796.6132
     572022.6873    5421746.9929     572566.3692    5421924.5137
     573080.1504    5421898.1313     573283.8824    5421838.7221
     573808.3096      5421469.97     574349.5708    5421268.6343
     574904.0327    5421190.2143     575456.2876    5421439.8079
     577110.3553    5421752.5776     578147.6695    5422051.9415
     579213.1222    5422223.6444     581669.6703    5421885.7197
     584222.1192    5421887.1708     586368.8924    5421134.0849
     586778.8435    5421181.8152     587808.8557    5421716.0084
     588849.0368    5421702.6129     589477.3203    5421531.8238
     590220.6278    5420584.8392     590413.3494    5420514.6239
     591417.3476    5420613.8169592464.4891674575420950.70166653

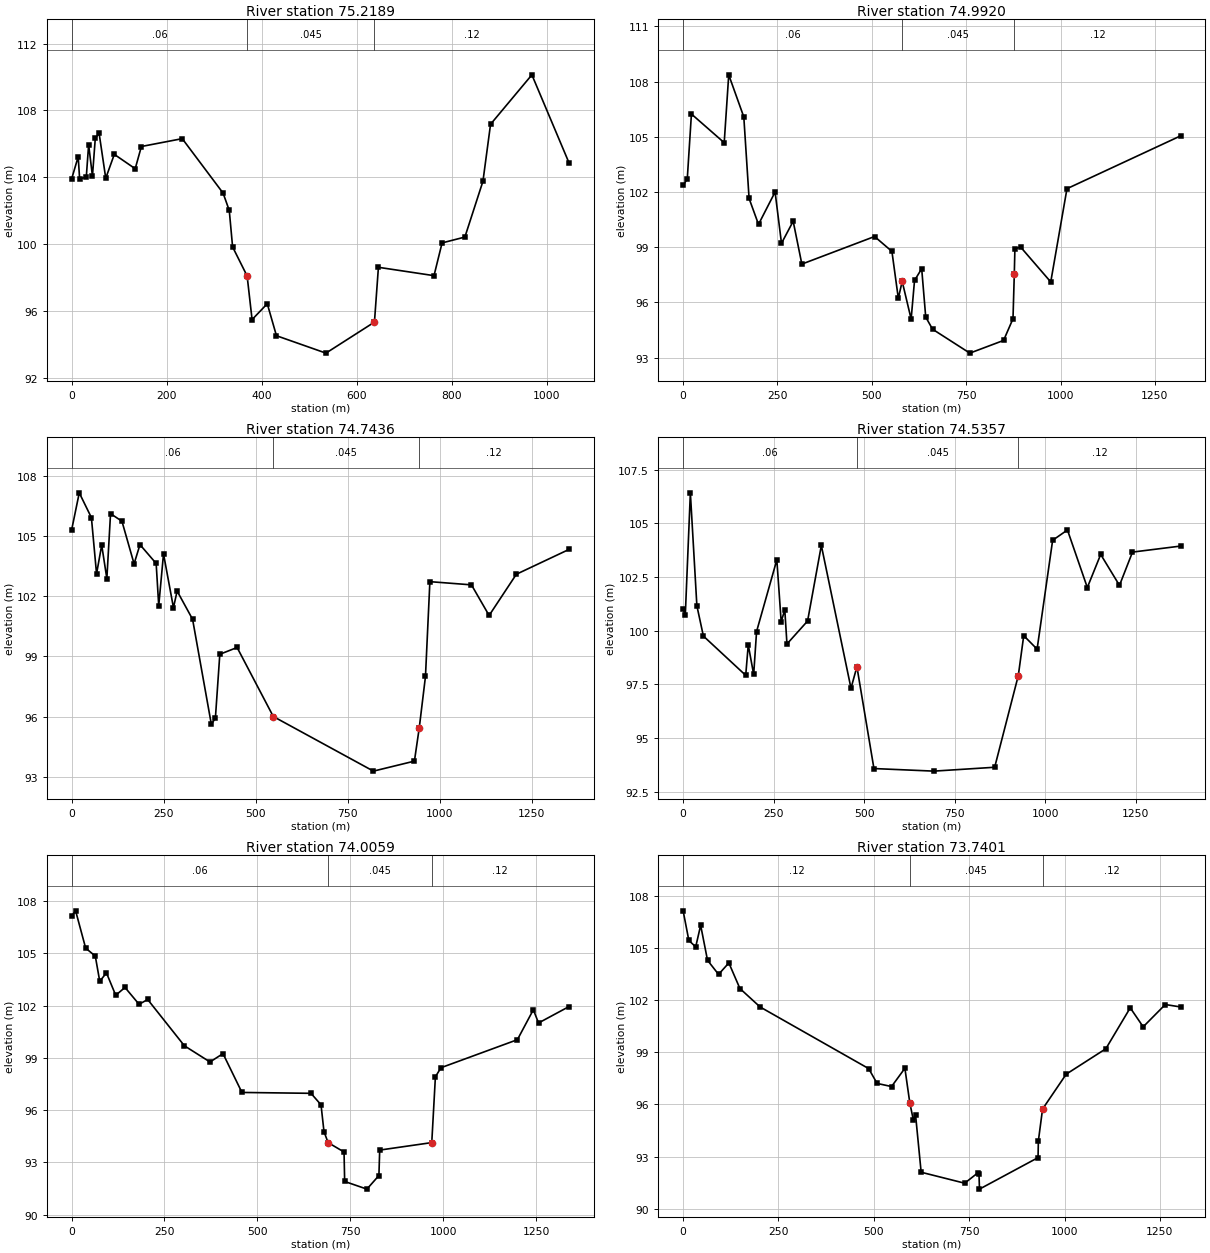
Type RM Length L Ch R = 1 ,75.2189 ,292.68,226.95,198.06
BEGIN DESCRIPTION:
DS of Badger Brook - E10 (SEM 2016)
END DESCRIPTION:
XS GIS Cut Line= 4
  571208.3625036 5425380.4172831  571026.9688036 5425051.2663831
  570878.1888036 5424787.6000831  570664.2285036 5424488.3268831
#Sta/Elev= 30
       0  103.88   13.99  105.23   16.99  103.91   30.99     104   35.98  105.95
   43.98  104.07   49.98  106.33   57.97  106.64   71.97  103.94   89.96  105.37
  133.94  104.51  146.93  105.84  232.89  106.31  318.85  103.05  331.84  102.01
  338.84   99.83  369.42   98.09  379.82   95.48  411.79   96.43 431.094  94.515
535.2159  93.473  637.26   95.33   645.6   98.61  762.54   98.11  779.54  100.07
  827.52  100.42  865.51  103.76  881.51  107.17  968.48  110.13 1046.46  104.87
#Mann= 3 , 0 , 0
       0     .06       0  369.42    .045       0  637.26     .12       0
Bank Sta=369.42,637.26
XS Rating Curve= 0 ,0
Exp/Cntr=0.3,0.1

Type RM Length L Ch R = 1 ,74.9920 ,312.1,248.41,210.99
BEGIN DESCRIPTION:
E10A (SEM 2019)
END DESCRIPTION:
XS GIS Cut Line= 4
  571792.2087036 5425153.3873831  571226.6670036 5424871.0939831
  571051.7963036 5424703.8684831  570703.9625036 5424428.1054831
#Sta/Elev= 30
       0  102.36   10.98  102.71   21.97  106.24  108.84  104.68  120.82  108.37
  160.77  106.08  174.75  101.65  199.71  100.24  243.65     102  260.62   99.21
  291.58  100.41  314.54   98.08  507.26   99.58   553.2   98.77  570.17   96.22
  580.41   97.14  604.12   95.09  613.11   97.19  632.08   97.83  642.77    95.2
  660.88   94.54  759.66   93.24  849.04   93.93  873.99   95.11  877.47   97.55
  879.04   98.91  894.04   99.01  974.02   97.11 1017.01  102.18 1317.93  105.05
#Mann= 3 , 0 , 0
       0     .06       0  580.41    .045       0  877.47     .12       0
Bank Sta=580.41,877.47
XS Rating Curve= 0 ,0
Exp/Cntr=0.3,0.1

Type RM Length L Ch R = 1 ,74.7436 ,234.73,207.85,198.51
BEGIN DESCRIPTION:
Junction Brook - E10B (SEM 2019)
END DESCRIPTION:
XS GIS Cut Line= 2
  571995.7882036 5424947.3968831  570790.7695036 5424335.7730831
#Sta/Elev= 30
       0   105.3   20.99  107.18   53.97  105.94   67.97  103.13   81.96  104.57
   95.95  102.89  105.95  106.14  136.93  105.76  169.92  103.63  185.91  104.59
  229.89  103.65  236.89  101.54  249.88  104.13  276.87  101.44  286.86  102.27
  328.84  100.86  379.82   95.61  390.81   95.92  402.81   99.11  449.78   99.45
  548.13      96  820.15   93.27  931.49   93.77  944.64   95.43  961.53      98
  973.52  102.74 1086.47  102.58 1134.45  101.05 1208.41  103.11 1351.34  104.35
#Mann= 3 , 0 , 0
       0     .06       0  548.13    .045       0  944.64     .12       0
Bank Sta=548.13,944.64
XS Rating Curve= 0 ,0
Exp/Cntr=0.3,0.1

Type RM Length L Ch R = 1 ,74.5357 ,582.74,529.78,484.98
BEGIN DESCRIPTION:
Beatons Island - E10C (SEM 2019)
END DESCRIPTION:
XS GIS Cut Line= 5
  572021.8012036 5424617.6342831  571545.2810036 5424467.8599831
  571187.3280036 5424328.4869831  570928.3603036 5424254.2009831
  570739.3846036 5424140.6044831
#Sta/Elev= 30
       0  101.01    5.99  100.72   19.98  106.42   37.96  101.16   55.94   99.75
  172.83   97.92  179.82   99.34  194.81   97.96   202.8   99.96  258.74   103.3
  270.73  100.42  280.72  100.97  286.71   99.38  343.66  100.45  381.62  103.97
  463.54   97.32  479.89   98.32   526.9   93.58  692.39   93.46  860.27   93.64
  925.54   97.91  940.51   99.77  977.43   99.14 1020.34  104.21 1061.25  104.69
 1116.13  102.01 1153.05  103.55 1204.93  102.11 1240.85  103.66 1373.54  103.94
#Mann= 3 , 0 , 0
       0     .06       0  479.89    .045       0  925.54     .12       0
Bank Sta=479.89,925.54
XS Rating Curve= 0 ,0
Exp/Cntr=0.3,0.1

Type RM Length L Ch R = 1 ,74.0059 ,326.93,265.84,219.71
BEGIN DESCRIPTION:
Badger Rough Waters - E09 (SEM 2016)
END DESCRIPTION:
XS GIS Cut Line= 4
  571990.3629036 5424137.1373831  571408.8764036 5423997.4571831
  571009.1638036 5423837.6640831  570727.7093036 5423709.5907831
#Sta/Elev= 30
       0  107.15   10.98  107.45   37.94  105.31    63.9  104.85   75.88   103.4
   93.85  103.89  118.81   102.6  143.77  103.05   181.7  102.08  204.67  102.36
  303.51    99.7  372.39   98.77  407.34   99.25  458.25   97.02  643.97   96.97
  670.94   96.31  678.93   94.77  689.94   94.14  732.86    93.6 734.494  91.909
 794.323  91.468 826.635  92.249  828.74   93.71  968.78   94.14  978.55   97.92
  993.53   98.44 1199.06  100.05 1241.96  101.77 1255.92  101.01 1337.72  101.95
#Mann= 3 , 0 , 0
       0     .06       0  689.94    .045       0  968.78     .12       0
Bank Sta=689.94,968.78
XS Rating Curve= 0 ,0
Exp/Cntr=0.3,0.1

Type RM Length L Ch R = 1 ,73.7401 ,735.54,739.52,762.22
BEGIN DESCRIPTION:
E09A (SEM 2019)
END DESCRIPTION:
XS GIS Cut Line= 4
  572007.7978036 5423756.0833831  571403.7410036 5423661.4829831
  571076.3550036 5423641.0509831  570723.3630036 5423549.1384831
#Sta/Elev= 30
       0  107.12   14.99  105.42   32.97  105.05   45.96  106.29   63.94  104.28
   92.91  103.47  119.89  104.13  148.86  102.66  201.81   101.6  486.54   98.06
  508.52   97.21  546.48   97.03  581.45   98.08  594.29    96.1  603.43   95.13
  609.42    95.4  624.09   92.11   738.2   91.48  771.91   92.06  775.72   92.02
  776.99   91.14  930.59   92.95931.4301   93.91  942.43   95.74 1004.39   97.74
 1108.33    99.2 1172.29  101.55 1206.27  100.46 1264.23  101.74 1304.21   101.6
#Mann= 3 , 0 , 0
       0     .12       0  594.29    .045       0  942.43     .12       0
Bank Sta=594.29,942.43
XS Rating Curve= 0 ,0
Exp/Cntr=0.3,0.1

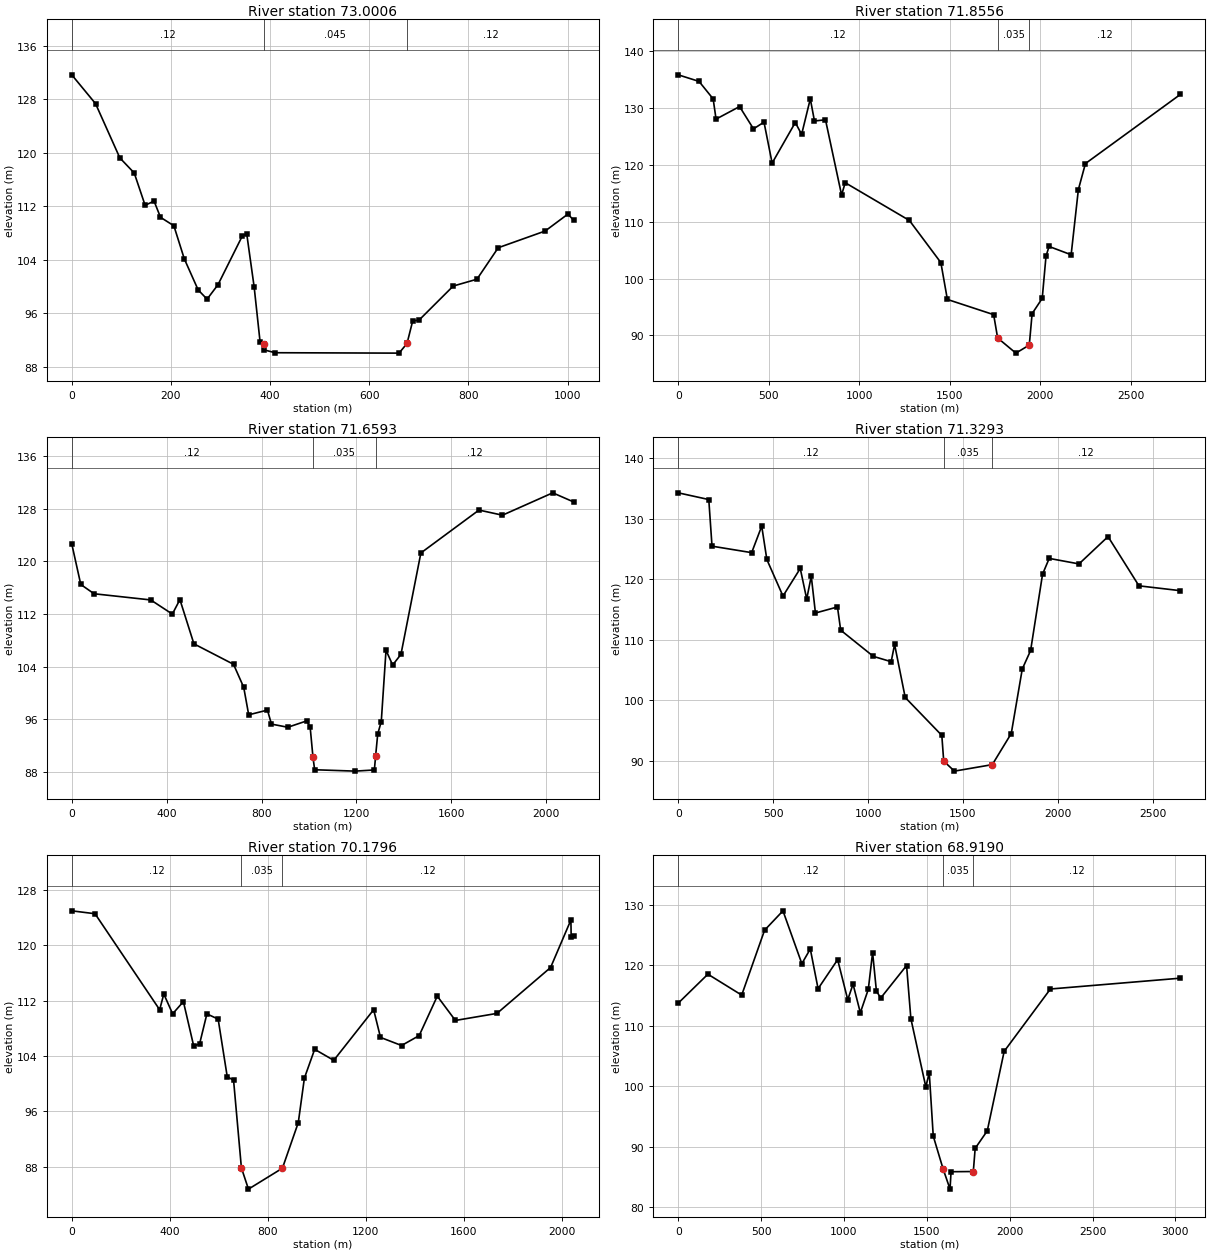
Type RM Length L Ch R = 1 ,73.0006 ,1076.97,1144.98,1214.22
BEGIN DESCRIPTION:
E09B (SEM 2019)
END DESCRIPTION:
XS GIS Cut Line= 4
  571981.4229036 5422996.2135831  571591.7780036 5422964.8579831
  571296.6083036 5422912.9663831  570977.4958036 5422869.1992831
#Sta/Elev= 30
       0  131.62   47.99  127.31   96.98  119.21  125.97  116.96  147.96  112.13
  165.96  112.76  178.96  110.34  205.95  109.07  226.94  104.14  254.94   99.49
  272.93   98.11  294.93  100.27  343.92  107.54  352.91  107.87  367.91   99.91
  379.91   91.67  386.82   91.39   387.7    91.4  387.72   90.54  410.15   90.11
  660.17   90.05  676.24    91.5  687.61   94.85  700.58   94.99  769.38  100.07
  817.25  101.09  860.13  105.79  954.86  108.29 1000.74  110.82  1012.7  109.87
#Mann= 3 , 0 , 0
       0     .12       0  386.82    .045       0  676.24     .12       0
Bank Sta=386.82,676.24
XS Rating Curve= 0 ,0
Exp/Cntr=0.3,0.1

Type RM Length L Ch R = 1 ,71.8556 ,164.11,196.22,231.02
BEGIN DESCRIPTION:
E08 (SEM 2016)
END DESCRIPTION:
XS GIS Cut Line= 5
      572890.448    5422967.5517     572211.0016    5422911.2256
     571793.4817    5421950.9283     571597.8655    5421698.6239
     571080.2523    5421189.5033
#Sta/Elev= 30
       0  135.89  114.96  134.73  192.94  131.65  208.93  128.09  338.89   130.3
  415.86  126.37  473.84  127.56  518.83  120.34  646.79  127.49  681.78   125.4
  729.74  131.66  752.72  127.76  813.67  127.97  902.59  114.72  922.57  116.89
 1277.28  110.24 1451.13  102.82  1487.1   96.33 1742.87   93.65 1764.81   89.55
1865.562  86.8731939.715  88.291 1955.37   93.83 2011.24   96.52 2032.19  103.98
 2049.16  105.66    2171   104.2 2210.95  115.68  2249.9  120.26 2774.24  132.43
#Mann= 3 , 0 , 0
       0     .12       0 1764.81    .035       01939.715     .12       0
Bank Sta=1764.81,1939.715
XS Rating Curve= 0 ,0
Exp/Cntr=0.3,0.1

Type RM Length L Ch R = 1 ,71.6593 ,257.38,330,391.14
BEGIN DESCRIPTION:
Big Bend
END DESCRIPTION:
XS GIS Cut Line= 2
      572278.432     5422844.136     571556.4944    5420855.0606
#Sta/Elev= 30
       0  122.64   37.98  116.48   93.96  115.07  332.85  114.13  423.81  111.98
  455.79  114.18  514.77  107.46  681.69  104.35  724.67  100.85  745.66   96.67
  824.63   97.39  841.62   95.26  910.59   94.78  989.55   95.74 1004.54   94.86
 1016.54   90.241023.615  88.321 1194.66  88.1121275.314  88.289 1280.41   90.35
 1289.41   93.75  1304.4   95.64 1324.39  106.48 1352.38  104.24 1387.36  105.86
 1471.32  121.27 1716.21  127.79 1815.16  127.01 2027.06  130.41 2116.02  129.01
#Mann= 3 , 0 , 0
       0     .12       0 1016.54    .035       0 1280.41     .12       0
Bank Sta=1016.54,1280.41
XS Rating Curve= 0 ,0
Exp/Cntr=0.3,0.1

Type RM Length L Ch R = 1 ,71.3293 ,1243.56,1149.72,1068.21
XS GIS Cut Line= 5
     572859.0535    5422842.6539      572355.154    5422812.5964
      572191.412    5422188.7616     572175.6477    5421979.5641
     572374.8963    5420709.7282
#Sta/Elev= 30
       0  134.29  160.93  133.18  177.93  125.48  386.84  124.41  439.82  128.79
  466.81  123.28  551.79  117.24  642.79   121.8  676.79  116.75  700.79  120.52
  722.79  114.44  838.78  115.44  855.78  111.61 1027.78  107.28 1121.77   106.4
 1139.77  109.25 1195.73  100.49 1388.55   94.23 1398.55   89.981455.007  88.327
 1654.43    89.4 1754.38   94.54 1812.36  105.19 1856.34  108.25 1919.31  120.86
 1954.29  123.46 2111.22  122.55 2264.15  127.06 2427.07  118.93 2644.96  118.13
#Mann= 3 , 0 , 0
       0     .12       0 1398.55    .035       0 1654.43     .12       0
Bank Sta=1398.55,1654.43
XS Rating Curve= 0 ,0
Exp/Cntr=0.3,0.1

Type RM Length L Ch R = 1 ,70.1796 ,1269.27,1260.6,1315.59
BEGIN DESCRIPTION:
E07 (SEM 2016)
END DESCRIPTION:
XS GIS Cut Line= 4
     573691.1426    5422511.2103     573390.1526    5421927.6832
     573210.4127     5421675.058     572790.1226    5420676.8785
#Sta/Elev= 30
       0  124.99   94.94  124.57  358.77   110.7  375.76  112.97  411.74  110.11
  455.71  111.87  497.68  105.47  521.67  105.74  551.65   110.1  597.62  109.34
   634.6  101.04  660.57   100.5  692.47   87.86 721.284  84.778  859.95    87.8
  924.75   94.39  949.68  100.82   991.6  104.98 1069.53  103.39  1232.4   110.7
 1260.37   106.7  1346.3  105.53 1418.24  106.96 1492.18  112.66 1566.11  109.15
 1735.97  110.17 1954.78   116.8 2037.71  123.67 2038.71  121.28  2049.7  121.32
#Mann= 3 , 0 , 0
       0     .12       0  692.47    .035       0  859.95     .12       0
Bank Sta=692.47,859.95
XS Rating Curve= 0 ,0
Exp/Cntr=0.3,0.1

Type RM Length L Ch R = 1 ,68.9190 ,525.28,519.92,543.7
BEGIN DESCRIPTION:
Badger Steps
END DESCRIPTION:
XS GIS Cut Line= 2
     574699.0246    5422911.6882     574190.5566    5419924.8625
#Sta/Elev= 30
       0  113.76  178.99  118.55  382.97  115.09  520.96  125.82  631.96  129.03
  745.95  120.29  796.95  122.72  843.94  116.15  961.94  120.95 1022.93  114.33
 1054.93   116.9 1098.93  112.18 1146.93  116.04 1172.93  122.13 1195.92  115.77
 1221.92  114.61 1377.91  119.98 1403.91  111.19 1493.91   99.93  1514.9  102.22
  1538.9   91.78  1597.9   86.381640.236      831646.337  85.879  1780.7  85.912
 1791.89   89.74 1864.88   92.64 1966.88  105.79 2245.87   116.1 3029.87  117.89
#Mann= 3 , 0 , 0
       0     .12       0  1597.9    .035       0  1780.7     .12       0
Bank Sta=1597.9,1780.7
XS Rating Curve= 0 ,0
Exp/Cntr=0.3,0.1