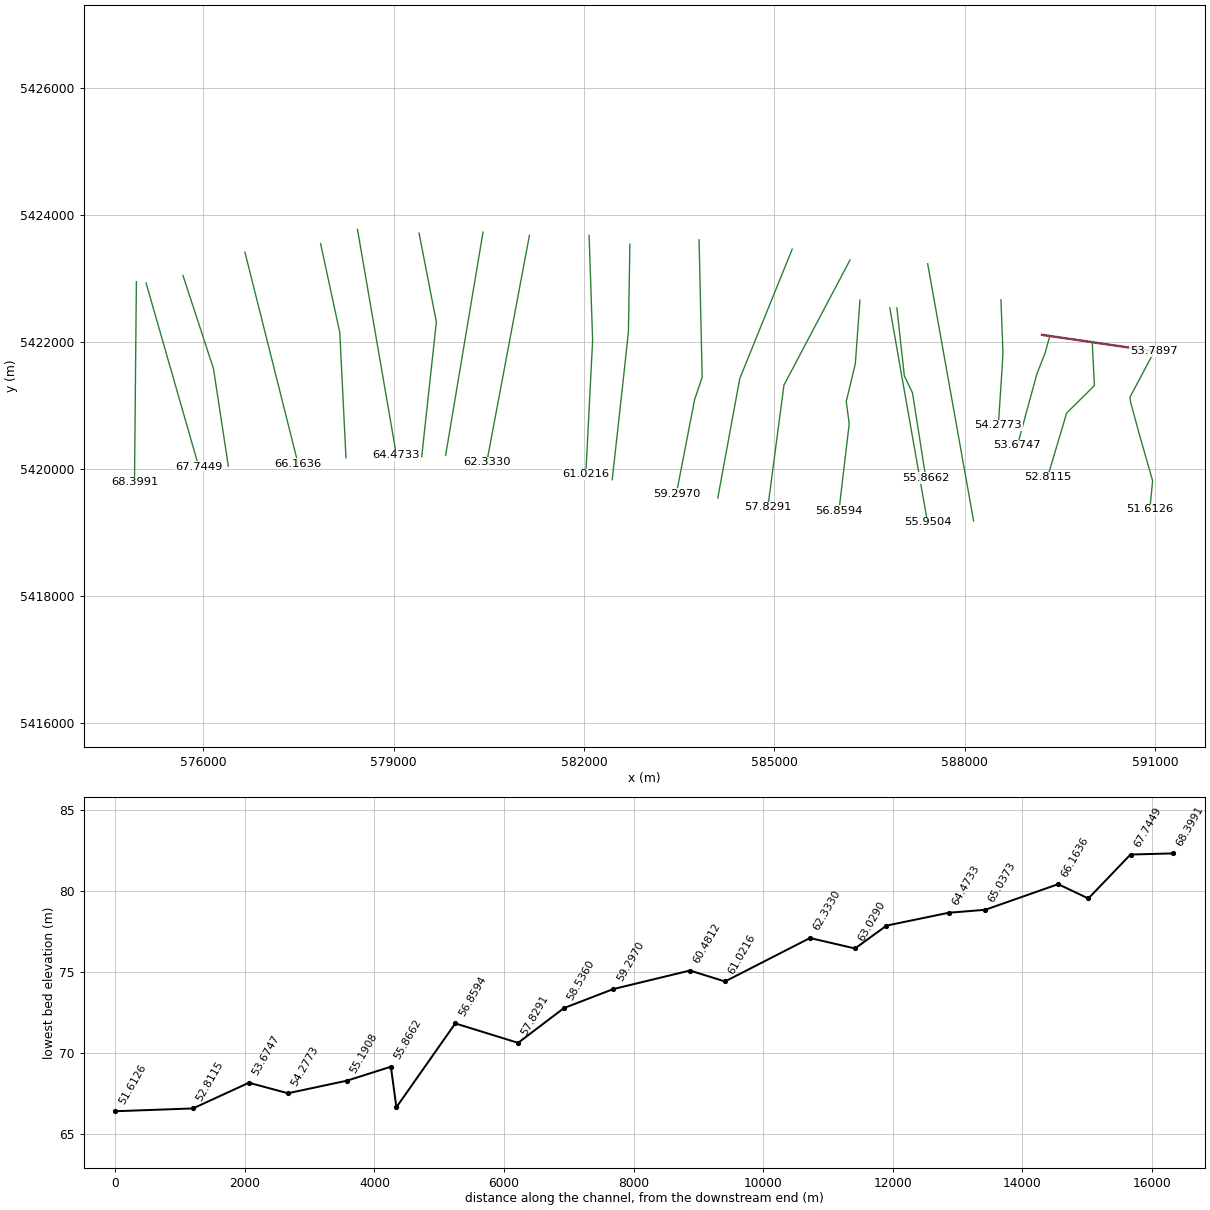
HEC-RAS study Unsteady_RAS.prj: Unsteady_RAS

--- Unsteady_RAS.g01 (geometry) --- (continued)

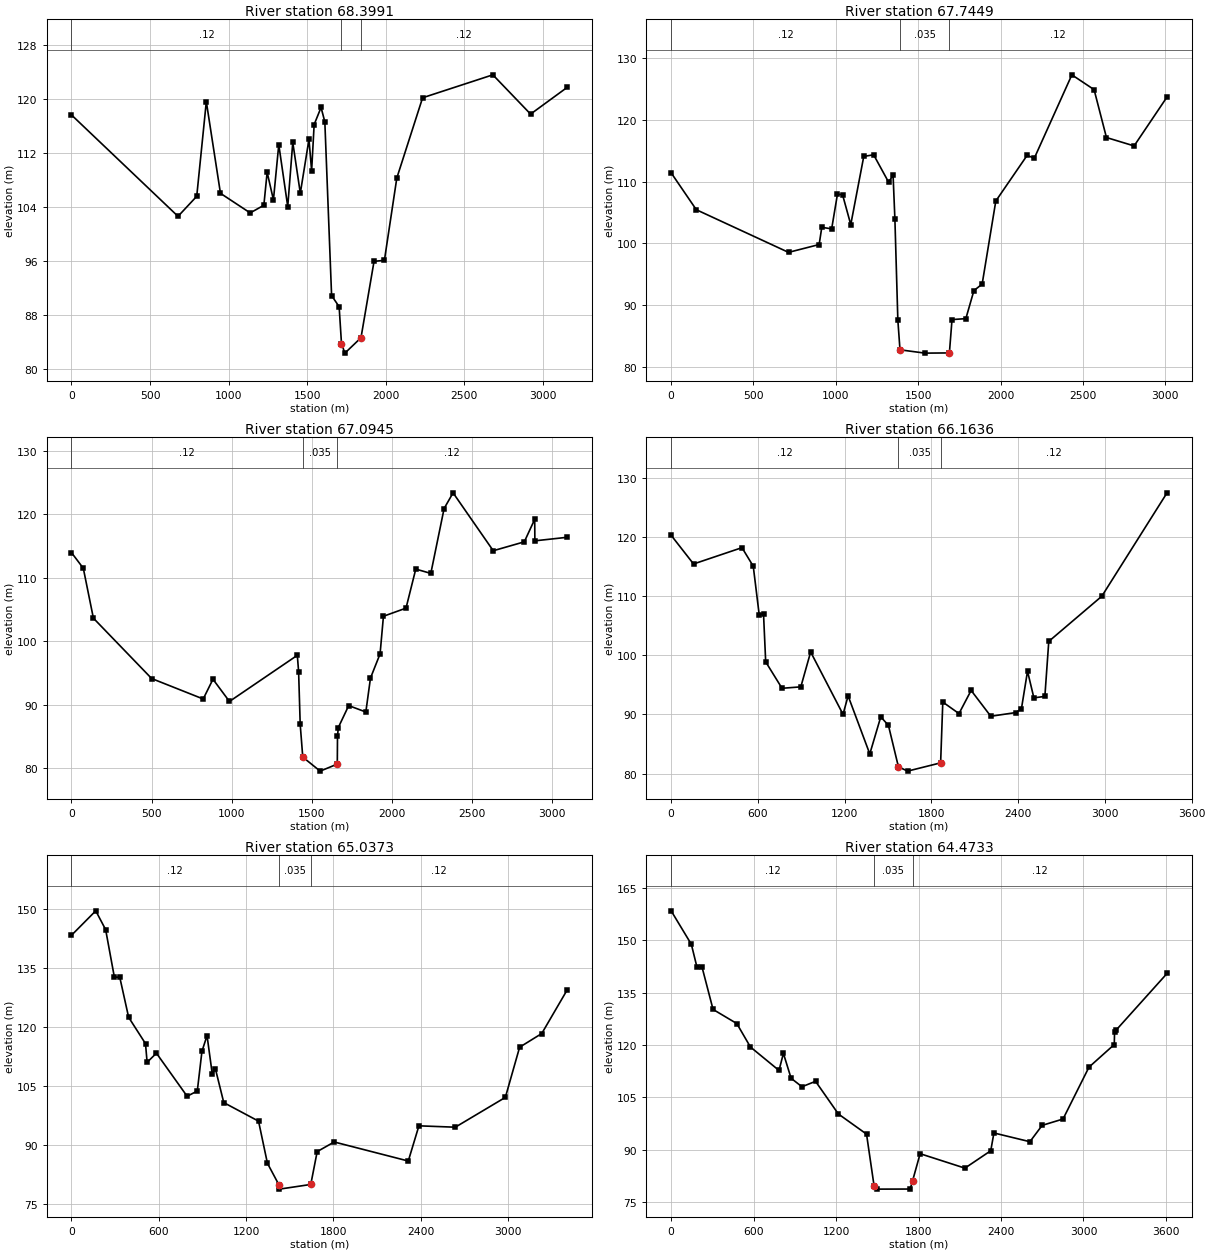
Type RM Length L Ch R = 1 ,68.3991 ,676.24,654.22,709.3
BEGIN DESCRIPTION:
US of Badger Chute
END DESCRIPTION:
XS GIS Cut Line= 2
     574948.2277    5422946.8436      574918.638    5419792.2236
#Sta/Elev= 30
       0   117.6  677.95  102.57  796.94  105.54  857.93  119.57  947.92  105.98
 1136.91  103.08 1223.91  104.21 1244.91   109.1 1284.91  105.01 1318.91   113.2
 1375.91  104.02 1407.91  113.53  1455.9     106  1510.9  113.97  1527.9  109.33
  1543.9  116.17  1587.9  118.71  1611.9  116.57  1654.9   90.83  1702.9   89.18
  1717.9    83.71739.532  82.301  1841.9   84.58 1924.89    95.9 1990.89   96.05
 2069.89  108.25 2233.88  120.14 2680.86  123.54 2920.85  117.72 3154.83   121.7
#Mann= 3 , 0 , 0
       0     .12       0  1717.9    .035       0  1841.9     .12       0
Bank Sta=1717.9,1841.9
XS Rating Curve= 0 ,0
Exp/Cntr=0.3,0.1

Type RM Length L Ch R = 1 ,67.7449 ,659.1,650.38,634.16
BEGIN DESCRIPTION:
DS of Badger Chute
END DESCRIPTION:
XS GIS Cut Line= 2
      575100.847    5422928.5356      575931.311     5420034.117
#Sta/Elev= 30
       0  111.45  152.96  105.47  712.81   98.56  898.76   99.83  914.76  102.62
  974.74  102.37 1009.73  107.97 1040.72  107.92 1090.71  103.06 1169.69  114.11
 1229.67  114.37 1320.65  109.93 1347.64  111.08 1358.64  104.01 1376.63   87.58
 1389.63   82.771541.071  82.232 1689.62  82.265 1705.54   87.67 1789.51   87.82
  1838.5   92.37 1888.49   93.41 1971.46  106.88 2161.41  114.27  2205.4  113.83
 2433.35  127.33 2568.31  124.93  2643.3  117.17 2811.25  115.81 3011.21  123.74
#Mann= 3 , 0 , 0
       0     .12       0 1389.63    .035       0 1689.62     .12       0
Bank Sta=1389.63,1689.62
XS Rating Curve= 0 ,0
Exp/Cntr=0.3,0.1

Type RM Length L Ch R = 1 ,67.0945 ,472.36,465.46,477.99
BEGIN DESCRIPTION:
E06 (SEM 2016)
END DESCRIPTION:
XS GIS Cut Line= 3
     575682.1108    5423045.9982     576162.6004    5421580.1626
     576397.1762    5420043.3932
#Sta/Elev= 30
       0  113.94   73.98  111.47  136.96  103.61  500.86    94.1  822.78   90.88
  883.76   93.99  986.74   90.49 1410.63   97.76 1418.63    95.2 1428.62   86.88
 1444.62   81.731553.255  79.5181660.277  80.627 1661.56   84.98 1666.56   86.38
 1731.54   89.84 1838.51   88.83 1867.51   94.17 1927.49   97.99 1948.48  103.91
 2089.45  105.19 2150.43  111.34 2244.41  110.66 2327.39  120.88 2383.37  123.35
 2634.31  114.23 2828.27  115.63 2893.25  119.18 2894.25  115.79  3097.2  116.35
#Mann= 3 , 0 , 0
       0     .12       0 1444.62    .035       01660.277     .12       0
Bank Sta=1444.62,1660.277
XS Rating Curve= 0 ,0
Exp/Cntr=0.3,0.1

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
Type RM Length L Ch R = 1 ,66.1636 ,1153.47,1126.29,1103.46
XS GIS Cut Line= 2
     576658.9118    5423411.2624     577495.0612    5420085.1708
#Sta/Elev= 30
       0  120.28  154.98  115.43  489.94  118.19  567.93  115.05  608.93  106.87
  638.92     107  653.92   98.88  766.91   94.41  896.89   94.65  964.88  100.55
 1188.86      90 1223.85   93.13 1373.84   83.31 1449.83   89.58 1502.82   88.14
 1571.81   81.141635.287  80.402 1863.78    81.8 1878.78   92.08 1990.77   90.13
 2074.76   94.05 2210.75   89.68 2384.74   90.31 2422.74   90.96 2464.74    97.3
 2508.73   92.79 2584.73   93.04 2611.73  102.34 2978.71  109.98 3429.68  127.46
#Mann= 3 , 0 , 0
       0     .12       0 1571.81    .035       0 1863.78     .12       0
Bank Sta=1571.81,1863.78
XS Rating Curve= 0 ,0
Exp/Cntr=0.3,0.1

Type RM Length L Ch R = 1 ,65.0373 ,579.16,563.96,579.4
XS GIS Cut Line= 3
     577850.7352    5423548.8564     578153.6456    5422145.8768
     578250.6771    5420176.3831
#Sta/Elev= 30
       0  143.42  166.92  149.65  234.89  144.86  294.86  132.76  331.84  132.76
  392.81  122.55  508.75  115.85  519.75  111.09  583.72  113.42  794.62  102.46
  864.58  103.78  896.57   113.9  931.55  117.89  967.53   108.1  988.52  109.52
 1046.49  100.84 1285.38   96.12 1346.35   85.41 1426.31   79.851429.314  78.819
 1644.29   80.01 1688.28   88.37 1805.27   90.82 2314.25   85.97 2387.25   94.93
 2637.25   94.58 2981.25  102.17 3079.25  114.94 3231.25  118.42 3407.25   129.6
#Mann= 3 , 0 , 0
       0     .12       0 1426.31    .035       0 1644.29     .12       0
Bank Sta=1426.31,1644.29
XS Rating Curve= 0 ,0
Exp/Cntr=0.3,0.1

Type RM Length L Ch R = 1 ,64.4733 ,1020.3,959.34,922.2
XS GIS Cut Line= 2
     578431.9292     5423771.109     579045.9247    5420215.2077
#Sta/Elev= 30
       0  158.49  146.98  148.89  187.98  142.32  224.97  142.32  304.96   130.2
  477.94  126.14  576.92  119.42   784.9  112.69  816.89  117.59  872.88  110.45
  951.87  108.01 1050.86  109.57 1216.84   100.2 1421.81   94.42  1476.8   79.54
1496.196  78.6361739.216   78.66 1756.48   80.97 1811.75    88.8 2137.71   84.66
 2325.67   89.65 2348.67   94.75 2610.62   92.24  2699.6   96.93 2851.58   98.75
 3040.54  113.64 3224.51  120.13 3226.51   123.6  3238.5  124.29 3608.44  140.52
#Mann= 3 , 0 , 0
       0     .12       0  1476.8    .035       0 1756.48     .12       0
Bank Sta=1476.8,1756.48
XS Rating Curve= 0 ,0
Exp/Cntr=0.3,0.1

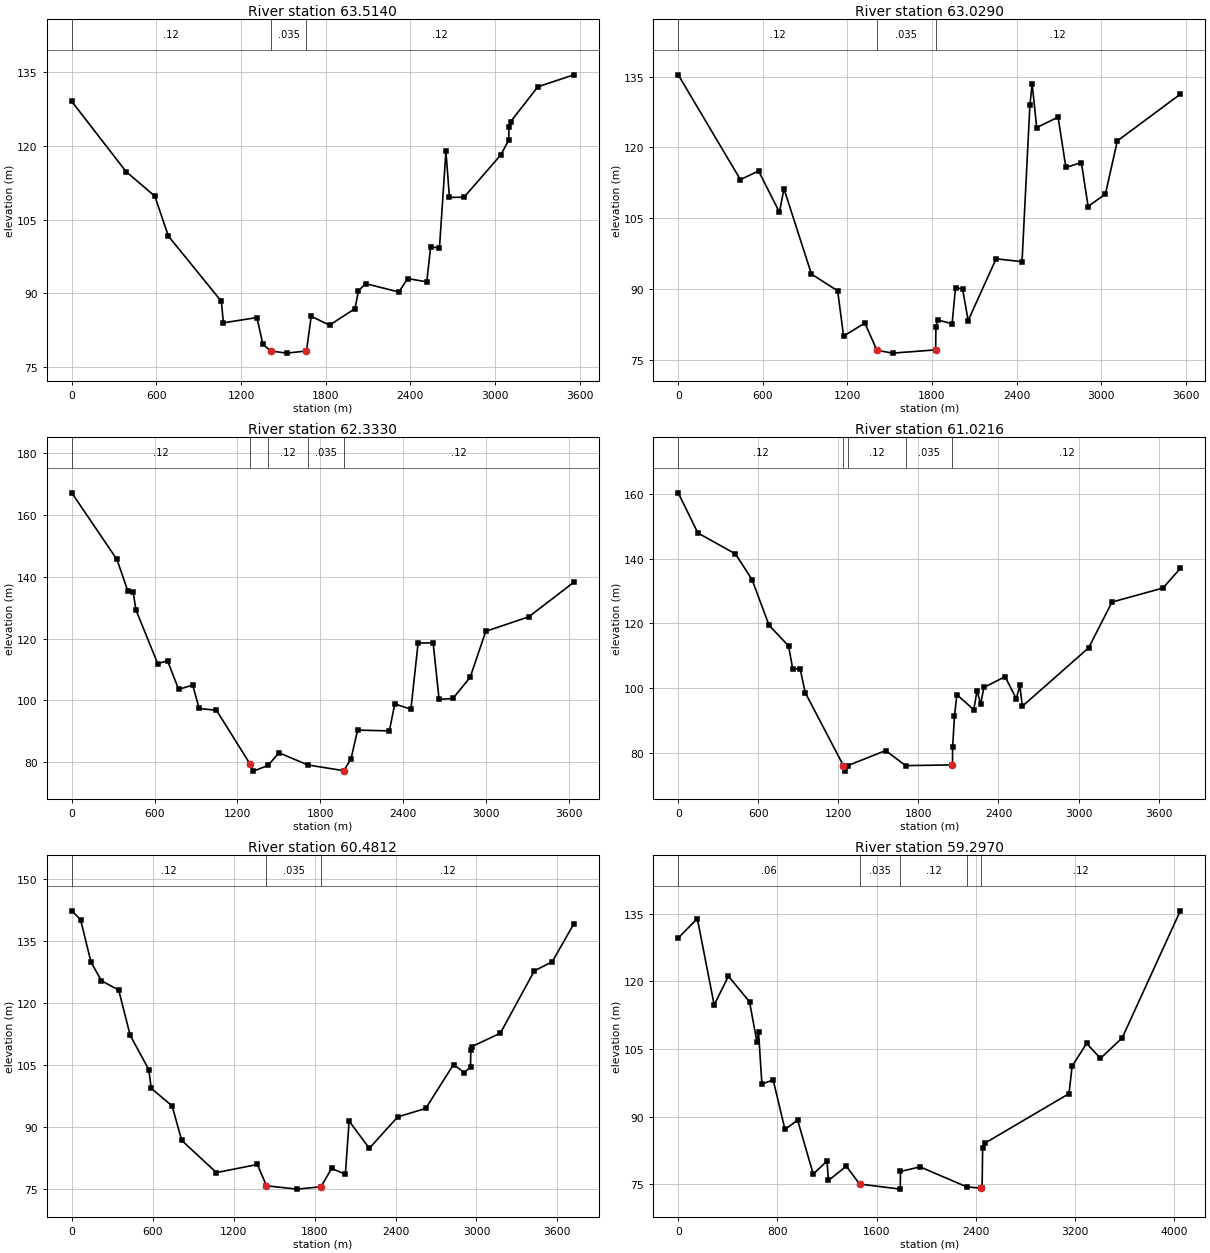
Type RM Length L Ch R = 1 ,63.5140 ,518.04,485.01,483.45
XS GIS Cut Line= 3
     579402.8627    5423711.5121     579675.1115    5422311.5935
     579444.1086    5420192.0882
#Sta/Elev= 30
       0  129.02  384.77  114.76  588.65  109.76  684.59  101.65 1060.37   88.37
 1074.36      84 1312.22   85.08  1354.2   79.65 1409.16   78.281524.708  77.842
 1663.05   78.28 1697.05   85.33 1826.99   83.53 2006.92   86.88 2031.91    90.5
 2081.89   91.98 2317.77   90.27 2380.74      93 2515.68   92.34 2543.66   99.51
 2605.63   99.17 2651.61  118.86  2676.6   109.5 2780.55  109.56 3039.42  118.12
 3096.39  121.14 3098.39  123.84 3110.39  124.93 3303.29  132.01 3558.17  134.44
#Mann= 3 , 0 , 0
       0     .12       0 1409.16    .035       0 1663.05     .12       0
Bank Sta=1409.16,1663.05
XS Rating Curve= 0 ,0
Exp/Cntr=0.3,0.1

Type RM Length L Ch R = 1 ,63.0290 ,755.96,695.94,694.78
BEGIN DESCRIPTION:
Aspen Brook - E5 (SEM 2016)
END DESCRIPTION:
XS GIS Cut Line= 2
     580410.2525    5423728.2673     579821.5711    5420215.7853
#Sta/Elev= 30
       0  135.38  440.93  113.18  569.91  115.02  717.89  106.26  749.89  111.26
  944.86   93.17 1130.84   89.63 1172.83   80.04 1323.81    82.81409.275  77.032
1521.065   76.431825.948  77.119 1827.75   81.92 1840.75   83.45 1942.73   82.66
 1966.73   90.32 2016.73   90.01 2056.72   83.34 2254.67   96.41 2438.63    95.8
 2494.61  129.05 2510.61  133.39  2542.6  124.21 2694.56  126.42 2749.55  115.76
 2859.52   116.8 2907.51  107.48 3030.48  110.15 3114.46  121.38 3561.35  131.28
#Mann= 3 , 0 , 0
       0     .12       01409.275    .035       01825.948     .12       0
Bank Sta=1409.275,1825.948
XS Rating Curve= 0 ,0
Exp/Cntr=0.3,0.1

Type RM Length L Ch R = 1 ,62.3330 ,1253.79,1311.45,1390.32
BEGIN DESCRIPTION:
Eleven Mile Island
END DESCRIPTION:
XS GIS Cut Line= 2
     581142.1024     5423679.808     580469.5589    5420106.9591
#Sta/Elev= 30
       0  167.21  326.96  145.63  406.96  135.31  443.95  135.17  464.95  129.27
  621.93  111.92  693.93  112.77  773.92  103.56   875.9  104.95   921.9   97.37
 1047.88   96.78 1291.29   79.351314.603  77.077 1420.85    78.9 1499.85   83.02
 1709.83   79.071969.557  77.221  2021.8   81.03  2069.8   90.36 2299.76   90.11
 2338.75   98.85 2455.73   97.13 2507.72  118.54 2616.71  118.65  2659.7  100.34
 2759.68   100.6 2884.66  107.44 2997.64  122.36 3308.59  127.04 3635.54  138.25
#Mann= 5 ,-1 , 0
       0     .12       0 1291.29    .035       0 1420.85     .12       0
 1709.83    .035       01969.557     .12       0
Bank Sta=1291.29,1969.557
XS Rating Curve= 0 ,0
Exp/Cntr=0.3,0.1

Type RM Length L Ch R = 1 ,61.0216 ,671.66,540.42,542.2
BEGIN DESCRIPTION:
Birchy Island
END DESCRIPTION:
XS GIS Cut Line= 3
     582081.8398    5423675.2493     582137.4241    5422025.1949
      582029.736    5419915.8509
#Sta/Elev= 30
       0  160.27     147  147.89     429  141.41     553   133.5  680.99  119.38
  826.99  113.01  857.99  105.96  913.99   105.9  951.98    98.6 1237.97  76.092
 1250.23  74.392    1270  76.092    1555   80.74    1704  76.092 2055.23   76.31
 2056.84   81.95 2070.25   91.42 2088.82   97.97 2214.76   93.35 2239.75    99.2
 2266.74    95.1 2290.73   100.2 2449.65  103.55 2533.61   96.74 2560.59  100.82
 2578.58   94.39 3076.34  112.47 3251.26  126.57 3633.07  130.89 3763.01  136.94
#Mann= 5 ,-1 , 0
       0     .12       0 1237.97    .035       0    1270     .12       0
    1704    .035       0 2055.23     .12       0
Bank Sta=1237.97,2055.23
XS Rating Curve= 0 ,0
Exp/Cntr=0.3,0.1

Type RM Length L Ch R = 1 ,60.4812 ,1166.61,1184.16,1262.16
BEGIN DESCRIPTION:
Pynns Brook - R01-4 (RIS 2013)
END DESCRIPTION:
XS GIS Cut Line= 4
     582724.4985    5423537.1535     582701.2268    5422160.4112
     582619.4974    5421399.7531     582445.7695    5419829.3542
#Sta/Elev= 30
       0  142.28      65  140.15  142.99  129.85  219.99   125.4  347.98  123.13
  432.98  112.22  570.97  103.94  588.97    99.4  743.97   95.16  814.96   86.85
 1071.95   79.06 1375.95   81.02 1443.51  75.869 1670.51  75.069 1847.51  75.639
 1926.23   80.07  2028.1   78.64 2056.06    91.5 2205.96   84.93 2415.96    92.5
 2623.96   94.56 2829.96  105.15 2908.96  103.23 2955.96   104.5 2957.96  108.72
 2966.96  109.51 3176.96  112.72 3428.96  127.78 3561.96  129.99 3721.96  139.15
#Mann= 3 , 0 , 0
       0     .12       0 1443.51    .035       0 1847.51     .12       0
Bank Sta=1443.51,1847.51
XS Rating Curve= 0 ,0
Exp/Cntr=0.3,0.1

Type RM Length L Ch R = 1 ,59.2970 ,979.8,761.02,633.52
BEGIN DESCRIPTION:
E03 (SEM 2016)
END DESCRIPTION:
XS GIS Cut Line= 4
     583814.6901    5423607.0587     583863.4829    5421443.8945
     583744.1773    5421090.8812     583455.9395    5419604.8838
#Sta/Elev= 30
       0  129.59  153.98  133.91  289.96  114.75  404.95  121.14  574.92  115.46
  634.92  106.57  647.92  108.68  674.91   97.24   765.9   98.12  860.89   87.15
  962.88   89.23 1088.87   77.26 1199.85   80.14 1211.85   75.84 1355.84   79.01
 1462.83   75.05 1790.73  73.923 1792.73  77.844 1950.78   78.862326.511  74.431
 2444.03  74.1242451.081  74.134 2455.46   83.06 2476.44   84.16 3152.23   95.09
 3177.23  101.17  3294.2  106.24 3406.17  102.91 3581.13  107.45 4050.02  135.62
#Mann= 5 ,-1 , 0
       0     .06       0 1462.83    .035       0 1790.73     .12       0
2326.511    .035       0 2444.03     .12       0
Bank Sta=1462.83,2444.03
XS Rating Curve= 0 ,0
Exp/Cntr=0.3,0.1

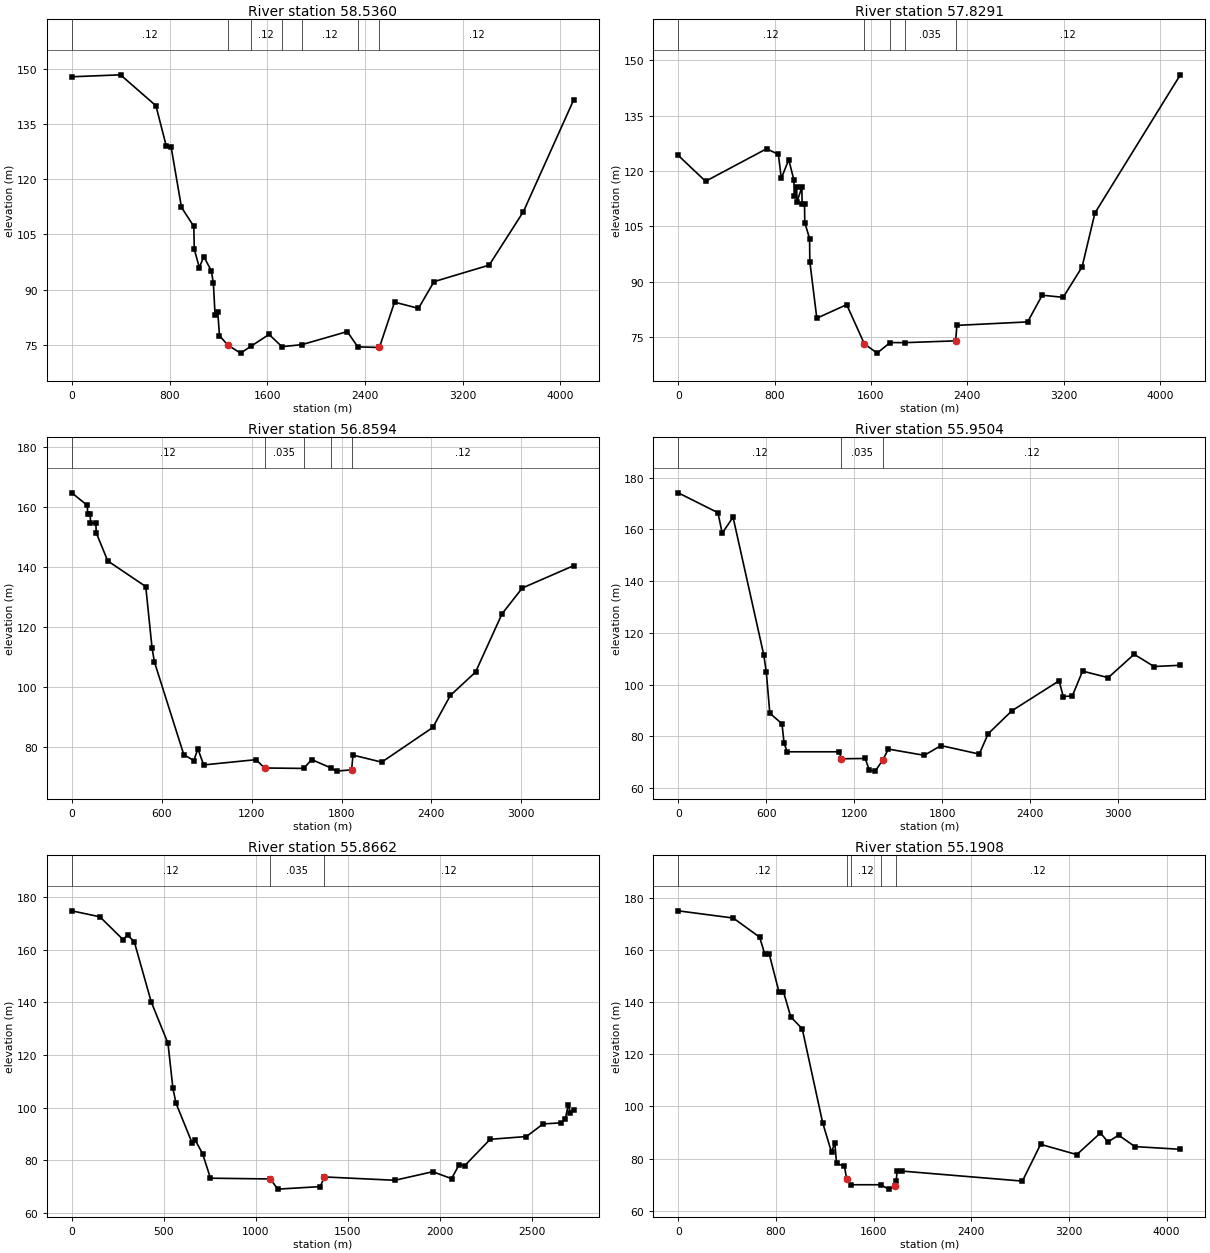
Type RM Length L Ch R = 1 ,58.5360 ,778.24,706.92,773.22
BEGIN DESCRIPTION:
Battle Island
END DESCRIPTION:
XS GIS Cut Line= 3
     585282.3343    5423460.4551     584455.8221    5421422.9078
     584109.7545     5419544.069
#Sta/Elev= 30
       0  147.85  398.96  148.38  688.94  139.98  773.93  128.94  812.92  128.81
  897.91  112.36   998.9   107.2  1002.9  100.96  1043.9      96  1080.9   98.98
 1141.89   95.13 1158.89   91.81 1172.89   83.07 1194.89   83.98 1208.89    77.5
 1276.65   74.94 1381.78  72.749 1464.87  74.589 1614.86   77.83 1719.85  74.509
 1881.84  75.039  2254.8    78.6 2340.78  74.449 2517.74  74.279  2641.7    86.6
 2837.66   84.92 2964.62   92.17 3416.51   96.67 3696.44   111.2 4109.33  141.67
#Mann= 7 ,-1 , 0
       0     .12       0 1276.65    .035       0 1464.87     .12       0
 1719.85    .035       0 1881.84     .12       0 2340.78    .035       0
 2517.74     .12       0
Bank Sta=1276.65,2517.74
XS Rating Curve= 0 ,0
Exp/Cntr=0.3,0.1

Type RM Length L Ch R = 1 ,57.8291 ,930.24,969.66,1225.68
BEGIN DESCRIPTION:
Goat Island
END DESCRIPTION:
XS GIS Cut Line= 3
     586192.7393    5423289.1602     585151.9929    5421319.9013
     584897.9609    5419394.8639
#Sta/Elev= 30
       0  124.23  226.93  117.21  733.79  126.03  831.76   124.5  855.76     118
  917.74  123.07  960.73   117.5  962.73   113.3  983.72  115.67  985.72  111.64
 1026.71  115.57 1028.71  111.06  1048.7  110.94  1050.7  106.01 1090.69  101.67
 1092.69   95.44 1150.67   80.07  1398.6   83.75 1545.56  73.123 1651.57  70.603
  1759.5  73.473 1880.47  73.443 2303.37  73.933 2314.04   78.13 2901.32   79.07
 3022.31   86.31 3196.29   85.73 3353.28   93.95 3460.27  108.61 4169.22  146.08
#Mann= 5 ,-1 , 0
       0     .12       0 1545.56    .035       0  1759.5     .12       0
 1880.47    .035       0 2303.37     .12       0
Bank Sta=1545.56,2303.37
XS Rating Curve= 0 ,0
Exp/Cntr=0.3,0.1

Type RM Length L Ch R = 1 ,56.8594 ,819.34,908.98,958.08
BEGIN DESCRIPTION:
Thunder Brook - E02 (SEM 2016)
END DESCRIPTION:
XS GIS Cut Line= 5
     586349.3738    5422656.9258      586276.459    5421653.3112
     586133.4544    5421061.4803     586180.4051    5420710.2453
     586017.8521    5419338.9116
#Sta/Elev= 30
       0  164.68  103.92  160.48  105.92  157.75  122.91  157.75  124.91   154.6
  160.88   154.6  162.88   151.4  239.82  141.97  493.64   133.4  535.61  112.97
   551.6  108.23  747.45   77.31   814.4   75.32  841.38   79.24  880.35   73.87
  1229.2   75.63 1286.19   72.851548.027  72.707 1601.12   75.66  1728.9   72.88
 1766.77  71.8031867.491  72.243 1876.63   77.15 2068.46    74.8 2409.46   86.38
 2526.46   97.06 2694.46  104.86 2871.46  124.32 3006.46  132.91 3350.46   140.4
#Mann= 5 ,-1 , 0
       0     .12       0 1286.19    .035       01548.027     .12       0
  1728.9    .035       01867.491     .12       0
Bank Sta=1286.19,1867.491
XS Rating Curve= 0 ,0
Exp/Cntr=0.3,0.1

Type RM Length L Ch R = 1 ,55.9504 ,41.4,84.29,123.64
BEGIN DESCRIPTION:
R01-2 (RIS 2013)
END DESCRIPTION:
XS GIS Cut Line= 2
     586819.9917    5422533.2567     587414.3375    5419159.4375
#Sta/Elev= 30
       0  174.13  270.98  166.44  299.98  158.54  373.98  164.73  583.96  111.43
  600.96   104.8  624.96   88.99  707.95   84.92  721.95   77.55  742.95   74.09
 1098.92   74.09 1111.92    71.4 1275.92   71.51 1304.08  66.922 1344.08  66.622
 1394.08  70.802 1433.91   75.13  1678.9   72.73  1792.9   76.49 2053.89   73.21
 2114.88   81.07 2276.87   89.95 2598.85  101.52 2626.84   95.44 2688.84   95.66
 2758.83  105.26 2933.82  102.73 3110.81  111.76  3246.8  107.03 3425.78  107.51
#Mann= 3 , 0 , 0
       0     .12       0 1111.92    .035       0 1394.08     .12       0
Bank Sta=1111.92,1394.08
XS Rating Curve= 0 ,0
Exp/Cntr=0.3,0.1

Type RM Length L Ch R = 1 ,55.8662 ,754.02,675.34,619.94
BEGIN DESCRIPTION:
R01-2A (SEM 2019)
END DESCRIPTION:
XS GIS Cut Line= 4
     586931.2706    5422533.6877      587049.015     5421464.552
      587177.982     5421196.347     587387.1347    5419857.1359
#Sta/Elev= 30
       0  174.75  152.94  172.48   279.9  163.75  302.89  165.63  339.87  162.96
  431.84  140.18   522.8  124.47   549.8  107.36  566.79  101.67  653.76   86.71
  671.75   87.59  710.74   82.62  753.72   73.28 1078.41   72.99 1120.13   69.13
 1351.01   70.09  1372.1   73.76 1756.05   72.49 1961.96   75.74 2063.92   73.11
  2105.9   78.46 2134.89   77.98 2273.83   88.04 2470.74   89.09  2561.7   93.88
 2659.66   94.28 2682.65   95.92 2698.64  101.24 2709.63   98.06 2728.63   99.12
#Mann= 3 , 0 , 0
       0     .12       0 1078.41    .035       0  1372.1     .12       0
Bank Sta=1078.41,1372.1
XS Rating Curve= 0 ,0
Exp/Cntr=0.3,0.1

Type RM Length L Ch R = 1 ,55.1908 ,985.84,913.54,892.36
BEGIN DESCRIPTION:
R01-2B (SEM 2019)
END DESCRIPTION:
XS GIS Cut Line= 2
     587416.6398    5423229.7524     588140.4092    5419180.8428
#Sta/Elev= 30
       0  174.95   450.9  172.18  666.85  164.85  707.85   158.5  744.84   158.5
  824.82  143.97  861.81  143.97   921.8  134.31 1015.78  129.72 1182.74    93.8
 1255.72   82.39 1282.72   86.13 1296.71   78.12  1361.7   77.02 1380.16   72.11
  1416.8   69.95 1658.29   69.95 1724.04   68.27 1776.16   69.44 1785.85   71.28
 1792.59   75.12 1833.58   75.18 2819.34   71.35  2968.3   85.44 3265.23   81.51
 3459.18   89.81 3520.17   86.34 3607.15   88.97 3741.12   84.57 4113.03   83.54
#Mann= 5 ,-1 , 0
       0     .12       0 1380.16    .035       0  1416.8     .12       0
 1658.29    .035       0 1785.85     .12       0
Bank Sta=1380.16,1776.16
XS Rating Curve= 0 ,0
Exp/Cntr=0.3,0.1

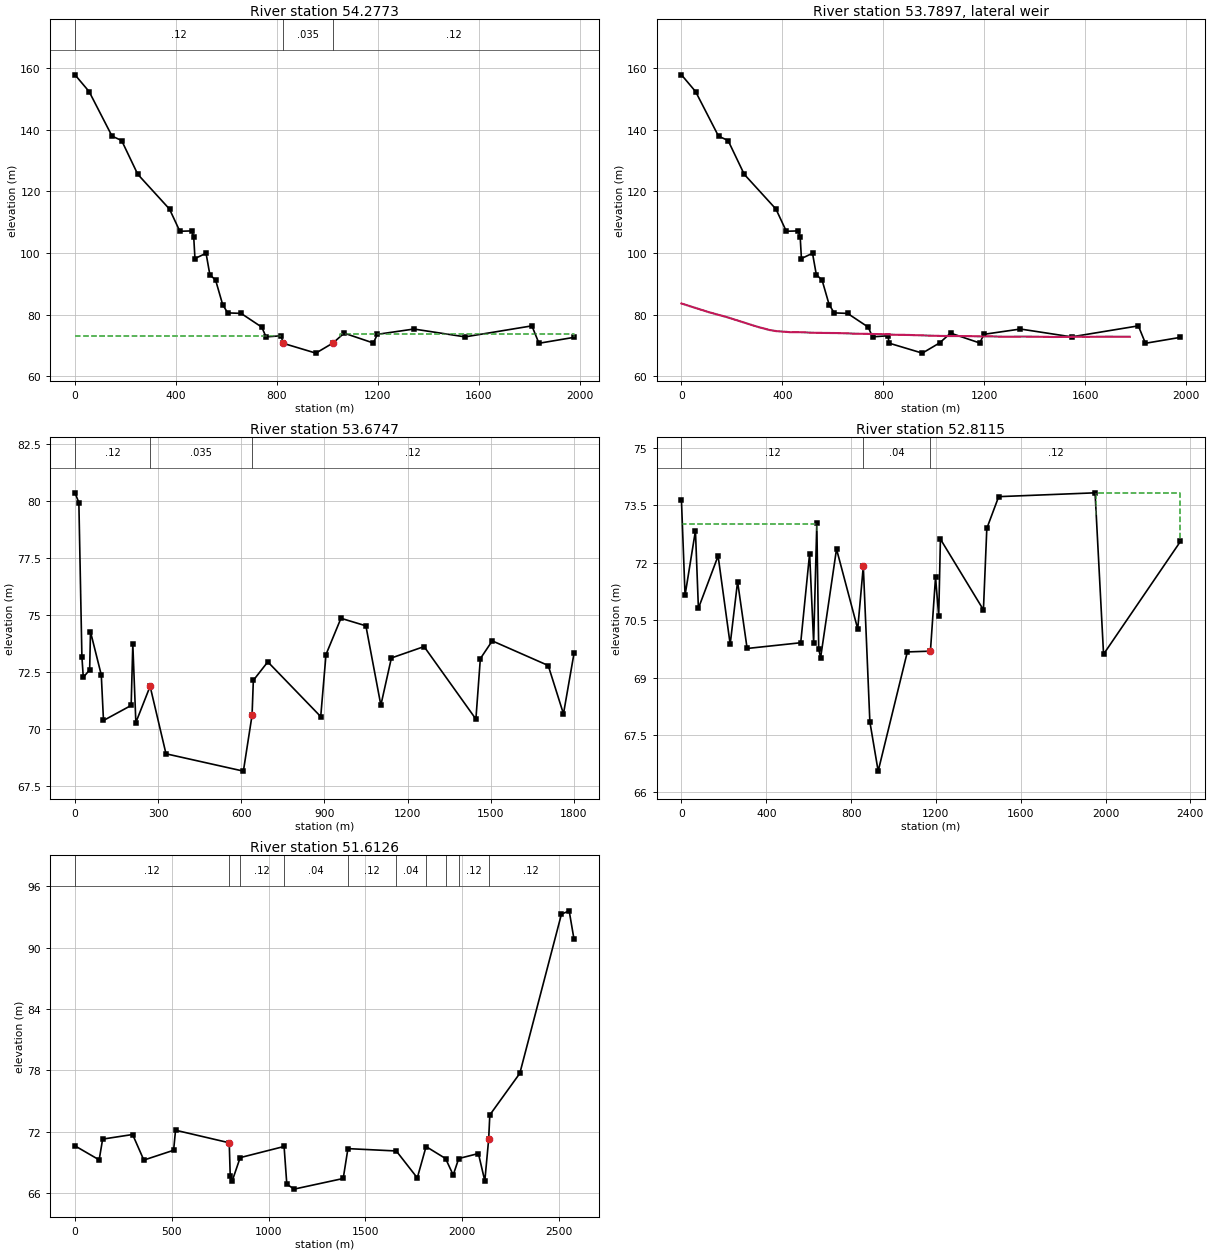
Type RM Length L Ch R = 1 ,54.2773 ,718.29,602.57,567.43
BEGIN DESCRIPTION:
02YO018 ER at CE Point - R01-1A (SEM 2019)
END DESCRIPTION:
XS GIS Cut Line= 4
  588571.1252036 5422661.0690831  588602.4900036 5421843.4389831
  588592.1690036 5421632.1959831  588530.0358036 5420685.9466831
#Sta/Elev= 30
       0  157.82   55.95  152.39  146.86  137.92  184.83   136.5  248.77  125.54
  374.65  114.24  415.61  107.04  462.56  107.16  470.56   105.3  475.55   98.19
  519.51    99.9   534.5   92.99  557.48   91.16  585.45   83.21  605.43   80.55
  658.38   80.39   740.3   75.93  757.29   72.77  817.98   73.12  823.78   70.71
  954.77   67.49  1023.2    70.8  1066.7   73.98 1182.61   70.78  1198.6   73.59
  1343.5   75.31 1546.35   72.77 1811.16   76.34 1839.13   70.69 1978.03   72.61
#Mann= 3 , 0 , 0
       0     .12       0  823.78    .035       0  1023.2     .12       0
#XS Ineff= 2 , 0
          817.62   73.12  1050.4           73.83
Permanent Ineff=
       F       F
Bank Sta=823.78,1023.2
XS Rating Curve= 0 ,0
Exp/Cntr=0.3,0.1

Type RM Length L Ch R = 6 ,53.7897 ,,,
BEGIN DESCRIPTION:
TransCanada Highway At Wigwam Brook
END DESCRIPTION:
Lateral Weir Pos= 0
Lateral Weir End=Wigwam Brook    ,Wigwam Brook    ,2.890   ,
Lateral Weir Distance=636.24
Lateral Weir TW Multiple XS=-1
Lateral Weir WD=20
Lateral Weir Coef=1.4
LW OverFlow Method 2D=False
Lateral Weir WSCriteria=-1
Lateral Weir Flap Gates= 0
Lateral Weir Hagers EQN= 0 ,,,,,
Lateral Weir SS=0.05,0.05,
Lateral Weir Type= 0
Lateral Weir Connection Pos and Dist= 3 ,0
Lateral Weir SE= 25
       0  83.602 108.916  80.771 183.858  79.082 298.768  76.096  348.73  74.999
 376.708  74.622 430.666  74.288 463.641  74.303 534.586  74.071 624.518   73.99
 695.486   73.79 803.438  73.629 848.417  73.438 900.388  73.386 1030.25  73.058
1146.126  73.0041189.026  72.8921228.884  72.9191287.675  72.8061358.424  72.877
1476.149  72.7261577.135  72.8161596.133  72.758 1689.12  72.845    1777   72.81
Lateral Weir Centerline= 2
        589217.8       5422110.9      590977.537     5421854.349
LW Div RC= 0 ,False,

Type RM Length L Ch R = 1 ,53.6747 ,998.63,863.18,775.75
BEGIN DESCRIPTION:
R01-1B (SEM 2019)
END DESCRIPTION:
XS GIS Cut Line= 4
  589342.7861036 5422096.9113831  589266.9401036 5421825.8574831
  589136.8050036 5421493.2649831  588830.8615036 5420372.5627831
#Sta/Elev= 30
       0   80.34   13.97   79.91   24.95   73.15   29.94   72.25    52.9   72.58
   55.89   74.25   94.82   72.36   102.8   70.36  202.62   71.02   208.6    73.7
  219.58   70.27     271   71.86   328.3    68.9  607.53   68.14  638.81   70.59
  643.48   72.12   695.6   72.93  886.55   70.53  905.55   73.25  959.54   74.84
 1049.51   74.51  1103.5   71.03 1141.49    73.1 1259.46    73.6 1446.41   70.42
 1462.41   73.07  1505.4   73.85 1707.35   72.77 1762.34   70.65 1800.33    73.3
#Mann= 3 , 0 , 0
       0     .12       0     271    .035       0  638.81     .12       0
Bank Sta=271,638.81
XS Rating Curve= 0 ,0
Exp/Cntr=0.3,0.1

Type RM Length L Ch R = 1 ,52.8115 ,841.86,1198.97,1588.02
BEGIN DESCRIPTION:
R01 (RIS 2013)
END DESCRIPTION:
XS GIS Cut Line= 4
590009.5375035985421996.36948309590043.7653035985421312.90588309
589606.3450035985420879.23928309589305.4740035985419869.97878309
#Sta/Elev= 30
       0   73.63   16.98   71.15   65.93   72.84   79.92   70.81  172.83   72.18
  229.77   69.87  264.74   71.51  309.69   69.76  562.44   69.91   604.4   72.24
  623.38   69.91  638.37   73.03  647.36   69.74  656.35   69.52  731.32   72.36
  831.31   70.27  857.62   71.91888.5699  67.843  927.77  66.553 1065.29   69.67
 1174.18   69.69 1198.28   71.62 1213.28   70.61 1221.28   72.62 1424.17   70.77
 1440.16    72.9 1496.11   73.73 1950.75   73.83 1990.72   69.61 2353.44   72.56
#Mann= 3 , 0 , 0
       0     .12       0  857.62     .04       0 1174.18     .12       0
#XS Ineff= 2 , 0
       0  638.94   73.01 1956.32       0   73.82
Permanent Ineff=
       T       T
Bank Sta=857.62,1174.18
XS Rating Curve= 0 ,0
Exp/Cntr=0.3,0.1

Type RM Length L Ch R = 1 ,51.6126 ,1028.2,878.28,1098.98
BEGIN DESCRIPTION:
Sandy Brook - R01A (SEM 2019)
END DESCRIPTION:
XS GIS Cut Line= 6
  590962.8090036 5421805.0920831  590603.6302036 5421128.4707831
  590615.2180036 5421046.1969831  590760.0000036 5420515.9339831
  590961.0350036 5419812.3059831  590916.9701036 5419367.6498831
#Sta/Elev= 30
       0   70.61  124.84   69.24  142.82   71.27  297.63   71.72  355.56   69.22
  509.36   70.18  519.35   72.14   796.7   70.91  801.82   67.69  811.66   67.16
  853.13   69.46 1079.99   70.55 1094.08   66.87 1131.62   66.38 1385.35   67.42
 1409.79   70.34 1659.55   70.11 1768.01   67.48 1813.39   70.54 1914.14   69.37
 1953.57   67.76 1981.97   69.37 2083.72   69.86  2116.8   67.18 2136.61   71.24
 2142.61   73.63 2297.55    77.7 2512.48   93.26 2552.46   93.59 2577.45   90.82
#Mann= 10 ,-1 , 0
       0     .12       0   796.7     .04       0  853.13     .12       0
 1079.99     .04       0 1409.79     .12       0 1659.55     .04       0
 1813.39     .12       0 1914.14     .04       0 1981.97     .12       0
 2136.61     .12       0
Bank Sta=796.7,2136.61
XS Rating Curve= 0 ,0
Exp/Cntr=0.3,0.1