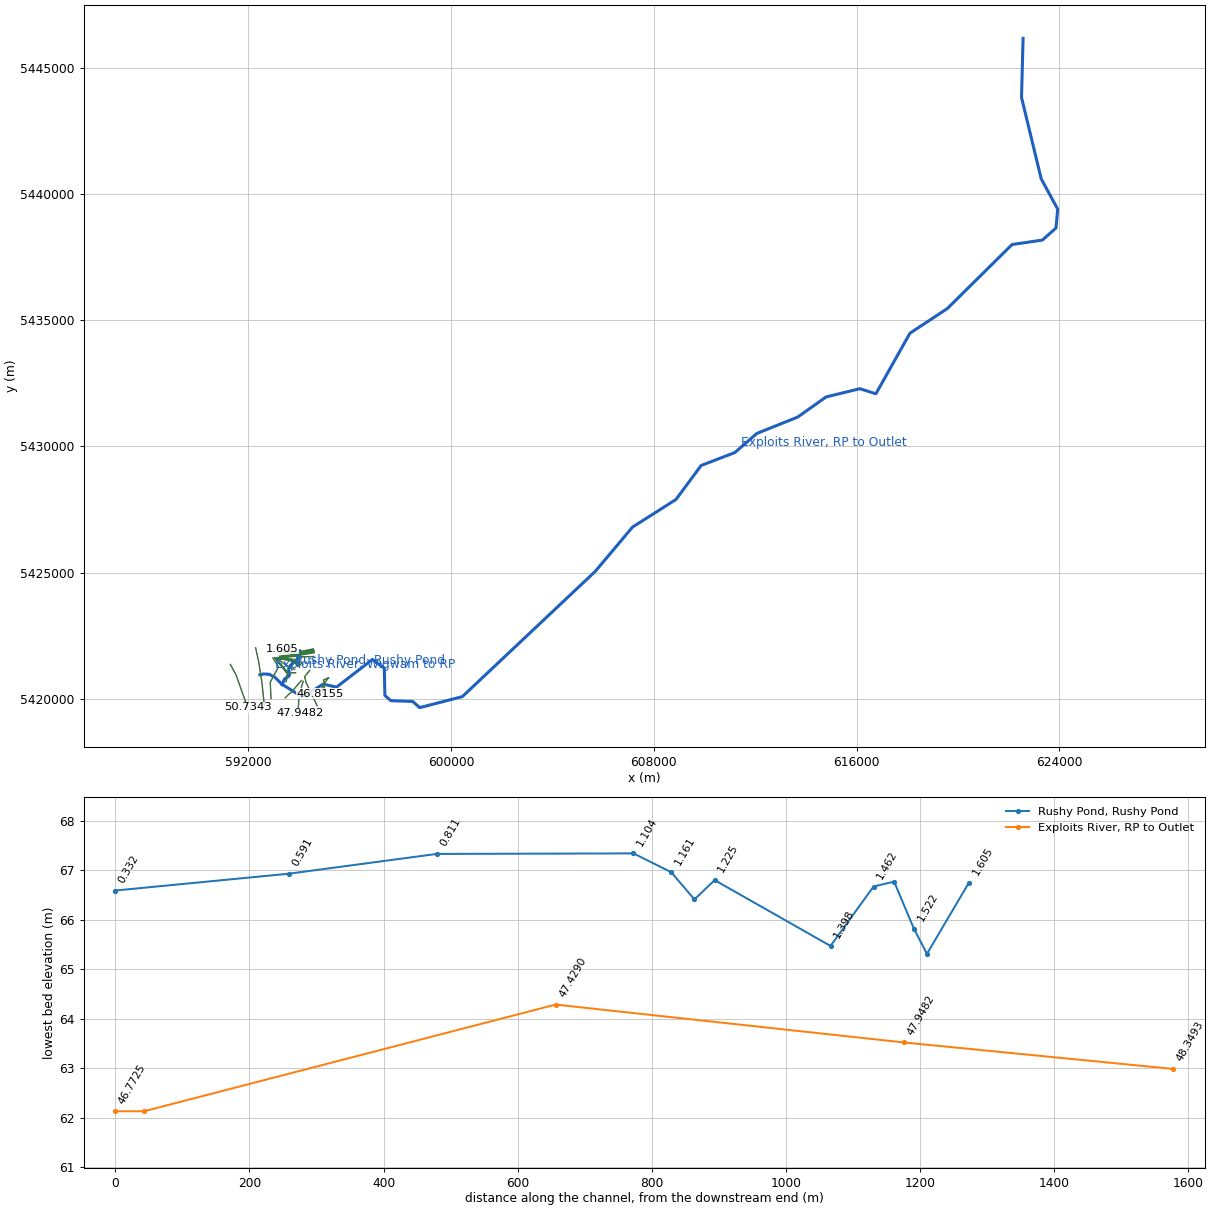
HEC-RAS study Unsteady_RAS.prj: Unsteady_RAS

--- Unsteady_RAS.g01 (geometry) --- (continued)

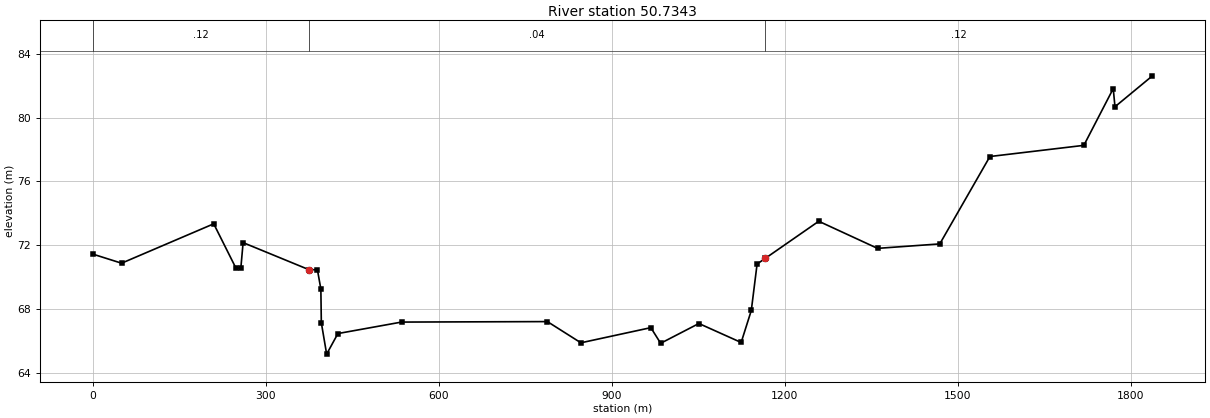
Type RM Length L Ch R = 1 ,50.7343 ,828.8,921.88,912.98
BEGIN DESCRIPTION:
R02 (RIS 2013)
END DESCRIPTION:
XS GIS Cut Line= 3
  591299.6484036 5421361.3682831  591524.8619036 5420941.5243831
  591978.0932036 5419658.0781831
#Sta/Elev= 30
       0   71.44   49.94   70.87  209.75   73.34  247.71    70.6   256.7   70.54
  260.69   72.16  375.13   70.46  389.54   70.46  395.53   69.25  396.33   67.14
405.5601  65.168425.0601  66.458535.3799  67.178788.3501  67.208  846.47  65.878
  967.73  66.828  984.76  65.848 1051.08  67.088 1124.36  65.898 1141.96  67.908
    1152   70.82 1166.08   71.17 1258.93    73.5 1360.87    71.8  1468.8   72.08
 1555.74   77.56 1718.64   78.26  1769.6   81.82  1772.6   80.68 1837.56   82.62
#Mann= 3 , 0 , 0
       0     .12       0  375.13     .04       0 1166.08     .12       0
Bank Sta=375.13,1166.08
XS Rating Curve= 0 ,0
Exp/Cntr=0.3,0.1

River Reach=Exploits River  ,Wigwam to RP
Reach XY= 30
592464.4891674575420950.70166653      592470.065    5420951.3545
     592482.2928    5420954.4551     592517.7109    5420963.4103
     592550.0097    5420971.5845     592554.2749    5420972.6705
     592609.5446    5420986.6564     592675.4122     5420981.714
     592704.3074    5420979.5546     592753.5405     5420975.863
     592754.7815    5420975.7694     592755.2421    5420975.7254
     592758.2646    5420975.5052     592772.2769    5420974.4498
     592807.9881    5420971.7801     592809.8398    5420971.6345
     592812.8423    5420971.4141     592834.6414    5420969.7812
     592922.0496    5420923.5869     592967.1283    5420899.7529
      592985.806    5420889.8898     592992.7134    5420886.2312
     592993.5893    5420885.7728     593054.4258    5420853.6171
     593215.7868     5420692.619     593228.2796    5420680.1448
     593234.1458    5420674.3026     593251.6742    5420656.8053
     593300.4695     5420608.123593328.5783616975420580.42338077

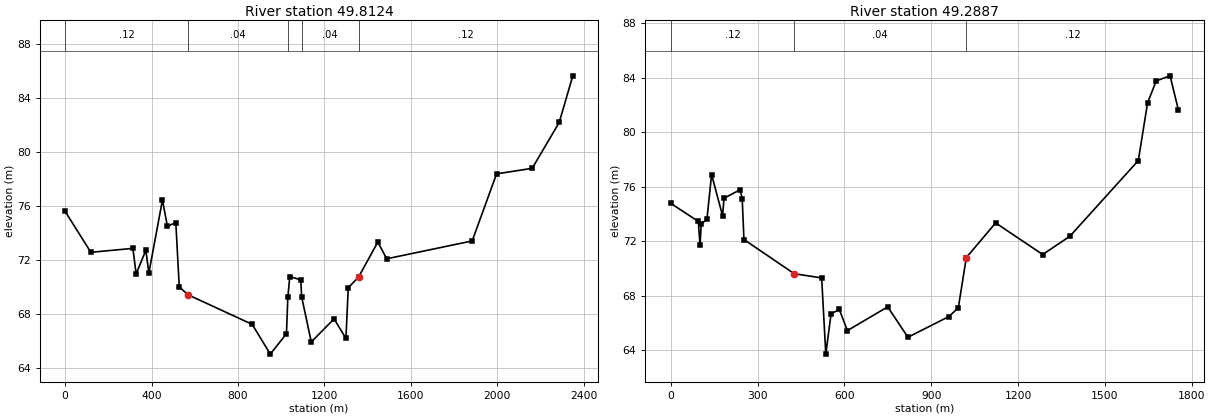
Type RM Length L Ch R = 1 ,49.8124 ,803.52,523.74,378.79
BEGIN DESCRIPTION:
R02A (SEM 2019)
END DESCRIPTION:
XS GIS Cut Line= 4
592295.5420035985422017.53628309592416.5131035985421462.56678309
592540.6005035985420663.98338309592643.2720035995419696.13978309
#Sta/Elev= 30
       0   75.59  118.79   72.57  313.45   72.86  328.42   70.97  373.34   72.72
  387.32   71.03  450.21   76.44  473.17   74.49   512.1   74.77  528.07   70.01
  568.53   69.43  865.61   67.24  949.41   65.04 1024.24   66.55 1030.53   69.23
 1039.52   70.78 1090.46   70.53 1094.46   69.28  1139.1   65.94 1244.66   67.65
 1299.48    66.2 1310.23   69.95 1357.62   70.73  1447.1   73.33 1488.07   72.09
 1883.77   73.41 1996.69   78.37 2161.56   78.78 2286.47   82.17 2349.43   85.62
#Mann= 5 ,-1 , 0
       0     .12       0  568.53     .04       0 1030.53     .12       0
 1094.46     .04       0 1357.62     .12       0
Bank Sta=568.53,1357.62
XS Rating Curve= 0 ,0
Exp/Cntr=0.3,0.1

Type RM Length L Ch R = 1 ,49.2887 ,782.52,939.38,745.21
BEGIN DESCRIPTION:
Camp Island - R02A (SEM 2019)
END DESCRIPTION:
XS GIS Cut Line= 4
592978.1684035985421615.36878309593198.8770035985421269.38198309
592870.4438035985420655.51768309592904.3578035985420008.33668309
#Sta/Elev= 30
       0   74.77   94.86   73.45  100.85   71.71  104.84   73.24  124.81   73.64
  140.79   76.89  178.73   73.87  183.73   75.15  239.64   75.78  246.63   75.11
  252.62   72.12  426.39   69.61  521.26    69.3 535.519  63.705  553.78  66.665
 582.291  66.985 610.158  65.435 749.501  67.175819.4189  64.945961.1211  66.465
  993.69   67.11 1021.16   70.79 1122.57   73.34 1285.33   71.02 1379.19   72.36
 1615.84   77.92  1647.8   82.16 1677.75   83.77 1725.68   84.14 1754.64    81.6
#Mann= 3 , 0 , 0
       0     .12       0  426.39     .04       0 1021.16     .12       0
Bank Sta=426.39,1021.16
XS Rating Curve= 0 ,0
Exp/Cntr=0.3,0.1

River Reach=Rushy Pond      ,Rushy Pond
Reach XY= 16
594039.3244358945421899.61768731594036.9632035985421802.09568309
594032.8720035985421724.36298309594002.0357035995421653.64928309
593917.3689035985421537.23238309593815.7687035995421448.33228309
593663.3684035995421319.21528309593604.1016035985421228.19848309
593595.6349035995421141.41498309593614.6850035985421080.03148309
593616.8016035995421003.83138309593631.6183035985420931.86458309
593580.8182035985420874.71438309593489.8014035985420826.03098309
593422.2466035985420768.53388309593346.3331035985420561.87178309
Reach Upstream Storage Area=Rushy Pond

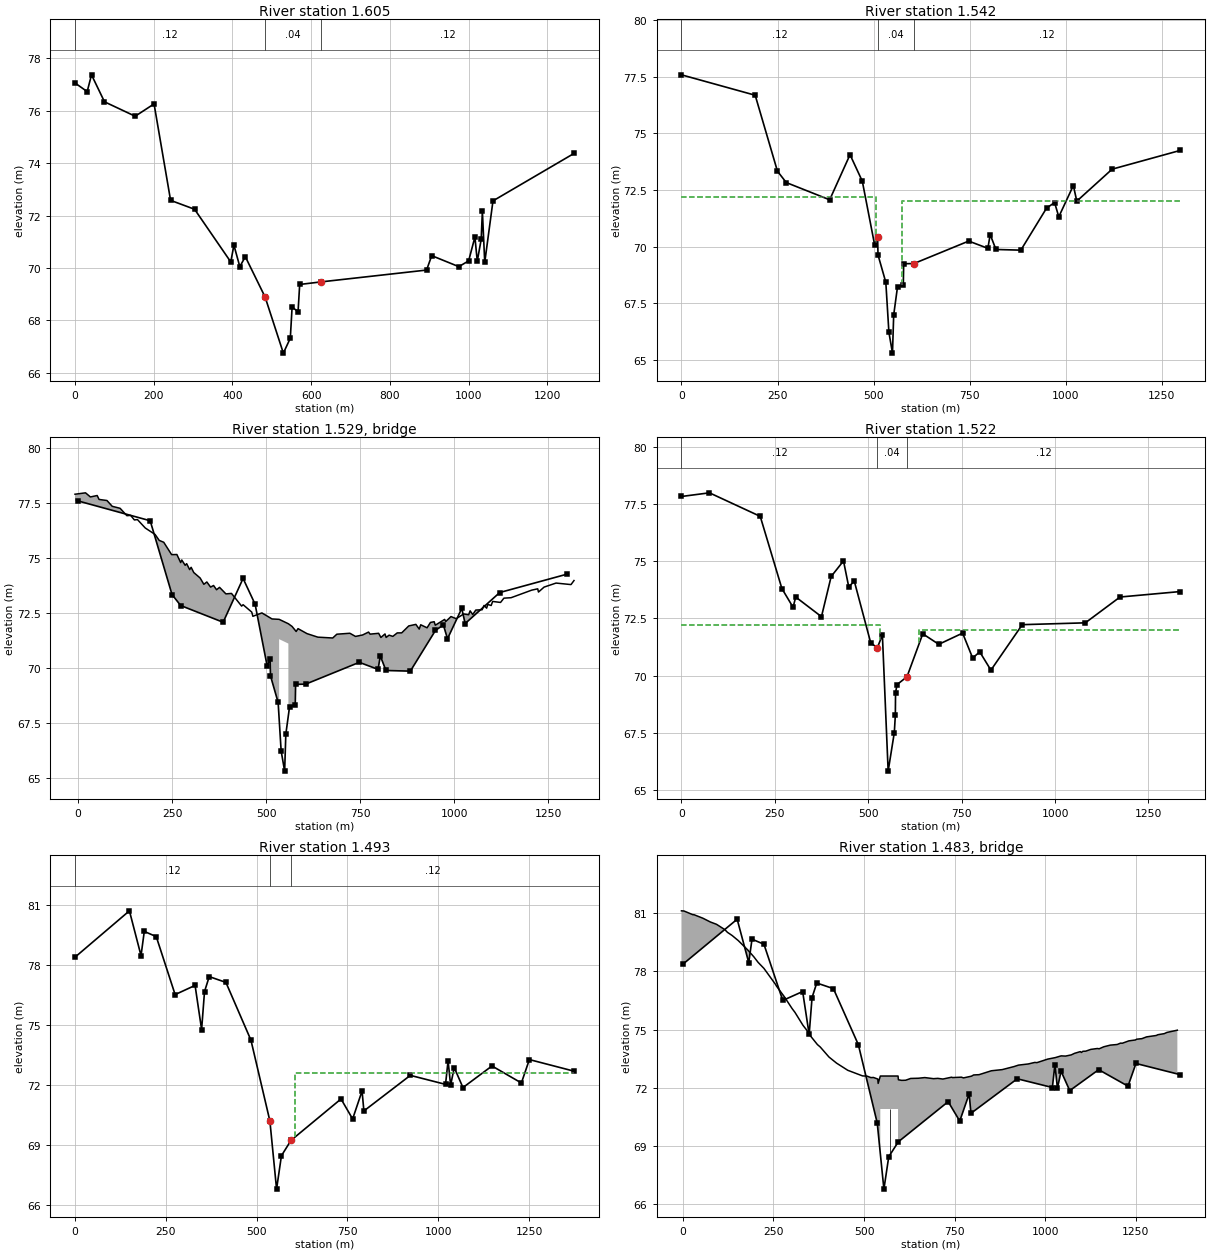
Type RM Length L Ch R = 1 ,1.605   ,63.85,62.61,66.16
BEGIN DESCRIPTION:
Rushy Pond - RP13 (SEM 2019)
END DESCRIPTION:
XS GIS Cut Line= 6
594571.4503035985421976.83008309594119.5832035985421886.85828309
594108.3648035985421886.01158309593916.1429035985421854.66458309
593532.4963035985421926.10218309593328.7667035985421980.34188309
#Sta/Elev= 30
       0   77.06   30.98   76.73   41.98   77.37   74.96   76.34  152.91   75.79
  200.89   76.26  242.86   72.58  303.83   72.24  395.77   70.23  403.77   70.87
  418.76   70.05  432.75   70.43  483.03   68.89  529.38   66.75  547.05   67.32
  551.62   68.51  566.75   68.33  570.87   69.37  625.99   69.47  893.31   69.92
  906.28   70.47  975.15   70.05  1000.1   70.27 1016.07   71.18 1022.06   70.26
 1032.04   71.09 1035.03   72.17 1041.02   70.21 1061.98   72.56 1267.82   74.37
#Mann= 3 , 0 , 0
       0     .12       0  483.03     .04       0  625.99     .12       0
#XS Ineff= 2 , 0
Permanent Ineff=
       F       F
Bank Sta=483.03,625.99
XS Rating Curve= 0 ,0
Exp/Cntr=0.3,0.1

Type RM Length L Ch R = 1 ,1.542   ,19.51,19.48,21.79
BEGIN DESCRIPTION:
US of Rushy Pond T'Railway Bridge - RP12 (SEM 2019)
END DESCRIPTION:
XS GIS Cut Line= 6
594582.8942035995421927.42518309594080.3750035995421821.29398309
594018.0850035995421807.94098309593913.4971035985421795.13318309
593551.0172035985421874.50838309593314.2146035985421936.68558309
#Sta/Elev= 30
       0   77.58  191.85   76.68  249.81   73.33  272.79   72.83   385.7   72.07
  438.66   74.06  470.64   72.89  502.61   70.09  510.46   70.41  511.48   69.64
  531.82   68.43  539.83   66.23  549.14   65.31  552.29   66.99  562.29   68.24
  577.31   68.32   578.3   69.25  605.07   69.26  747.52   70.25  797.39   69.93
  803.38   70.54  818.34   69.88  883.18   69.85  950.01    71.7  970.96   71.95
  981.93   71.32 1019.84    72.7 1028.81   72.01  1120.7   73.42 1298.58   74.25
#Mann= 3 , 0 , 0
       0     .12       0  510.46     .04       0  605.07     .12       0
#XS Ineff= 2 , 0
       0     505    72.2     575       0      72
Permanent Ineff=
       F       F
Bank Sta=510.46,605.07
XS Rating Curve= 0 ,0
Exp/Cntr=0.3,0.1

Type RM Length L Ch R = 3 ,1.529   ,,,
Node Photo=.\FFSModel_Pictures\RP_1_529.JPG
BEGIN DESCRIPTION:
Rushy Pond T'Railway Bridge
END DESCRIPTION:
Bridge Culvert--1,0,-1,-1, 0
Deck Dist Width WeirC Skew NumUp NumDn MinLoCord MaxHiCord MaxSubmerge Is_Ogee
5,4.2,1.4,0, 96, 96, , , 0.98, 0, 3,3,,
      -8   19.98   32.97  50.957  55.953  76.938  90.928 111.913   129.9 139.892
 149.885 157.879 178.864 204.845 215.837 227.828 248.813 262.803 272.795 275.793
 284.787 288.759 296.704 300.676 307.628 324.511 334.442 342.387 352.318 360.262
 368.207 376.152 393.035 407.931 434.779  438.77 461.722 464.716 488.665 515.609
 534.476 536.441 559.037 568.862 579.755  584.73 608.607 637.423 676.929 687.814
 722.524 737.399 756.265 772.158 776.131 798.978 804.938 815.857 818.815 826.703
 836.563 848.395 860.227 878.976 897.852 906.794 910.767 927.656 936.598 946.532
 949.513  974.35  977.33 991.2391005.1471025.0991038.0741042.0661049.0521057.037
1074.0031078.994 1085.981088.9741097.9561101.9491122.908 1131.891150.8531205.745
1221.714 1223.711238.6241270.4211310.1681318.117
  77.885  77.948  77.761  77.826  77.648  77.599  77.336  77.245   76.91  76.924
  76.716  76.734  76.349  76.058  75.788  75.703  75.141  75.147  74.781  74.898
  74.657  74.731   74.46  74.566  74.329  74.081  73.794    73.9  73.668   73.74
  73.547  73.656  73.359   73.38  72.804  72.867  72.531  72.341  72.495  72.221
  72.203  72.187  72.003  71.881  71.651  71.781  71.554  71.394  71.356  71.528
  71.571  71.427  71.493  71.625  71.531  71.569   71.38   71.54  71.381  71.485
  71.429  71.587  71.589  71.904  71.974  71.761  71.956  71.819  72.062  72.095
  71.937    72.2  72.104  72.329  72.232  72.448  72.412  72.589  72.422  72.625
  72.639  72.834   72.71  72.879  72.831  73.016   72.97  73.165  73.185  73.529
  73.589  73.442  73.667   73.85  73.781  73.965
                                                                                
                                                                                
                                                                                
                                                                                
  71.303  71.287  71.103
                                                                                
                                                                                
                                                                                
                                                                                
                                                
       5   32.98   45.97  63.957  68.953  89.938 103.928 124.913   142.9 152.892
 162.885 170.879 191.864 217.845 228.837 240.828 261.813 275.803 285.795 288.793
 297.787 301.759 309.704 313.676 320.628 337.511 347.442 355.387 365.318 373.262
 381.207 389.152 406.035 420.931 447.779  451.77 474.722 477.716 501.665 528.609
 547.476 549.441 572.037 581.862 592.755  597.73 621.607 650.423 689.929 700.814
 735.524 750.399 769.265 785.158 789.131 811.978 817.938 828.857 831.815 839.703
 849.563 861.395 873.227 891.976 910.852 919.794 923.767 940.656 949.598 959.532
 962.513  987.35  990.331004.2391018.1471038.0991051.0741055.0661062.0521070.037
1087.0031091.994 1098.981101.9741110.9561114.9491135.908 1144.891163.8531218.745
1234.714 1236.711251.6241283.4211323.1681331.117
  77.885  77.948  77.761  77.826  77.648  77.599  77.336  77.245   76.91  76.924
  76.716  76.734  76.349  76.058  75.788  75.703  75.141  75.147  74.781  74.898
  74.657  74.731   74.46  74.566  74.329  74.081  73.794    73.9  73.668   73.74
  73.547  73.656  73.359   73.38  72.804  72.867  72.531  72.341  72.495  72.221
  72.203  72.187  72.003  71.881  71.651  71.781  71.554  71.394  71.356  71.528
  71.571  71.427  71.493  71.625  71.531  71.569   71.38   71.54  71.381  71.485
  71.429  71.587  71.589  71.904  71.974  71.761  71.956  71.819  72.062  72.095
  71.937    72.2  72.104  72.329  72.232  72.448  72.412  72.589  72.422  72.625
  72.639  72.834   72.71  72.879  72.831  73.016   72.97  73.165  73.185  73.529
  73.589  73.442  73.667   73.85  73.781  73.965
                                                                                
                                                                                
                                                                                
                                                                                
  71.303  71.287  71.103
                                                                                
                                                                                
                                                                                
                                                                                
                                                
BR Coef=-1 , 0 , 0 ,, 0 ,,,0.8,-1,,0,
WSPro=,,,, 1 ,,,, 0 ,,,, 0 ,,,,-1 ,-1 ,-1 , 0 , 0 , 0 , 0 , 0
BC Design=,, 0 ,, 0 ,,,,,,
BC HTab HWMax=74
BC Use User HTab Curves=0
BC User HTab FreeFlow(D)= 0

Type RM Length L Ch R = 1 ,1.522   ,37.63,29.53,28.96
BEGIN DESCRIPTION:
DS of Rushy Pond T'Railway Bridge - RP11 (SEM 2019)
END DESCRIPTION:
XS GIS Cut Line= 5
594593.0807035985421906.91988309594067.0980035985421800.46598309
594019.1983035985421788.12178309593797.7416035985421759.94358309
593286.5656035985421885.35628309
#Sta/Elev= 30
       0   77.84   74.95      78  210.86   76.97  268.82   73.81   298.8   72.99
   305.8   73.44  374.75   72.58  400.74   74.34  433.72   75.02  447.71   73.89
   462.7   74.13  506.67   71.43  524.33   71.22  537.84   71.78  553.27   65.82
  569.77   67.51   572.5   68.27  573.06   69.26  577.21   69.61  603.67   69.95
  645.91   71.83  688.76   71.37  752.55   71.86  779.46   70.77  798.39   71.04
  828.33   70.24  912.22   72.23 1081.01   72.31 1173.89   73.44 1335.69   73.68
#Mann= 3 , 0 , 0
       0     .12       0  524.33     .04       0  603.67     .12       0
#XS Ineff= 2 , 0
       0     532    72.2     637       0      72
Permanent Ineff=
       F       F
Bank Sta=524.33,603.67
XS Rating Curve= 0 ,0
Exp/Cntr=0.3,0.1

Type RM Length L Ch R = 1 ,1.493   ,32.58,30.63,37.38
BEGIN DESCRIPTION:
RP10 (SEM 2019)
END DESCRIPTION:
XS GIS Cut Line= 4
594597.0495035985421871.20108309594072.0990035985421766.30398309
594002.2170035985421760.24798309593237.3530035985421688.50588309
#Sta/Elev= 30
       0   78.37  149.81   80.69  181.77   78.45  190.76   79.66  223.72    79.4
  275.65    76.5  330.58   76.96  348.56   74.75  356.55   76.65  369.54    77.4
  415.48   77.11  484.39   74.22  536.52   70.18  554.91   66.77  568.29   68.44
  594.72   69.21  732.34   71.28  764.31   70.28  790.28   71.68  795.28   70.68
  923.15   72.46 1020.05   72.01 1027.04   73.19 1034.04   71.97 1044.03   72.85
    1068   71.85 1147.92   72.93 1228.84   72.08 1250.82   73.25  1373.7   72.67
#Mann= 3 , 0 , 0
       0     .12       0  536.52     .04       0  594.72     .12       0
#XS Ineff= 2 , 0
       0                     605       0    72.6
Permanent Ineff=
       F       F
Bank Sta=536.52,594.72
XS Rating Curve= 0 ,0
Exp/Cntr=0.3,0.1

Type RM Length L Ch R = 3 ,1.483   ,,,
Node Photo=.\FFSModel_Pictures\RP_1_483.JPG
BEGIN DESCRIPTION:
Rushy Pond TCH Bridge
END DESCRIPTION:
Bridge Culvert--1,0,-1,-1, 0
Deck Dist Width WeirC Skew NumUp NumDn MinLoCord MaxHiCord MaxSubmerge Is_Ogee
15,8.6,1.4,0, 99, 99, , , 0.98, 0, 3,3,,
      -42.99018727.9551429.9523454.9172975.8878592.86402115.8318 122.822135.8037
152.7799179.7421195.7196207.7028223.6804255.6339258.6248279.5612301.4946309.4704
331.4038342.3705349.3493371.3078379.2954403.2582424.2257455.1777496.1142508.0956
519.0786526.0676538.0486539.0471545.0375546.0359 551.028556.0201559.0154566.0043
571.9948  574.99577.9852580.9805584.9741587.9694588.9678593.9599594.9583 603.944
614.9266628.9044649.8712667.8438691.8077703.7896717.7685741.7324744.7278768.6917
774.6827796.6495802.6405817.6179851.5668881.5215914.4719926.4538953.4131 971.386
 977.3771007.332  1028.31044.2761056.2581072.234 1081.221097.1961100.1921104.186
1112.1741126.1681144.1651149.1641162.1611180.1581199.1541208.1521213.1511231.148
1249.1441253.1431267.1411280.1381307.1331311.1321329.1281336.1271365.121
 81.1225 81.1138 80.9189 80.9275 80.7438 80.5462 80.4268 80.1524 80.0152 79.8513
  79.589  79.091 78.7529 78.4631 78.1541 77.3306 77.2332 76.7046  76.081 75.8828
 75.2207 74.9577 74.7357 74.2262 74.0971 73.5832 73.2677 72.8983 72.6083    72.6
 72.5212 72.5288 72.4462 72.2227  72.603  72.603  72.603  72.603  72.603  72.603
  72.603  72.603  72.603  72.603  72.603  72.603  72.603  72.603 72.4098 72.3788
 72.3855 72.4782 72.4885 72.5234 72.4666 72.4828 72.4473 72.5425 72.5233 72.5441
 72.5067 72.5956  72.658  72.673 72.8736 72.9338 73.0926 73.1657 73.2251 73.3041
 73.2937 73.4765 73.5537 73.6427 73.6308 73.6936 73.7734 73.8626 73.8187 73.8779
 73.8858 73.9768 74.0225  74.008 74.1125  74.197 74.2296 74.2998 74.2943 74.4162
 74.4616 74.5033 74.5303 74.6219 74.6949 74.7332 74.7898 74.8506 74.9672
                                                                                
                                                                                
                                                                                
                                  70.903  70.903  70.903  70.903  70.903  70.903
  70.903  70.903  70.903  70.903  70.903  70.903  70.903  70.903
                                                                                
                                                                                
                                                                                
                                                                                
                                                                        
       410.9901935.9551437.9523462.9172983.88785 100.864123.8318 130.822143.8037
160.7799187.7421203.7196215.7028231.6804263.6339266.6248287.5612309.4946317.4704
339.4038350.3705357.3493379.3078387.2954411.2582432.2257463.1777504.1142516.0956
527.0786534.0676546.0486547.0471553.0375554.0359 559.028564.0201567.0154574.0043
579.9948  582.99585.9852588.9805592.9741595.9694596.9678601.9599602.9583 611.944
622.9266636.9044657.8712675.8438699.8077711.7896725.7685749.7324752.7278776.6917
782.6827804.6495810.6405825.6179859.5668889.5215922.4719934.4538961.4131 979.386
 985.3771015.332  1036.31052.2761064.2581080.234 1089.221105.1961108.1921112.186
1120.1741134.1681152.1651157.1641170.1611188.1581207.1541216.1521221.1511239.148
1257.1441261.1431275.1411288.1381315.1331319.1321337.1281344.1271373.121
 81.1225 81.1138 80.9189 80.9275 80.7438 80.5462 80.4268 80.1524 80.0152 79.8513
  79.589  79.091 78.7529 78.4631 78.1541 77.3306 77.2332 76.7046  76.081 75.8828
 75.2207 74.9577 74.7357 74.2262 74.0971 73.5832 73.2677 72.8983 72.6083    72.6
 72.5212 72.5288 72.4462 72.2227  72.603  72.603  72.603  72.603  72.603  72.603
  72.603  72.603  72.603  72.603  72.603  72.603  72.603  72.603 72.4098 72.3788
 72.3855 72.4782 72.4885 72.5234 72.4666 72.4828 72.4473 72.5425 72.5233 72.5441
 72.5067 72.5956  72.658  72.673 72.8736 72.9338 73.0926 73.1657 73.2251 73.3041
 73.2937 73.4765 73.5537 73.6427 73.6308 73.6936 73.7734 73.8626 73.8187 73.8779
 73.8858 73.9768 74.0225  74.008 74.1125  74.197 74.2296 74.2998 74.2943 74.4162
 74.4616 74.5033 74.5303 74.6219 74.6949 74.7332 74.7898 74.8506 74.9672
                                                                                
                                                                                
                                                                                
                                  70.903  70.903  70.903  70.903  70.903  70.903
  70.903  70.903  70.903  70.903  70.903  70.903  70.903  70.903
                                                                                
                                                                                
                                                                                
                                                                                
                                                                        
Pier Skew, UpSta & Num, DnSta & Num=  ,571.75, 2 ,579.75, 2 , 0 , 0 , 0 ,,
       2       2
       0      72
       2       2
       0      72
BR Coef=-1 , 0 , 0 ,, 0 ,,,0.8,-1,,0,
WSPro=,,,, 1 ,,,, 0 ,,,, 0 ,,,,-1 ,-1 ,-1 , 0 , 0 , 0 , 0 , 0
BC Design=,, 0 ,, 0 ,,,,,,
BC HTab HWMax=76
BC Use User HTab Curves=0
BC User HTab FreeFlow(D)= 0

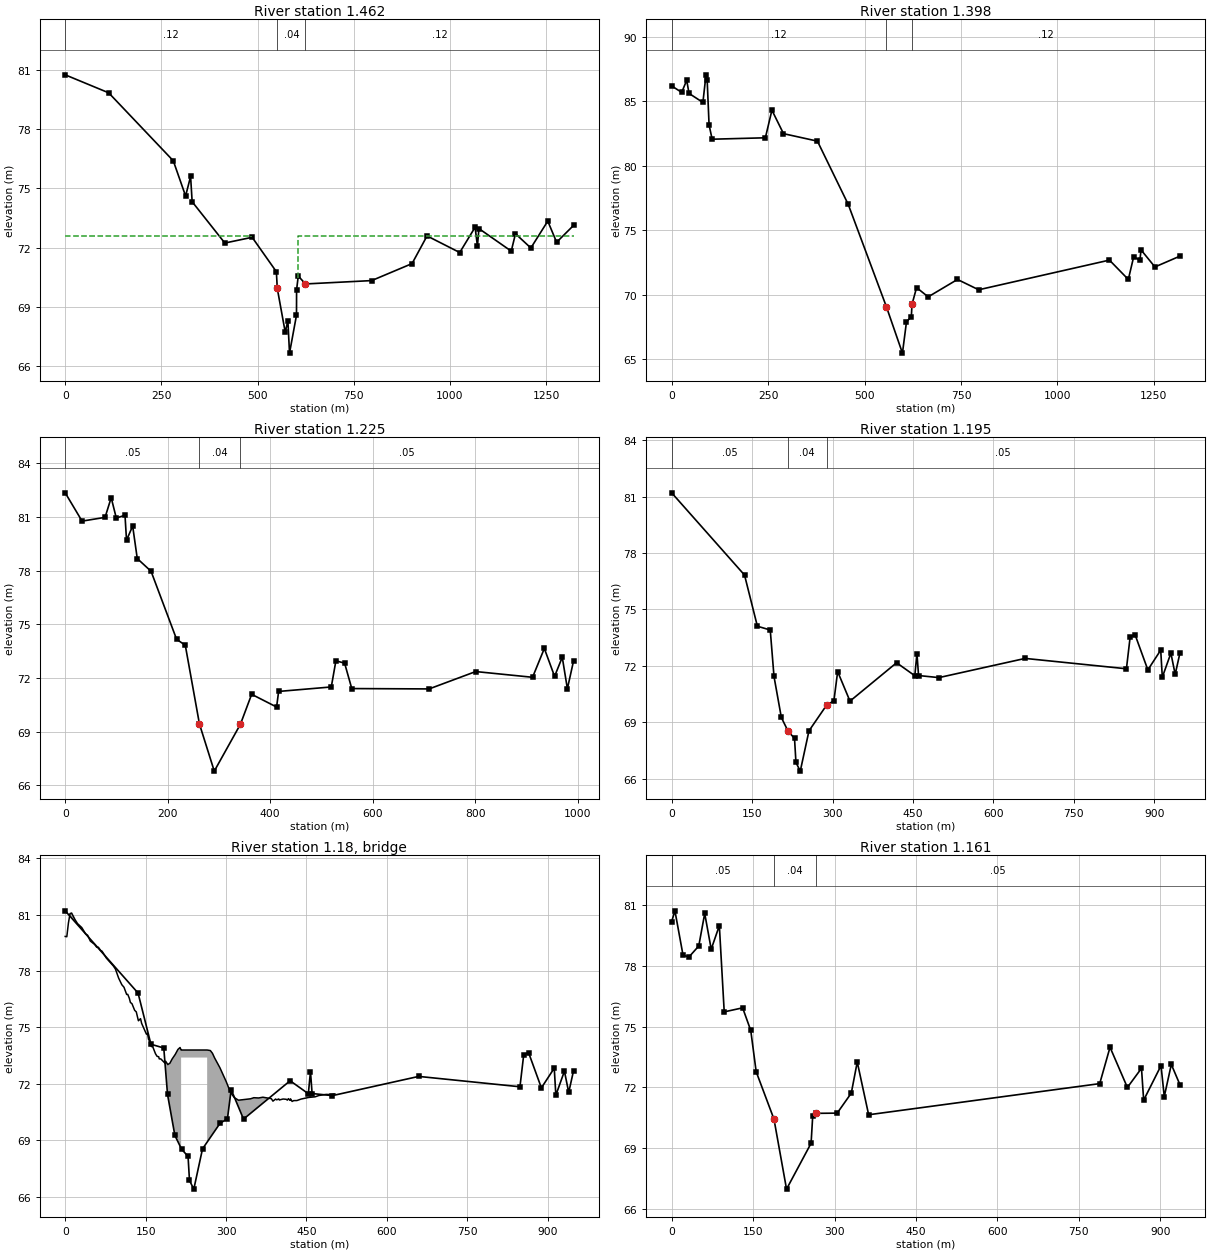
Type RM Length L Ch R = 1 ,1.462   ,77.12,64.12,47.6
BEGIN DESCRIPTION:
RP09 (SEM 2019)
END DESCRIPTION:
XS GIS Cut Line= 4
594608.9557035985421826.75098309594063.9130035985421734.41118309
593992.2108035985421729.91328309593300.8531035995421645.64338309
#Sta/Elev= 30
       0   80.75  112.96   79.84   280.9    76.4  312.89   74.62  325.89   75.61
  329.89   74.33  414.86   72.24  485.83   72.53  548.81   70.79  551.21   69.94
  571.83   67.73  578.74   68.31  582.97   66.67  601.11   68.59  601.34   69.87
  605.71   70.57  624.45   70.17  796.52   70.34  901.45    71.2  940.42    72.6
 1025.36   71.76 1065.33   73.04 1071.32   72.09 1075.32   72.97 1159.26   71.83
 1170.25   72.71 1210.22   71.99 1254.19   73.35 1277.17   72.28 1321.14   73.13
#Mann= 3 , 0 , 0
       0     .12       0  551.21     .04       0  624.45     .12       0
#XS Ineff= 2 , 0
       0     484    72.6     605       0    72.6
Permanent Ineff=
       F       F
Bank Sta=551.21,624.45
XS Rating Curve= 0 ,0
Exp/Cntr=0.3,0.1

Type RM Length L Ch R = 1 ,1.398   ,183.71,172.77,159.43
BEGIN DESCRIPTION:
RP08 (SEM 2019)
END DESCRIPTION:
XS GIS Cut Line= 4
594593.6099035985421676.99648309594052.2840035995421656.97798309
593964.4294035985421690.75488309593284.9781035995421634.53078309
#Sta/Elev= 30
       0   86.18   25.99   85.68   38.98   86.62   44.97    85.6   80.95    84.9
   88.95   87.04   91.95   86.67   96.95   83.15  104.94   82.05  242.86   82.16
  259.85    84.3  289.84   82.48  377.79    81.9  457.74   76.99  556.51   69.07
  598.17   65.47  608.61   67.89  621.21    68.3  622.95   69.25  634.83   70.55
  664.81   69.83  740.78   71.18  795.77   70.38 1134.66   72.68 1183.64   71.18
 1197.64   72.95 1213.63   72.66 1216.63   73.47 1252.62   72.15  1317.6   72.99
#Mann= 3 , 0 , 0
       0     .12       0  556.51     .04       0  622.95     .12       0
#XS Ineff= 2 , 0
Permanent Ineff=
       F       F
Bank Sta=556.51,622.95
XS Rating Curve= 0 ,0
Exp/Cntr=0.3,0.1

Type RM Length L Ch R = 1 ,1.225   ,35.7,30.12,24.68
BEGIN DESCRIPTION:
RP07 (SEM 2019)
END DESCRIPTION:
XS GIS Cut Line= 5
594162.3382035985421372.72508309593941.5429035985421508.58888309
593874.2460035985421561.63198309593773.9687035985421558.85388309
593232.5905035995421634.53078309
#Sta/Elev= 30
       0   82.34    32.9   80.76   77.77   80.97   89.74   82.07   99.71   80.93
  116.66   81.09  119.65   79.69  131.62   80.49  140.59   78.67  167.51   77.96
  217.37   74.16  234.32   73.83  261.95   69.43  290.87    66.8  341.93   69.42
  363.81   71.09  412.48   70.38  416.45   71.25   519.2    71.5   528.2   72.96
  545.19   72.83  559.18   71.41  710.08   71.39  801.02   72.36  911.95   72.04
  934.93   73.65  954.92   72.09  969.91   73.16   979.9    71.4   991.9   72.95
#Mann= 3 , 0 , 0
       0     .05       0  261.95     .04       0  341.93     .05       0
#XS Ineff= 2 , 0
Permanent Ineff=
       F       F
Bank Sta=261.95,341.93
XS Rating Curve= 0 ,0
Exp/Cntr=0.3,0.1

Type RM Length L Ch R = 1 ,1.195   ,28.04,34.66,44.69
BEGIN DESCRIPTION:
US of Gold Course Bridge - RP06 (SEM 2019)
END DESCRIPTION:
XS GIS Cut Line= 4
594068.4109035985421342.29798309593917.3335035985421483.58568309
593859.8910035985421541.78598309593205.6029035985421625.00578309
#Sta/Elev= 30
       0    81.2   135.9   76.83  159.88   74.11  183.87   73.91  190.86   71.44
  204.57   69.26  217.15   68.53  229.15   68.15  231.81   66.87  239.87   66.41
   256.1   68.55  288.84   69.91  302.61   70.15  309.61    71.7  332.59   70.13
  419.54   72.17  453.51   71.48  457.51   72.66  460.51   71.49  498.48   71.38
  659.37    72.4  848.25   71.85  855.24   73.55  864.24   73.67  888.22   71.79
   912.2   72.84   915.2    71.4  931.19   72.68  939.19   71.55  948.18    72.7
#Mann= 3 , 0 , 0
       0     .05       0  217.15     .04       0  288.84     .05       0
Bank Sta=217.15,288.84
XS Rating Curve= 0 ,0
Exp/Cntr=0.3,0.1

Type RM Length L Ch R = 3 ,1.18    ,,,
Node Photo=.\FFSModel_Pictures\RP_1_180.JPG
BEGIN DESCRIPTION:
Golf Course Bridge
END DESCRIPTION:
Bridge Culvert--1,0,-1,-1, 0
Deck Dist Width WeirC Skew NumUp NumDn MinLoCord MaxHiCord MaxSubmerge Is_Ogee
18,3,1.4,0, 100, 100, , , 0.98, 0, 3,3,,
       0    2.99    5.98    8.97  11.959  17.939  22.922  30.895  37.872  41.858
  46.841  54.814  58.801  61.791  65.777  68.767   76.74  89.696  93.683  99.662
 105.642 109.629 114.612 116.605 119.595 121.588 124.578 129.561 132.551 136.537
 140.524 142.517 151.487  153.48 155.473 158.463 160.456 163.446 168.429 171.419
 174.409 175.406 178.395 186.368 187.365 191.352 195.338 199.325 205.284 210.243
 214.209 216.192 217.184 220.159 221.151 224.125 225.117  233.05 235.033 238.008
 256.849 257.841 260.816 262.799 263.791 264.782 270.732 274.699 278.658 288.548
 300.417  308.33 315.253 323.166 345.914 351.849 360.752 368.669 384.502 387.482
 392.449 394.436 398.409 399.403 406.357 412.317 414.304 416.291 419.271 420.265
 423.245 426.225 432.196 440.165  454.11 466.063 473.036 486.487 495.146 503.105
  79.839  79.824   80.55  81.054  81.083  80.751  80.523   80.31  79.985  79.901
  79.593  79.417  79.263  79.267  79.104  79.052  78.689  78.274  78.106  77.625
  77.271   77.14  76.756  76.763  76.553  76.332  76.262  75.911  75.832  75.356
  75.471  75.222  74.645  74.691  74.369  74.235  73.993  73.966  73.603  73.466
  73.445  73.332  73.329  73.096  73.207  73.029  73.106  73.321  73.572  73.833
  73.936  73.803  73.803  73.803  73.803  73.803  73.803  73.803  73.803  73.803
  73.803  73.803  73.803  73.803  73.803  73.803  73.775  73.628  73.383  72.863
  72.117   71.55  71.278  71.136  71.212  71.269  71.254  71.295  71.217  71.086
  71.197  71.155  71.202  71.148  71.199  71.184   71.14  71.218  71.124  71.208
   71.07  71.115  71.117  71.198  71.282  71.315  71.384  71.444  71.438  71.469
                                                                                
                                                                                
                                                                                
                                                                                
                                                                                
          73.403  73.403  73.403  73.403  73.403  73.403  73.403  73.403  73.403
  73.403  73.403  73.403  73.403  73.403  73.403
                                                                                
                                                                                
                                                                                
     -20-17.0101-14.0202-11.0304-8.04053-2.06079 2.92232 10.895317.8716621.85815
26.8412634.8142438.80073 41.790645.7770948.7669656.7399469.6960473.6825379.66226
  85.642 89.6285 94.6116 96.6048 99.5947 101.588104.5778109.5609112.5508116.5373
120.5238 122.517131.4866133.4799135.4731 138.463140.4562143.4461148.4292151.4191
 154.409155.4056158.3954166.3684167.3651171.3515 175.338179.3245185.2843190.2425
 194.209196.1923197.1839200.1588201.1505204.1254 205.117213.0501215.0334218.0083
236.8494 237.841240.8159242.7992243.7908244.7824250.7322254.6988258.6576268.5483
280.4171288.3297295.2531303.1657325.9143331.8487340.7522348.6686364.5015367.4818
372.4489374.4357378.4094379.4028386.3567392.3172394.3041396.2909399.2712400.2646
403.2448406.2251412.1963420.1649434.1101446.0631453.0357466.4868475.1463483.1054
  79.839  79.824   80.55  81.054  81.083  80.751  80.523   80.31  79.985  79.901
  79.593  79.417  79.263  79.267  79.104  79.052  78.689  78.274  78.106  77.625
  77.271   77.14  76.756  76.763  76.553  76.332  76.262  75.911  75.832  75.356
  75.471  75.222  74.645  74.691  74.369  74.235  73.993  73.966  73.603  73.466
  73.445  73.332  73.329  73.096  73.207  73.029  73.106  73.321  73.572  73.833
  73.936  73.803  73.803  73.803  73.803  73.803  73.803  73.803  73.803  73.803
  73.803  73.803  73.803  73.803  73.803  73.803  73.775  73.628  73.383  72.863
  72.117   71.55  71.278  71.136  71.212  71.269  71.254  71.295  71.217  71.086
  71.197  71.155  71.202  71.148  71.199  71.184   71.14  71.218  71.124  71.208
   71.07  71.115  71.117  71.198  71.282  71.315  71.384  71.444  71.438  71.469
                                                                                
                                                                                
                                                                                
                                                                                
                                                                                
          73.403  73.403  73.403  73.403  73.403  73.403  73.403  73.403  73.403
  73.403  73.403  73.403  73.403  73.403  73.403
                                                                                
                                                                                
                                                                                
BR Coef=-1 , 0 , 0 ,, 0 ,,,0.8,-1,,0,
WSPro=,,,, 1 ,,,, 0 ,,,, 0 ,,,,-1 ,-1 ,-1 , 0 , 0 , 0 , 0 , 0
BC Design=,, 0 ,, 0 ,,,,,,
BC HTab HWMax=76
BC Use User HTab Curves=0
BC User HTab FreeFlow(D)= 0

Type RM Length L Ch R = 1 ,1.161   ,62.62,56.22,46.95
BEGIN DESCRIPTION:
DS of Golf Course Bridge - RP05 (SEM 2019)
END DESCRIPTION:
XS GIS Cut Line= 4
593994.3274035985421310.54788309593897.8410035995421467.89198309
593829.5460035985421510.13898309593167.5029035985421621.83078309
#Sta/Elev= 30
       0    80.2    5.99   80.73   20.95   78.53   31.93   78.45   49.88   78.99
   60.86    80.6   72.83   78.83    87.8      80   96.78   75.73   130.7   75.93
  145.66   74.81  155.64   72.77  188.46   70.42  211.57   66.96  256.79   69.23
  259.73   70.56  266.57   70.71  304.84   70.72  330.82   71.71  341.81   73.25
  362.79   70.64  788.41   72.18   807.4   73.98  839.37   71.99  865.35   72.94
  869.34   71.36  901.31   73.07  907.31   71.54   920.3   73.13  936.28   72.12
#Mann= 3 , 0 , 0
       0     .05       0  188.46     .04       0  266.57     .05       0
Bank Sta=188.46,266.57
XS Rating Curve= 0 ,0
Exp/Cntr=0.3,0.1

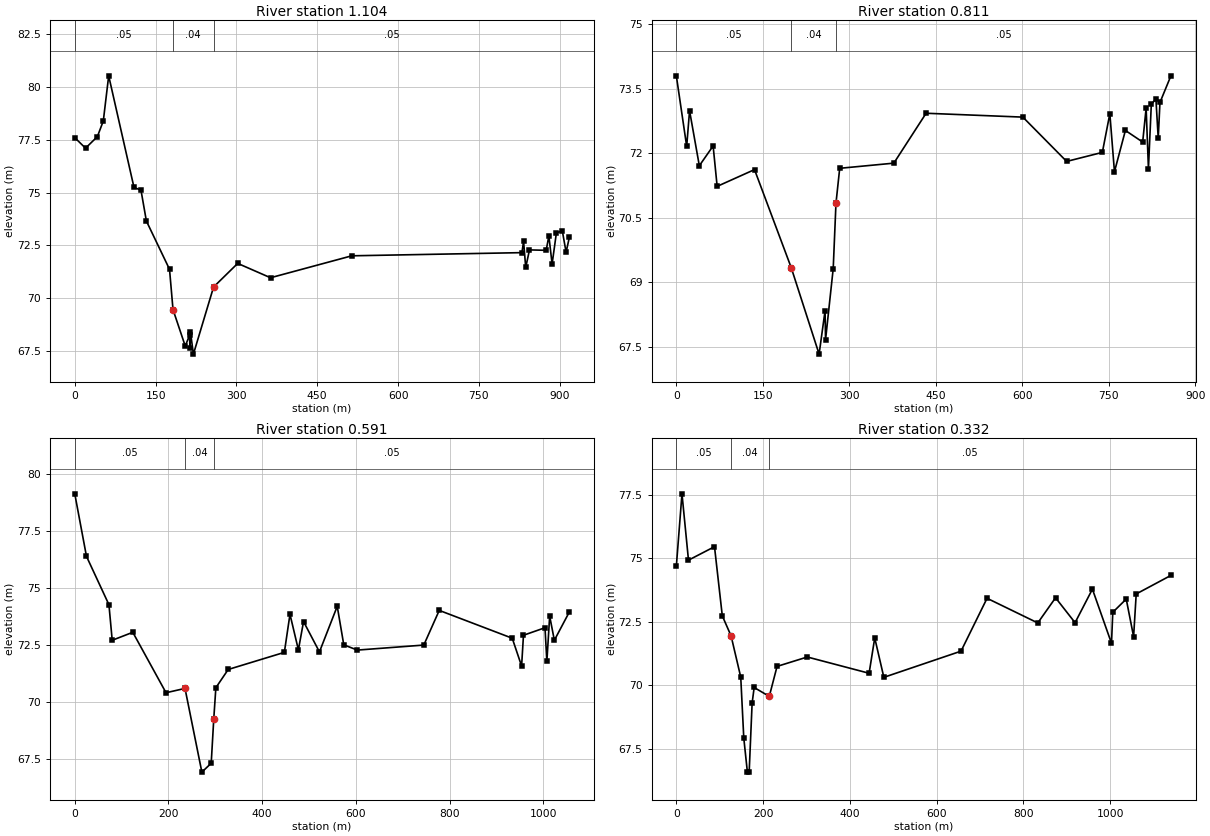
Type RM Length L Ch R = 1 ,1.104   ,281.55,293.12,309.8
BEGIN DESCRIPTION:
RP04 (SEM 2019)
END DESCRIPTION:
XS GIS Cut Line= 4
593958.6086035995421282.76658309593847.2840035995421426.55298309
593793.0602035985421479.18748309593146.8653035985421615.48078309
#Sta/Elev= 30
       0    77.6   19.98    77.1   41.96   77.65   52.95   78.39   62.95   80.53
  109.91   75.24   122.9   75.11  132.89   73.65  175.85   71.36  182.32   69.45
  205.05   67.72  213.08   68.24  213.66   67.64  214.71   68.38  220.19   67.34
  257.58   70.52  302.37   71.64  363.32   70.96  514.19      72   829.9   72.15
   832.9   72.69  836.89   71.45  843.89   72.28  874.86   72.26  879.85   72.94
  885.85   71.61  893.84   73.09  904.83   73.18  911.82   72.17  917.82   72.87
#Mann= 3 , 0 , 0
       0     .05       0  182.32     .04       0  257.58     .05       0
Bank Sta=182.32,257.58
XS Rating Curve= 0 ,0
Exp/Cntr=0.3,0.1

Type RM Length L Ch R = 1 ,0.811   ,219.57,220.6,242.99
BEGIN DESCRIPTION:
RP03 (SEM 2019)
END DESCRIPTION:
XS GIS Cut Line= 4
593837.3410035995421167.67258309593651.5840035985421228.37898309
593576.5180035985421266.00898309593116.7028035985421617.06828309
#Sta/Elev= 30
       0    73.8   17.95   72.16   22.93   72.99   39.88   71.71   63.81   72.17
   70.79   71.23   135.6   71.62  199.29   69.34  247.65   67.33  257.99   68.34
   258.8   67.66  272.13   69.32  276.92   70.84  283.39   71.65  377.31   71.77
  433.26   72.93  601.12   72.84  677.06   71.81     739   72.02  751.99   72.92
  759.99   71.57  778.97   72.53  808.95   72.26  814.94   73.05  818.94   71.64
  823.93   73.14  831.93   73.26  835.92   72.35  838.92   73.18   857.9    73.8
#Mann= 3 , 0 , 0
       0     .05       0  199.29     .04       0  276.92     .05       0
#XS Ineff= 2 , 0
Permanent Ineff=
       F       F
Bank Sta=199.29,276.92
XS Rating Curve= 0 ,0
Exp/Cntr=0.3,0.1

Type RM Length L Ch R = 1 ,0.591   ,316.1,258.95,211.39
BEGIN DESCRIPTION:
RP02 (SEM 2019)
END DESCRIPTION:
XS GIS Cut Line= 4
593871.7369035995421030.08898309593675.9448035985421027.44318309
593566.5720035985421036.64998309593088.5687035985421614.81928309
#Sta/Elev= 30
       0   79.13   24.98   76.39   72.93   74.27   79.92   72.71  123.88   73.06
  194.81   70.41  235.32    70.6  271.31   66.93  291.26   67.32  296.77   69.28
  301.19   70.63  327.54   71.43  447.41   72.18   459.4   73.85  477.38   72.29
  488.37   73.53  522.33    72.2  560.29    74.2  574.27   72.51  603.24   72.28
  745.09    72.5  778.05   74.02  933.88    72.8  953.86   71.58  957.86   72.93
 1003.81   73.26  1007.8   71.78  1013.8   73.77 1023.79   72.71 1055.75   73.95
#Mann= 3 , 0 , 0
       0     .05       0  235.32     .04       0  296.77     .05       0
#XS Ineff= 2 , 0
Permanent Ineff=
       F       F
Bank Sta=235.32,296.77
XS Rating Curve= 0 ,0
Exp/Cntr=0.3,0.1

Type RM Length L Ch R = 1 ,0.332   ,19.87,331.75,35.98
BEGIN DESCRIPTION:
RP01 (SEM 2019)
END DESCRIPTION:
XS GIS Cut Line= 6
593491.7945035985420673.95908309593523.5445035985420773.97178309
593506.8050035985420844.70498309593542.5946035985420962.88468309
593514.0195035985421032.73478309593040.9436035995421630.69438309
#Sta/Elev= 30
       0   74.69   12.99   77.54   27.98   74.93   87.94   75.46  105.91   72.74
  126.15   71.95  148.41   70.33  155.43   67.93  163.74   66.59  167.89   66.61
  174.62    69.3  179.33   69.92  214.18   69.57   232.1   70.75  301.81   71.12
  444.23   70.48  457.22   71.87  478.21   70.32  656.08   71.35  716.04   73.43
  832.95   72.46  873.92   73.45  918.89   72.47  958.86   73.79 1002.83   71.66
 1005.83   72.88 1036.81    73.4 1053.79   71.92 1059.79    73.6 1139.73   74.33
#Mann= 3 , 0 , 0
       0     .05       0  126.15     .04       0  214.18     .05       0
Bank Sta=126.15,214.18
XS Rating Curve= 0 ,0
Exp/Cntr=0.3,0.1

River Reach=Exploits River  ,RP to Outlet
Reach XY= 30
593328.5783616975420580.42338077      594148.221    5420065.2206
      594958.337    5420583.8262      595484.828    5420461.6589
     596903.2042    5421559.7117     597369.1672    5421212.4015
     597393.1335    5420131.3395     597631.9702    5419924.5543
     598488.3108     5419896.537     598768.5434      5419651.01
     600447.7761    5420086.3458     605694.7374    5425052.9373
     607159.5715    5426803.5173     608874.3401    5427897.0445
     609866.1774    5429243.5019     611197.0431    5429756.2983
      612065.398    5430514.8727     613671.7875    5431160.4158
     614791.4881    5431958.2861     616124.7997    5432286.9887
     616758.1957    5432083.6825     618100.2081    5434482.4732
      619577.313    5435462.8482      622129.673    5437998.1886
     623324.0339    5438173.9955     623860.1143    5438650.6812
     623929.6066     5439399.006      623278.784    5440600.8193
     622502.0499    5443824.9191     622563.7261    5446167.1662

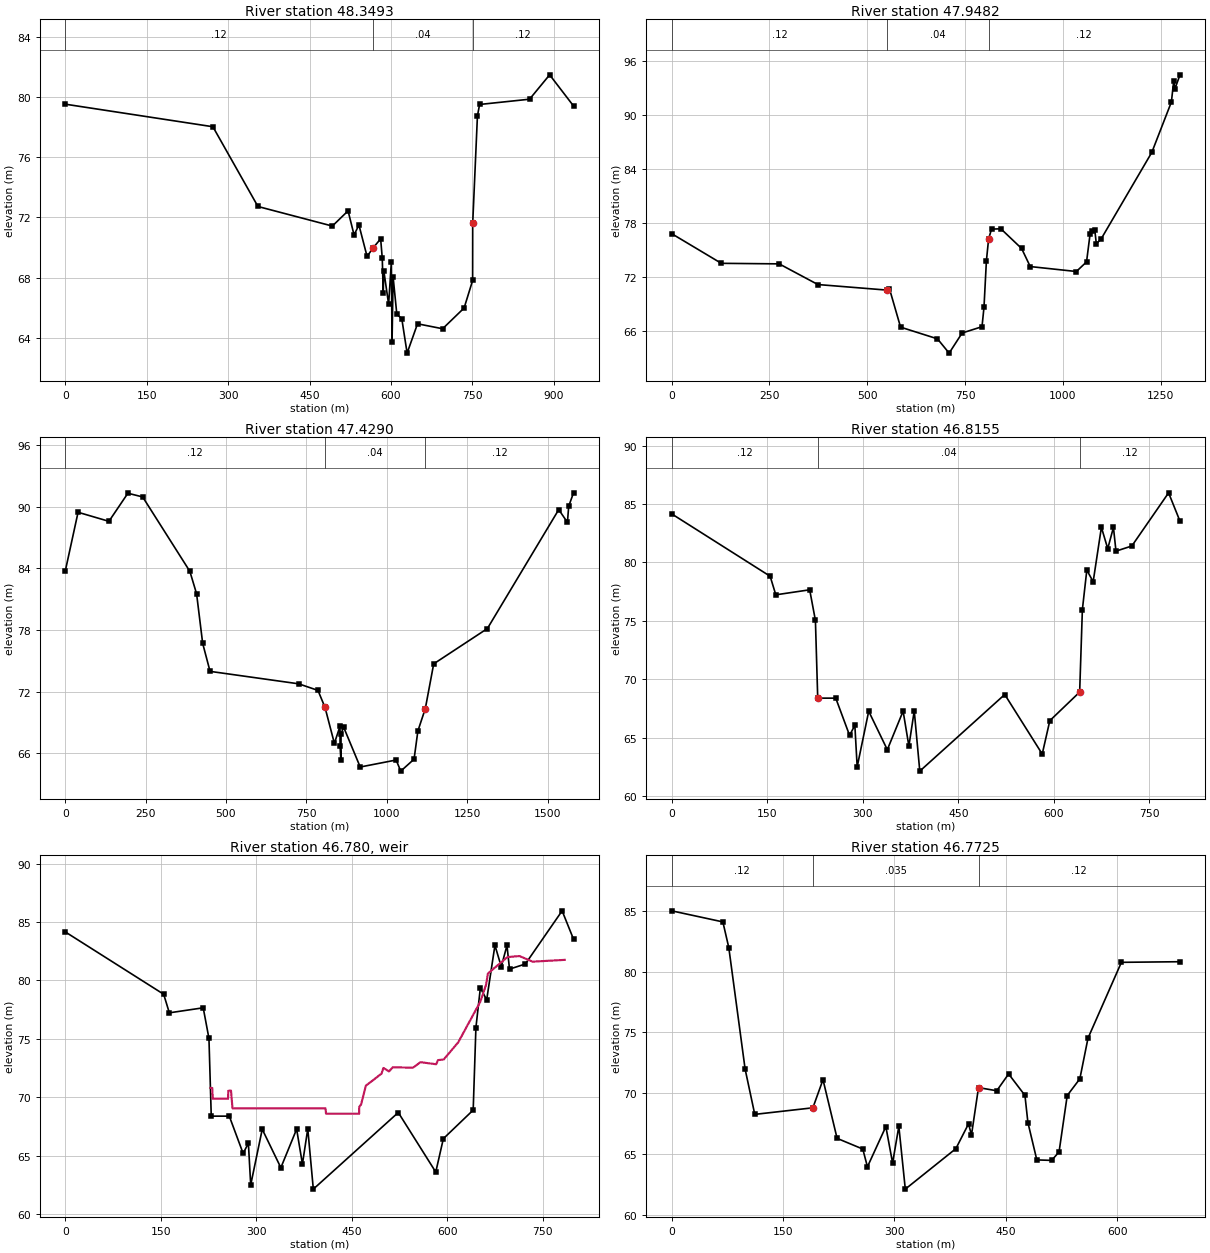
Type RM Length L Ch R = 1 ,48.3493 ,323.78,401.12,495.42
BEGIN DESCRIPTION:
Grand Falls Golf Club - R03 (RIS 2013)
END DESCRIPTION:
XS GIS Cut Line= 4
594097.2124035985420723.51688309593722.7239035985420282.07668309
593591.9733035985420171.52808309593462.8692035985420037.68388309
#Sta/Elev= 30
       0   79.53  271.95   78.03  354.93   72.73  491.91   71.43   520.9   72.44
   531.9   70.84   540.9    71.5  555.89   69.41  566.73   69.97  580.88   70.58
  583.87   69.29  585.64  66.995  586.71  68.465  595.59  66.225   600.6  69.065
  601.87  63.705  603.84  68.045  610.67  65.565  619.81  65.275  629.63  62.985
  648.77  64.935     695  64.605   734.6  65.985  750.26  67.815  750.39    71.6
  759.11   78.75  763.11   79.51  855.09   79.86  892.09   81.48  936.08   79.41
#Mann= 3 , 0 , 0
       0     .12       0  566.73     .04       0  750.39     .12       0
Bank Sta=566.73,750.39
XS Rating Curve= 0 ,0
Exp/Cntr=0.3,0.1

Type RM Length L Ch R = 1 ,47.9482 ,466.43,519.18,595.07
BEGIN DESCRIPTION:
DS of Rushy Pond Brook - R04 (RIS 2013)
END DESCRIPTION:
XS GIS Cut Line= 4
594169.7219035985420692.43048309594013.3890035985420154.02098309
593979.8898035995419678.27508309594038.2769035995419422.95438309
#Sta/Elev= 30
       0   76.81  126.92   73.51  274.83   73.45  373.77   71.15   550.7   70.53
  556.65    70.7  585.14   66.41  679.43   65.11   709.3   63.52  742.57   65.76
  793.33   66.46  798.37   68.61  804.61   73.82  810.16    76.2  817.61   77.32
   841.6   77.35   894.6   75.16  916.59   73.15 1034.57    72.6 1060.56   73.67
 1069.56   76.75 1073.56    77.1 1081.56   77.25 1085.56   75.69 1097.55    76.2
  1227.5   85.86 1277.49   91.46 1283.48   93.84 1286.48   92.92 1299.48   94.48
#Mann= 3 , 0 , 0
       0     .12       0   550.7     .04       0  810.16     .12       0
Bank Sta=550.7,810.16
XS Rating Curve= 0 ,0
Exp/Cntr=0.3,0.1

Type RM Length L Ch R = 1 ,47.4290 ,648.13,613.51,432.68
BEGIN DESCRIPTION:
R04A (SEM 2019)
END DESCRIPTION:
XS GIS Cut Line= 4
  594429.2282036 5421129.4479831  594228.1445036 5420880.7390831
  594282.1953036 5420653.8590831  594720.9810036 5419724.6056831
#Sta/Elev= 30
       0    83.7   39.98   89.44  135.93   88.56   194.9   91.29  240.87   90.93
  387.61    83.7  408.54   81.52  427.47    76.7   450.4   73.98     726   72.77
  785.98   72.13  807.97   70.47  837.01  66.985  854.51  68.645  854.67  66.695
  857.35  65.365  857.78  67.875  865.58  68.575  917.32  64.685 1029.05  65.365
 1043.41  64.285 1084.79  65.445 1096.67  68.185 1119.86   70.37 1145.85   74.71
 1312.79   78.14 1534.71    89.7  1561.7   88.46  1565.7   90.03  1580.7   91.33
#Mann= 3 , 0 , 0
       0     .12       0  807.97     .04       0 1119.86     .12       0
Bank Sta=807.97,1119.86
XS Rating Curve= 0 ,0
Exp/Cntr=0.3,0.1

Type RM Length L Ch R = 1 ,46.8155 ,102.81,43,165.09
BEGIN DESCRIPTION:
R05 (RIS 2013)
END DESCRIPTION:
XS GIS Cut Line= 6
  595151.1957036 5420826.9782831  594966.0689036 5420742.0971831
  594997.5544036 5420671.7178831  594967.9210036 5420499.2091831
  594876.3750036 5420390.4651831  594835.6290036 5420202.8752831
#Sta/Elev= 30
       0   84.15  154.61   78.81  163.48   77.22  216.69   77.65  225.69   75.03
  229.31  68.377 257.622  68.377 279.346  65.187 287.609  66.059 291.251  62.497
 309.362  67.255 338.582  63.963 363.374  67.265 372.458  64.273 380.855  67.291
 389.559   62.13 522.952  68.688 581.808  63.592 593.717  66.448 640.569  68.896
  644.85   75.96  651.82   79.34  661.77   78.34  674.71      83  684.66   81.17
  693.62   82.99   697.6   80.96  722.48    81.4   780.2   85.95  798.12   83.52
#Mann= 3 , 0 , 0
       0     .12       0  229.31     .04       0 640.569     .12       0
Bank Sta=229.31,640.569
XS Rating Curve= 0 ,0
Exp/Cntr=0.3,0.1

Type RM Length L Ch R = 5 ,46.780  ,,,
BEGIN DESCRIPTION:
Goodyear's Dam
END DESCRIPTION:
IW Pilot Flow=0
#Inline Weir SE= 30
     228  70.795 230.859  70.789 231.631  69.864 255.648  69.864 256.089  70.546
 260.282  70.569 262.695  69.044 408.695  69.044 409.516  68.584 461.516  68.584
 461.616 69.1652464.4726 69.3711  472.09 70.9845496.6172 72.0129499.5616 72.5028
508.3948 72.2045514.2836 72.5595 546.061 72.5234557.8654 72.9946582.3739 72.8195
585.3558 73.1731594.3013 73.2265617.1296 74.7004651.7933 78.1747660.7252 79.6069
663.7025 80.5884694.3762  81.992713.1653 82.0797733.9323 81.5997784.3128 81.7517
IW Dist,WD,Coef,Skew,MaxSub,Min_El,Is_Ogee,SpillHt,DesHd
16,3.65,2.5,0,0.98,, 0 ,,,3,3,
Inline Weir Flap Gates= 0

Type RM Length L Ch R = 1 ,46.7725 ,238.71,238.6,356.06
BEGIN DESCRIPTION:
DS of Goodyear's Dam
END DESCRIPTION:
XS GIS Cut Line= 4
595176.4633035995420836.82978309595037.1861035985420663.01538309
594997.4579035985420440.59658309594891.0985035985420230.19958309
#Sta/Elev= 30
       0   84.99   68.92   84.08   76.91   81.97   98.88   71.99  111.87   68.27
  190.12   68.81  203.75   71.12  222.73    66.3 257.326  65.422 263.582  63.963
 288.374  67.265 297.458  64.273 305.855  67.291 314.559   62.13 382.608  65.452
  399.68   67.49  403.68   66.58  413.12   70.47  437.67   70.21  453.67   71.59
  475.64   69.83  479.64    67.6  491.63   64.53   511.6   64.49  521.59   65.19
  532.58   69.82  549.57   71.19  560.55   74.53  605.51   80.76  684.42   80.81
#Mann= 3 , 0 , 0
       0     .12       0  190.12    .035       0  413.12     .12       0
Bank Sta=190.12,413.12
XS Rating Curve= 0 ,0
Exp/Cntr=0.3,0.1