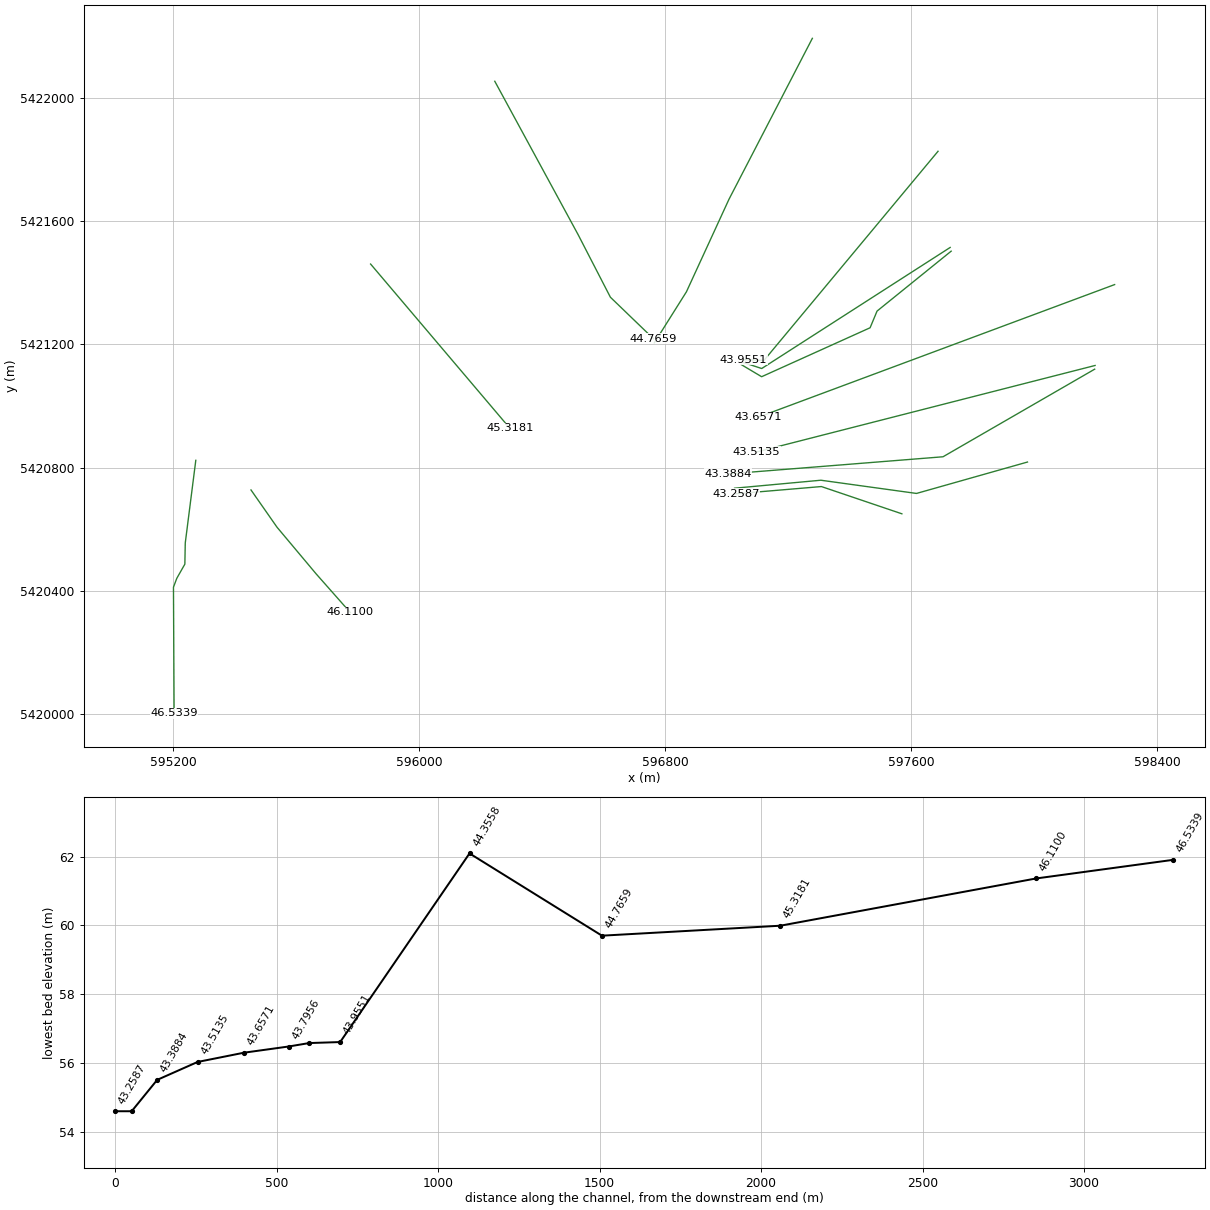
HEC-RAS study Unsteady_RAS.prj: Unsteady_RAS

--- Unsteady_RAS.g01 (geometry) --- (continued)

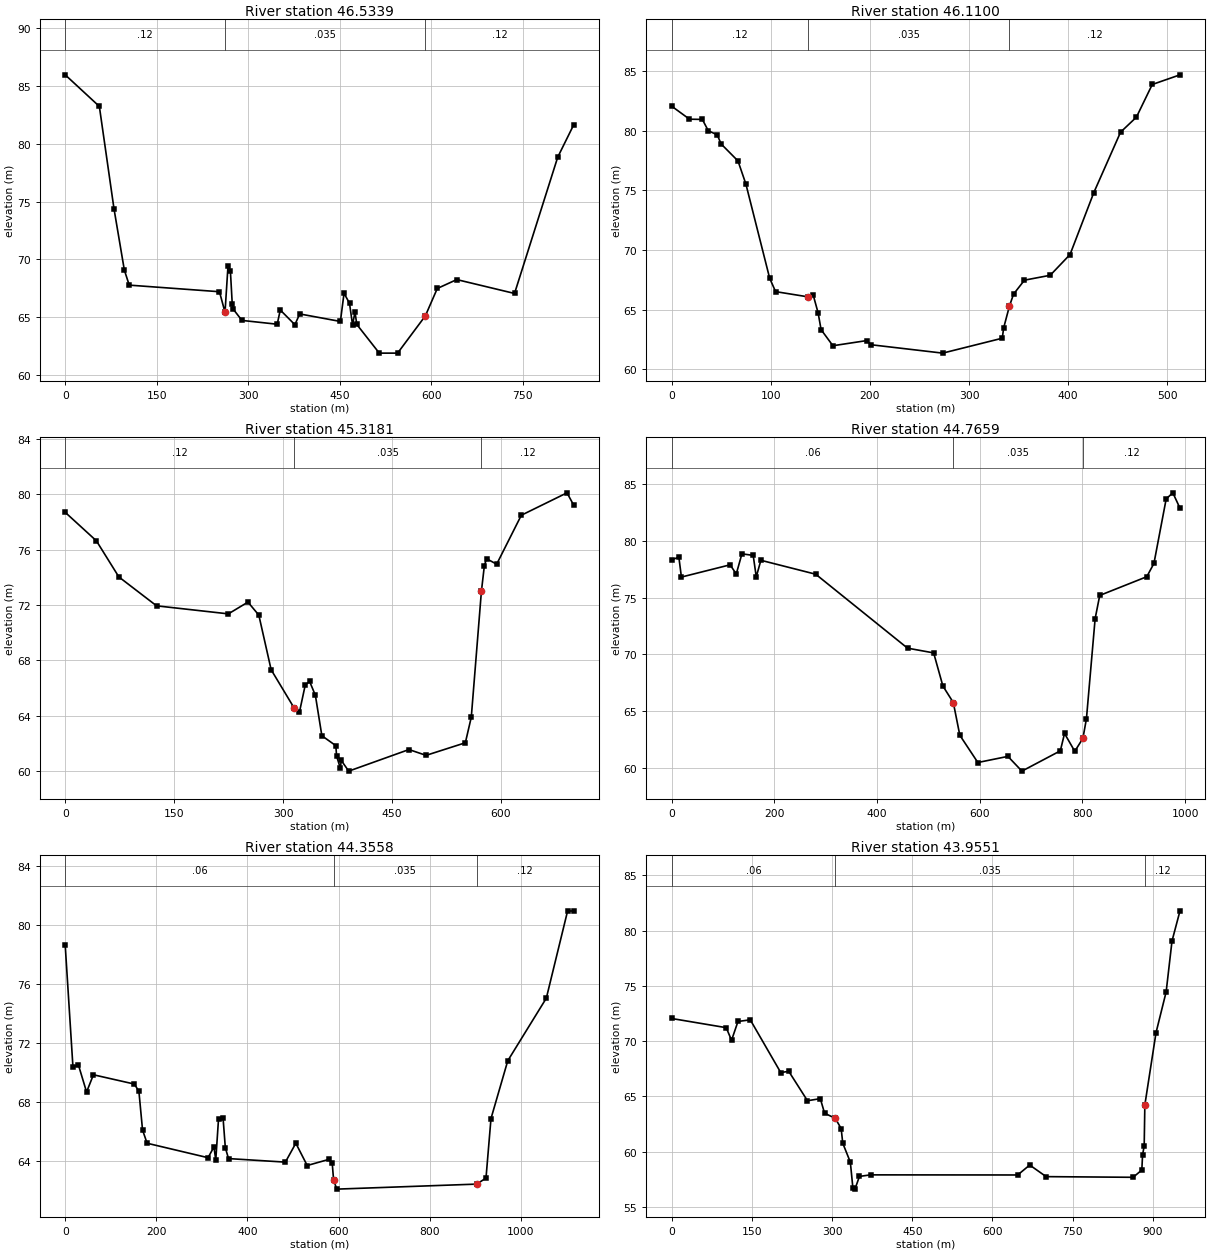
Type RM Length L Ch R = 1 ,46.5339 ,317.86,423.87,565.51
XS GIS Cut Line= 6
  595274.0180036 5420823.7344831  595239.7875036 5420555.3472831
  595238.4646036 5420486.5554831  595212.3369036 5420440.5839831
  595201.4228036 5420411.8104831  595203.4965036 5420001.7937831
#Sta/Elev= 30
       0   85.96   55.98   83.23   79.97   74.39   96.97   69.08  104.97   67.78
  252.92   67.21  262.03   65.43  266.87    69.4  270.84   69.03  273.83   66.19
  275.83   65.68  289.79   64.73  347.63    64.4  352.62   65.63  376.56   64.36
  384.54   65.29  451.21   64.64  457.19   67.08  466.16   66.21  471.14   64.34
  475.13   65.46  478.12   64.38     515  61.902     545  61.902  590.49   65.12
  610.08   67.49     642   68.26  736.74   67.06  807.55   78.84  833.48   81.61
#Mann= 3 , 0 , 0
       0     .12       0  262.03    .035       0  590.49     .12       0
Bank Sta=262.03,590.49
XS Rating Curve= 0 ,0
Exp/Cntr=0.3,0.1

Type RM Length L Ch R = 1 ,46.1100 ,800.96,791.92,793.35
BEGIN DESCRIPTION:
R07 (RIS 2013)
END DESCRIPTION:
XS GIS Cut Line= 4
595453.4822035985420727.51768309595538.1372035985420606.40498309
595665.5410035985420454.63808309595776.1744035995420329.63758309
#Sta/Elev= 30
       0   82.07   17.97   80.98   30.95   80.96   36.94   80.01   45.93   79.67
   49.92    78.9   66.89   77.48   74.88   75.54   98.84   67.65  104.83   66.52
  137.67   66.08  142.77   66.24  147.77   64.73  150.75   63.33  162.68  61.982
  196.65  62.412  201.42  62.062  273.43  61.362  333.52  62.612  334.97   63.49
  340.75    65.3  344.92   66.31  355.92   67.48   381.9   67.89   401.9   69.63
  425.88   74.82  452.87   79.89  468.87   81.15  484.86   83.89  512.85    84.7
#Mann= 3 , 0 , 0
       0     .12       0  137.67    .035       0  340.75     .12       0
Bank Sta=137.67,340.75
XS Rating Curve= 0 ,0
Exp/Cntr=0.3,0.1

Type RM Length L Ch R = 1 ,45.3181 ,604.09,552.23,528.89
BEGIN DESCRIPTION:
R08 (RIS 2013)
END DESCRIPTION:
XS GIS Cut Line= 2
595842.4030035995421461.21828309596295.4702035985420927.48878309
#Sta/Elev= 30
       0    78.7   42.94   76.64    73.9   74.03  125.84   71.94  224.71   71.36
  251.68   72.21  266.66   71.27  283.63   67.32  314.91   64.59  322.58   64.25
  330.57   66.21  336.57   66.48  344.56   65.47  353.48  62.551  372.73  61.831
  373.75  61.081  378.92  60.211  380.22  60.761  390.49  59.991  473.45  61.551
     497  61.131   551.1  62.041  559.28   63.89   573.2   72.98  577.26   74.83
  580.25   75.35  594.23   74.95  628.19   78.49  691.11   80.11   700.1   79.24
#Mann= 3 , 0 , 0
       0     .12       0  314.91    .035       0   573.2     .12       0
Bank Sta=314.91,573.2
XS Rating Curve= 0 ,0
Exp/Cntr=0.3,0.1

Type RM Length L Ch R = 1 ,44.7659 ,541.81,410.11,274.04
BEGIN DESCRIPTION:
R09 (RIS 2013)
END DESCRIPTION:
XS GIS Cut Line= 4
596246.1248035985422054.90958309596516.1615035985421558.45688309
596622.0283035985421353.49208309596761.9062035985421218.82748309
#Sta/Elev= 30
       0   78.34   13.98   78.58   18.97   76.82  113.83    77.9  125.81   77.09
  136.79   78.87  158.76   78.73  164.75   76.84  173.74    78.3  280.57   77.07
   459.3   70.55  510.23   70.13   528.2   67.21  548.52   65.75  561.15   62.87
  596.29  60.462  654.83  61.002  682.13  59.702  756.92  61.492  765.13  63.022
  785.05  61.452  800.87   62.59  807.78   64.32  824.71   73.15  833.67    75.2
  925.28   76.85  939.22   78.02  963.12   83.72  976.06   84.25     990   82.89
#Mann= 3 , 0 , 0
       0     .06       0  548.52    .035       0  800.87     .12       0
Bank Sta=548.52,800.87
XS Rating Curve= 0 ,0
Exp/Cntr=0.3,0.1

Type RM Length L Ch R = 1 ,44.3558 ,524.36,400.64,344.37
BEGIN DESCRIPTION:
First Falls
END DESCRIPTION:
XS GIS Cut Line= 4
     597278.6605     5422194.348      597007.465     5421671.309
     596869.2199     5421371.006     596764.6875     5421205.026
#Sta/Elev= 30
       0   78.62   16.98   70.37   28.96   70.51   46.93   68.67   61.91   69.84
  151.79   69.21  161.77   68.72  169.76    66.1  179.75    65.2  313.56   64.22
  326.54   64.95  330.53   64.06  336.52   66.82  346.51   66.92   351.5    64.9
  358.49   64.16  483.32   63.92  506.28    65.2  531.25   63.69  578.18    64.1
  586.17   63.85  589.17   62.71  596.16   62.09  903.41   62.43  923.75   62.84
   934.7   66.87  971.54   70.79 1056.18   75.03 1102.97   80.95 1115.92   80.93
#Mann= 3 , 0 , 0
       0     .06       0  589.17    .035       0  903.41     .12       0
Bank Sta=589.17,903.41
XS Rating Curve= 0 ,0
Exp/Cntr=0.3,0.1

Type RM Length L Ch R = 1 ,43.9551 ,196.02,95.97,20.95
BEGIN DESCRIPTION:
R11 (RIS 2013)
END DESCRIPTION:
XS GIS Cut Line= 3
597687.3123035985421827.51058309597121.5261035985421148.34858309
597054.8230035985421150.64028309
#Sta/Elev= 30
       0   72.05  101.99   71.22  111.99   70.08  123.99   71.78  146.99   71.93
  203.99   67.16  218.99   67.27  253.99   64.61  277.98    64.8  285.98   63.48
  306.01   63.02  316.98   62.09  319.98   60.77  334.15  59.054  338.84  56.754
  342.79  56.614  351.16  57.764  371.89  57.904  647.13  57.894  669.64  58.794
  700.34  57.744  863.07  57.684  879.31  58.344  880.69  59.714  883.73  60.514
  884.95   64.23  905.87   70.77   924.8   74.46  935.75   79.06   950.7   81.79
#Mann= 3 , 0 , 0
       0     .06       0  306.01    .035       0  884.95     .12       0
Bank Sta=306.01,884.95
XS Rating Curve= 0 ,0
Exp/Cntr=0.3,0.1

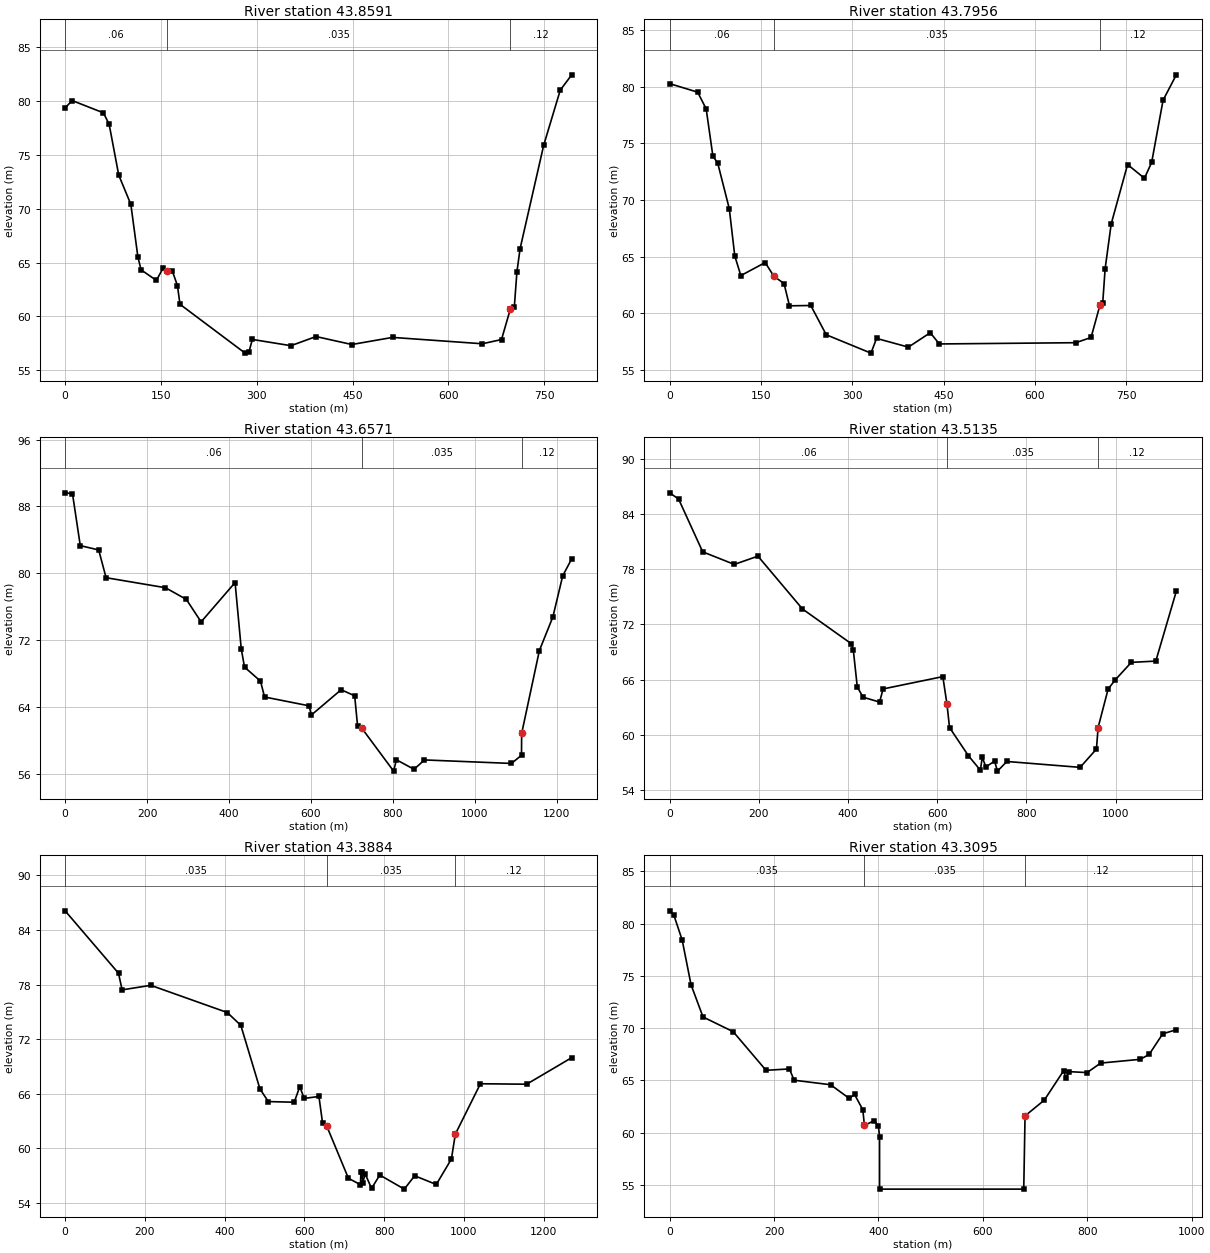
Type RM Length L Ch R = 1 ,43.8591 ,34.15,63.54,29.49
BEGIN DESCRIPTION:
Grand Falls Headpond
END DESCRIPTION:
XS GIS Cut Line= 3
597726.8547035995421515.16838309597114.0350035985421121.90268309
597052.4352035985421142.12978309
#Sta/Elev= 30
       0   79.36   10.99   80.04   59.93    78.9   68.92   77.84    83.9   73.12
  102.88    70.4  113.87   65.53  118.86   64.32  142.83   63.34  153.82   64.53
   158.8   64.22   167.8   64.21   175.8   62.86  179.79   61.12  281.73  56.585
   287.6  56.665  293.06  57.855  353.48  57.275  392.73  58.125  448.75  57.385
  512.54  58.045  652.95  57.455  683.07  57.845  697.08   60.71  703.18   60.91
  707.18   64.12  712.17   66.29   749.1   75.89  775.04   81.01  792.99   82.43
#Mann= 3 , 0 , 0
       0     .06       0   158.8    .035       0  697.08     .12       0
Bank Sta=158.8,697.08
XS Rating Curve= 0 ,0
Exp/Cntr=0.3,0.1

Type RM Length L Ch R = 1 ,43.7956 ,255.3,138.53,124.09
BEGIN DESCRIPTION:
Grand Falls Headpond
END DESCRIPTION:
XS GIS Cut Line= 6
597730.0174035985421503.06868309597489.0663035985421308.47138309
597466.4252035985421254.27068309597314.6908035995421185.86038309
597113.7601035985421095.26948309597047.5184035985421134.67348309
#Sta/Elev= 30
       0   80.27   45.96   79.52   59.95   78.04   70.94   73.88   78.93   73.25
   97.91   69.23   106.9   65.07  116.89   63.33  156.86   64.48  171.31   63.26
  187.83   62.63  196.82   60.66  231.79   60.69  257.24  58.105  330.66  56.485
  339.89  57.785  392.14  57.015  428.12  58.285  442.99  57.295  667.17  57.405
  692.32  57.865  706.87   60.71  711.42   60.87  715.41   63.93  725.39   67.89
  752.31   73.13  780.01   71.92  791.87   73.32  810.64   78.81  832.38   81.05
#Mann= 3 , 0 , 0
       0     .06       0  171.31    .035       0  706.87     .12       0
Bank Sta=171.31,706.87
XS Rating Curve= 0 ,0
Exp/Cntr=0.3,0.1

Type RM Length L Ch R = 1 ,43.6571 ,165.58,143.54,122.91
BEGIN DESCRIPTION:
Grand Falls Headpond
END DESCRIPTION:
XS GIS Cut Line= 2
598261.5275035985421394.53888309597102.5594035985420963.63818309
#Sta/Elev= 30
       0   89.62   17.99   89.52   36.98    83.3   81.97   82.78   99.96   79.46
   244.9   78.26  295.88   76.86  331.86   74.17  414.82   78.88  429.82   70.96
  437.81   68.76   476.8   67.08  486.79   65.18  595.75   64.12  600.75   63.01
  673.72   66.05   706.7   65.32   713.7   61.76  723.59   61.48  801.78  56.305
  808.51  57.665  851.57  56.525  877.09  57.645 1089.35  57.225 1113.88  58.205
 1114.24   60.81 1157.52   70.74  1190.5   74.77 1214.49   79.69 1236.48   81.72
#Mann= 3 , 0 , 0
       0     .06       0  723.59    .035       0 1114.24     .12       0
Bank Sta=723.59,1114.24
XS Rating Curve= 0 ,0
Exp/Cntr=0.3,0.1

Type RM Length L Ch R = 1 ,43.5135 ,151.21,125.11,95.9
BEGIN DESCRIPTION:
Grand Falls Headpond
END DESCRIPTION:
XS GIS Cut Line= 2
598197.9526035985421131.78898309597096.9170035985420850.66578309
#Sta/Elev= 30
       0   86.32   19.99   85.64   73.96    79.9  144.92   78.53  197.89   79.43
  297.83   73.68  406.77   69.92  411.77   69.25  420.76   65.19  433.76   64.08
  470.73   63.55  478.73   64.98  612.65   66.32  621.99   63.31  627.64   60.78
   670.1  57.706  696.87  56.136   701.1  57.536  709.31  56.496  728.71  57.126
   735.2  56.036   756.3  57.086  920.59  56.446  957.21  58.436  960.94   60.78
  983.44   64.97  999.43   65.97 1035.41   67.87 1090.38   68.01 1136.36   75.61
#Mann= 3 , 0 , 0
       0     .06       0  621.99    .035       0  960.94     .12       0
Bank Sta=621.99,960.94
XS Rating Curve= 0 ,0
Exp/Cntr=0.3,0.1

Type RM Length L Ch R = 1 ,43.3884 ,117.19,78.92,45.96
BEGIN DESCRIPTION:
Grand Falls Headpond
END DESCRIPTION:
XS GIS Cut Line= 3
598196.6806035985421119.79348309597703.5067035985420835.25138309
597004.9433035985420779.50268309
#Sta/Elev= 30
       0   86.11  133.85   79.25  142.84   77.42  214.76   77.92  406.55   74.93
  440.51   73.52  488.46   66.53  509.44   65.14  574.37   65.07  588.36   66.78
  599.36   65.49  636.35    65.7  645.35   62.82  656.23   62.42  710.29  56.706
   740.5  56.006  741.57  57.436  744.31  57.396  746.04  56.186  752.28  57.196
  768.28  55.596  788.91  57.066  850.34  55.516  876.36  56.986  930.56  56.026
  968.48  58.826  978.31   61.56 1041.23    67.1 1157.19   67.05 1270.15   69.97
#Mann= 3 , 0 , 0
       0    .035       0  656.23    .035       0  978.31     .12       0
Bank Sta=656.23,978.31
XS Rating Curve= 0 ,0
Exp/Cntr=0.3,0.1

Type RM Length L Ch R = 1 ,43.3095 ,77.56,50.84,23.88
BEGIN DESCRIPTION:
Grand Falls Headpond
END DESCRIPTION:
XS GIS Cut Line= 4
  597978.1346036 5420818.1539831  597617.2500036 5420716.1466831
  597306.4205036 5420759.0828831  597025.8009036 5420733.1719831
#Sta/Elev= 30
       0   81.22    7.98   80.81   23.94   78.42   40.89   74.15   63.83   71.07
  121.68   69.66  184.52   65.97   229.4    66.1  238.38   65.02   308.2   64.59
   344.1   63.28  354.08   63.67  370.04   62.19  373.03    60.7  392.01   61.16
  399.95    60.6   402.1  59.636  402.11  54.606  678.33  54.606  680.81   61.61
  717.78   63.12  754.76   65.93  758.76   65.25  765.75   65.84  799.73   65.75
  825.71   66.66  901.66   67.02  918.65   67.49  944.63   69.46  970.62   69.85
#Mann= 3 , 0 , 0
       0    .035       0  373.03    .035       0  680.81     .12       0
Bank Sta=373.03,680.81
XS Rating Curve= 0 ,0
Exp/Cntr=0.3,0.1

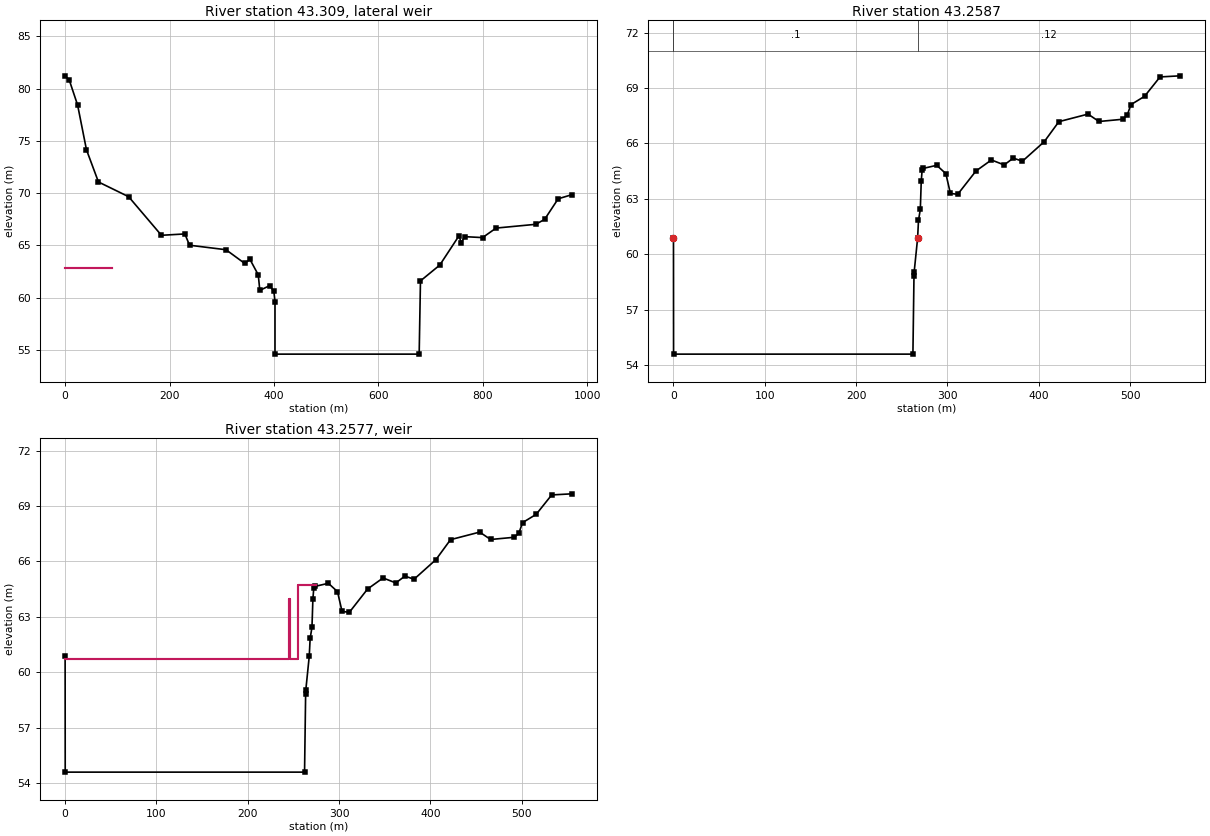
Type RM Length L Ch R = 6 ,43.309  ,,,
BEGIN DESCRIPTION:
Forebay Gate Structure
END DESCRIPTION:
Lateral Weir Pos= 1
Lateral Weir End=                ,                ,        ,Power Canal
Lateral Weir Distance=0
Lateral Weir TW Multiple XS=0
Lateral Weir WD=4
Lateral Weir Coef=1.45
LW OverFlow Method 2D=False
Lateral Weir WSCriteria=-1
Lateral Weir Flap Gates= 0
Lateral Weir Hagers EQN= 0 ,,,,,
Lateral Weir SS=0.05,0.05,
Lateral Weir Type= 0
Lateral Weir Connection Pos and Dist= 3 ,
Lateral Weir SE= 2
       0  62.826      90  62.826
Lateral Weir Centerline= 0
Lateral Weir HW RS User Defined=-1
Lateral Weir HW RS Station=43.3095,0
Lateral Weir HW RS Station=43.2587,90.01
LW Gate Name Wd,H,Inv,GCoef,Exp_T,Exp_O,Exp_H,Type,WCoef,Is_Ogee,SpillHt,DesHd,#Openings
Forebay     ,2.44,3.66,54.606,0.6,0,1,0.5, 0 ,1.67, 0 ,,, 17 ,0,0.786, 0 ,0.6,,0,0,0, 0
   16.22   19.88   23.53   27.19   30.85   34.51   38.16   41.82   45.48   50.66
   54.32   57.97   61.63   65.29   68.95    72.6   76.26
LW Div RC= 0 ,False,

Type RM Length L Ch R = 1 ,43.2587 ,255.78,14.78,12.14
BEGIN DESCRIPTION:
US of Grand Falls Main Dam
END DESCRIPTION:
XS GIS Cut Line= 3
597569.7686035985420650.02038309597308.0210035985420738.51608309
597030.5393035985420715.01628309
#Sta/Elev= 30
       0  60.906      .1  54.606   262.2  54.606  263.37  58.806  263.55  59.036
  267.33   60.87  268.32   61.84  270.32   62.44  271.32   63.96  272.31   64.57
  273.31   64.65  288.28   64.82  298.26   64.37  303.25    63.3  311.24   63.25
   331.2   64.51  348.17   65.11  362.14   64.84  372.12   65.21   382.1   65.04
  406.06    66.1  422.03   67.18  453.97   67.59  465.95   67.19   491.9   67.31
  496.89   67.53  500.88    68.1  515.85   68.55  532.82    69.6  554.78   69.66
#Mann= 3 , 0 , 0
       0    .035       0       0      .1       0  267.33     .12       0
Bank Sta=0,267.33
XS Rating Curve= 0 ,0
Exp/Cntr=0.3,0.1

Type RM Length L Ch R = 5 ,43.2577 ,,,
BEGIN DESCRIPTION:
Grand Falls Main Dam
END DESCRIPTION:
IW Pilot Flow=0
#Inline Weir SE= 8
       0  60.706   244.9  60.706   244.9  63.956  246.05  63.956  246.05  60.706
   254.9  60.706   254.9  64.706   274.9  64.706
IW Dist,WD,Coef,Skew,MaxSub,Min_El,Is_Ogee,SpillHt,DesHd
0.1,4,2.1,0,0.98,, 0 ,,,3,3,
IW Gate Name Wd,H,Inv,GCoef,Exp_T,Exp_O,Exp_H,Type,WCoef,Is_Ogee,SpillHt,DesHd,#Openings
Outside Gate,6.096,3.9624,54.602,0.59,0,1,0.5, 0 ,1.67, 0 ,,, 1 ,0,0.8, 1 ,0.59,Sluice Gate Main Dam,0,0,0, 0
      11
IW Gate Name Wd,H,Inv,GCoef,Exp_T,Exp_O,Exp_H,Type,WCoef,Is_Ogee,SpillHt,DesHd,#Openings
Obermeyer   ,8.85,1.5,59.206,,0,1,0.5, 3 ,2.1, 0 ,,, 1 ,0,0.8, 0 ,,,0,0,0, 0
 250.475
IW Gate User Curve Set=Sluice Gate Main Dam
IW Gate User Curve Set Headwater=1
 61.0208
IW Gate User Curve Set Gate Opening=13
       1       2       3       4       5       6       7       8       9      10
      11      12      13
IW Gate User Curve Set Flows
 12.431124.52239 36.3022 47.742258.8424169.5744979.9667789.9909499.64698108.9349
117.7981126.2931147.2476
Inline Weir Flap Gates= 0