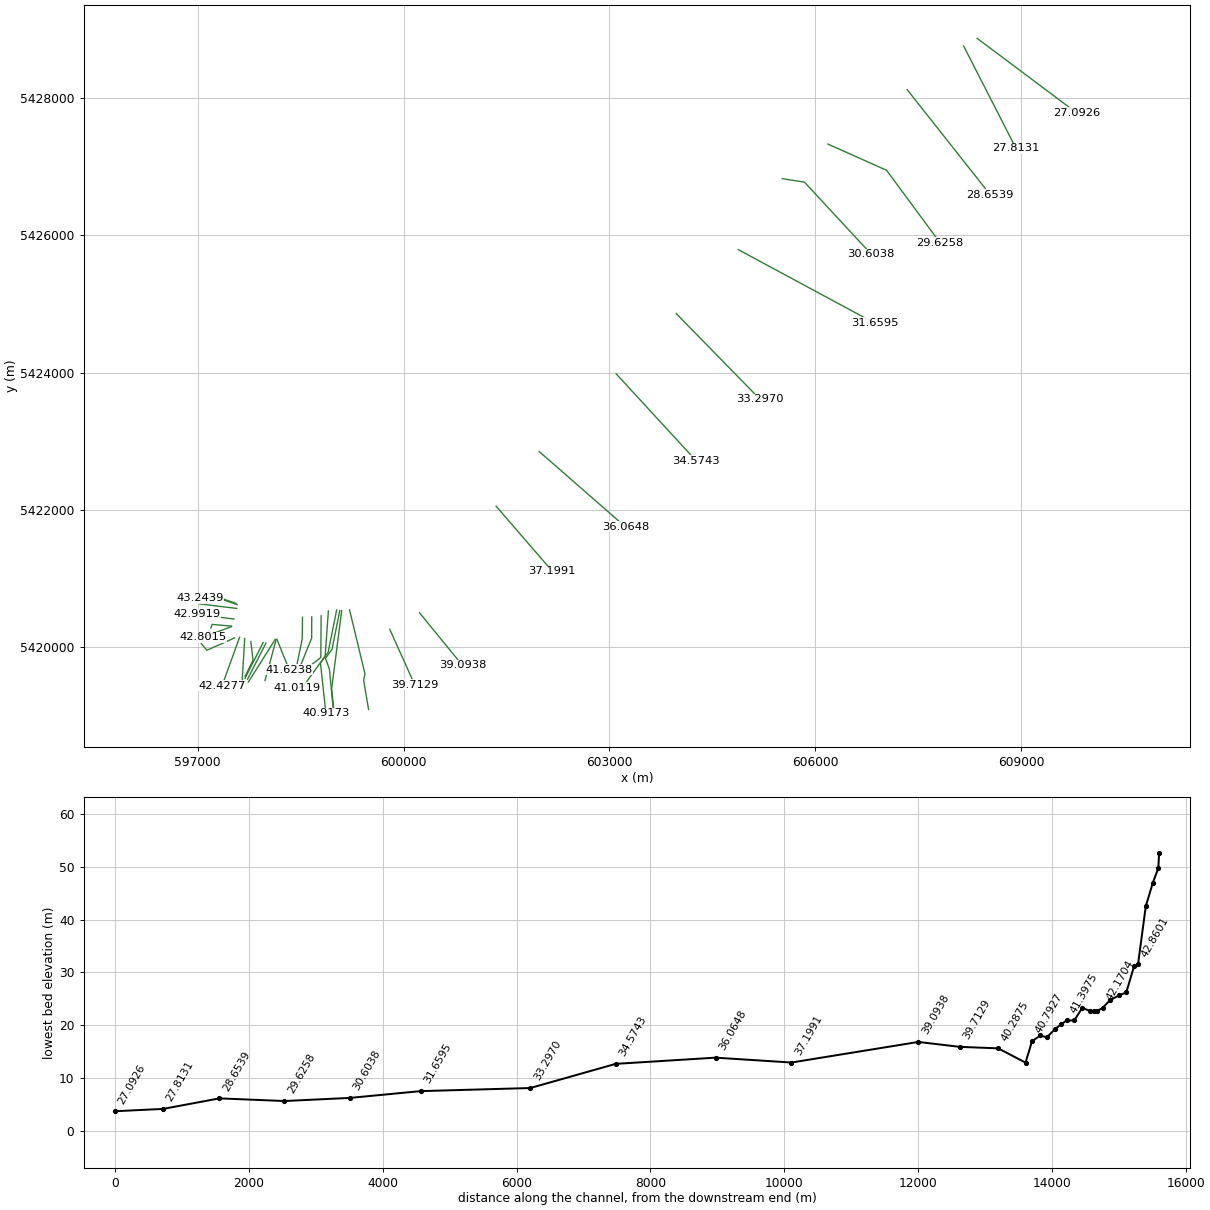
HEC-RAS study Unsteady_RAS.prj: Unsteady_RAS

--- Unsteady_RAS.g01 (geometry) --- (continued)

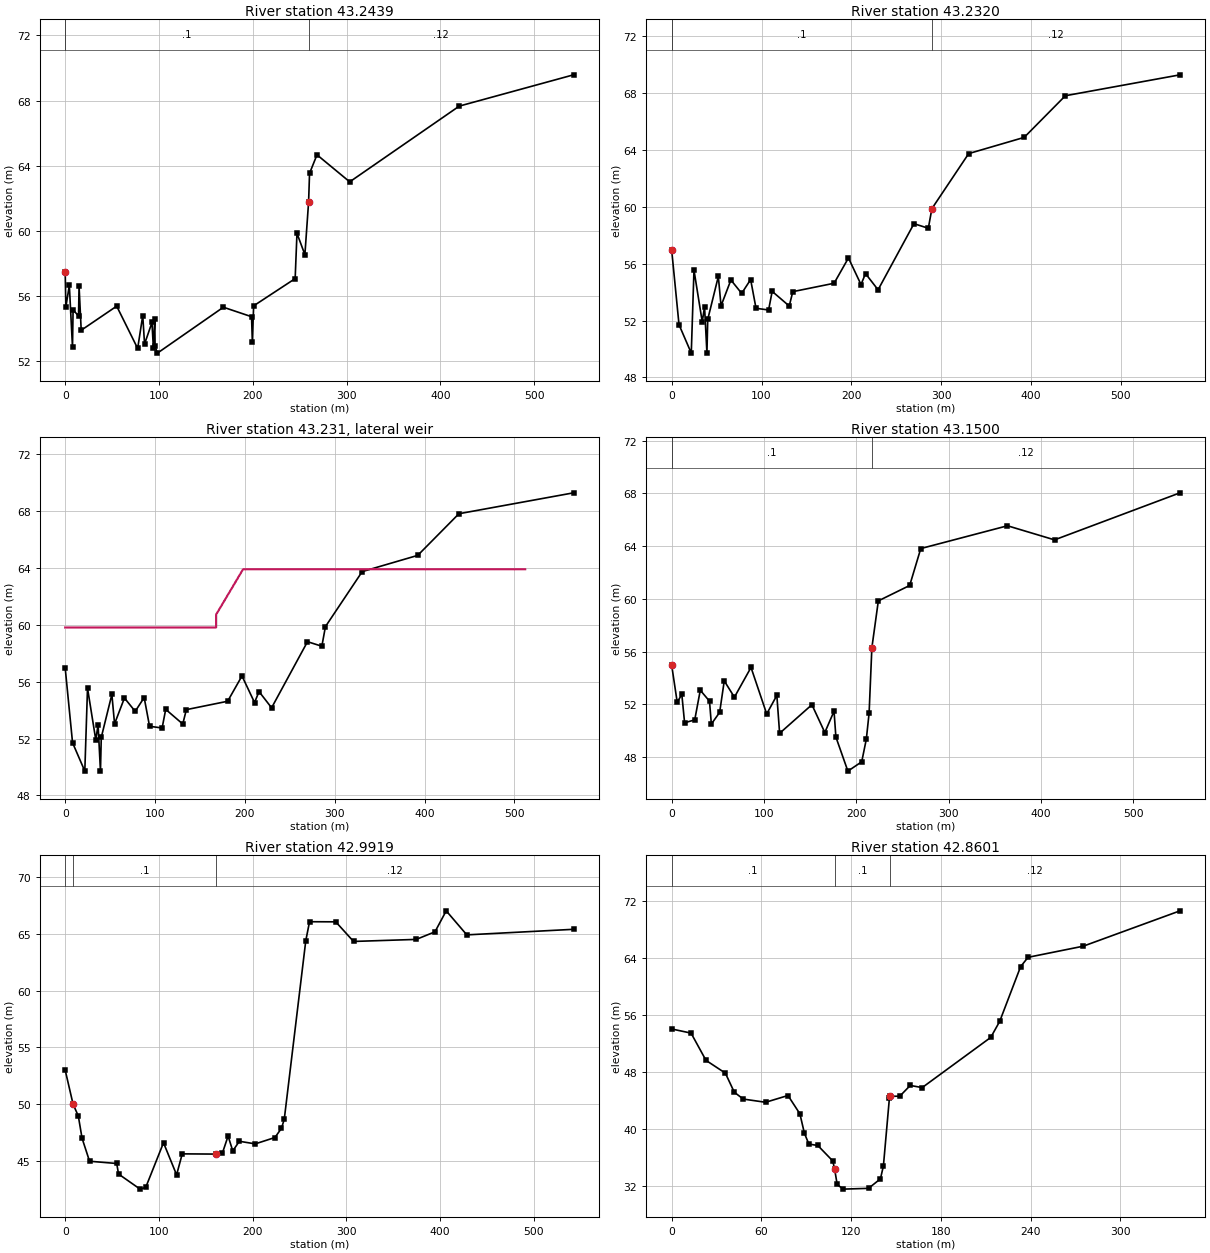
Type RM Length L Ch R = 1 ,43.2439 ,0,11.92,18.02
BEGIN DESCRIPTION:
DS of Grand Falls Main Dam
END DESCRIPTION:
XS GIS Cut Line= 4
597556.9618035985420638.48298309597407.3939035985420690.40898309
597298.9594035995420731.87748309597032.1585035995420711.26798309
#Sta/Elev= 30
       0   57.47    .676  55.321     4.4  56.658   7.776  52.852   8.393   55.15
  14.224  54.779  14.762  56.622   17.06  53.899  54.897  55.379  77.271  52.782
  82.671  54.803  84.604  53.052  92.507  54.376   94.01  52.812  95.487  54.619
   95.84  52.905  98.308  52.495 168.656  55.313 198.699  54.731 199.537  53.187
  200.93  55.398 245.194   57.07 247.125  59.852  255.57   58.54  259.53   61.78
  260.53   63.53  268.46   64.67  303.37   63.01   420.2   67.66  542.02   69.58
#Mann= 3 , 0 , 0
       0    .035       0       0      .1       0  259.53     .12       0
Bank Sta=0,259.53
XS Rating Curve= 0 ,0
Exp/Cntr=0.3,0.1

Type RM Length L Ch R = 1 ,43.2320 ,0,81.92,129.03
XS GIS Cut Line= 3
597576.9952035985420619.82858309597273.7651035985420724.04668309
597029.2998035985420705.11098309
#Sta/Elev= 30
       0   56.95    8.17  51.706   21.82  49.706   24.83  55.546   34.03  51.906
    36.6  52.966   39.25  49.706   40.14  52.076   51.94    55.1   54.94   53.03
   65.93   54.85   77.91   53.91    87.9   54.88   93.89   52.86  107.88   52.74
  111.87   54.05  130.85   53.02  134.85   54.03   180.8   54.62  196.78    56.4
  210.76   54.53  215.76    55.3  229.74   54.16   269.7   58.81  285.68   58.49
  289.67   59.87  330.61   63.74   392.4   64.88  438.25   67.81  565.84   69.28
#Mann= 3 , 0 , 0
       0    .035       0       0      .1       0  289.67     .12       0
Bank Sta=0,289.67
XS Rating Curve= 0 ,0
Exp/Cntr=0.3,0.1

Type RM Length L Ch R = 6 ,43.231  ,,,
BEGIN DESCRIPTION:
Power Canal RCC Dam and west embankment section
END DESCRIPTION:
Lateral Weir Pos= 0
Lateral Weir End=                ,                ,        ,Power Canal
Lateral Weir Distance=0
Lateral Weir TW Multiple XS=0
Lateral Weir WD=4
Lateral Weir Coef=1.65
LW OverFlow Method 2D=False
Lateral Weir WSCriteria=-1
Lateral Weir Flap Gates= 0
Lateral Weir Hagers EQN= 0 ,,,,,
Lateral Weir SS=0.05,0.05,
Lateral Weir Type= 0
Lateral Weir Connection Pos and Dist= 3 ,
Lateral Weir SE= 6
       0  59.806     168  59.806     168  60.716     198  63.906  431.39  63.906
     512  63.906
Lateral Weir Centerline= 0
Lateral Weir HW RS User Defined=-1
Lateral Weir HW RS Station=43.232,0
Lateral Weir HW RS Station=43.15,56
Lateral Weir HW RS Station=43.097*,112.3188
Lateral Weir HW RS Station=43.045*,167.575
Lateral Weir HW RS Station=42.9919,224
Lateral Weir HW RS Station=42.926*,278.5
Lateral Weir HW RS Station=42.8601,333
Lateral Weir HW RS Station=42.8015,342
Lateral Weir HW RS Station=42.749*,384.554
Lateral Weir HW RS Station=42.697*,426.7026
Lateral Weir HW RS Station=42.645*,468.8513
Lateral Weir HW RS Station=42.593,511
Lateral Weir HW RS Station=42.538*,530
LW Gate Name Wd,H,Inv,GCoef,Exp_T,Exp_O,Exp_H,Type,WCoef,Is_Ogee,SpillHt,DesHd,#Openings
Inside Gate ,4.572,2.1336,54.602,0.59,0,1,0.5, 0 ,1.67, 0 ,,, 1 ,0,0.8, 1 ,0.59,,0,0,0, 0
      10
LW Gate Name Wd,H,Inv,GCoef,Exp_T,Exp_O,Exp_H,Type,WCoef,Is_Ogee,SpillHt,DesHd,#Openings
RCC Fboards ,168,0.9,59.806,,0,1,0.5, 3 ,1.8, 0 ,,, 1 ,0,0.8, 0 ,,,0,0,0, 0
      84
LW Div RC= 0 ,False,

Type RM Length L Ch R = 1 ,43.1500 ,56.33,105.41,111.46
XS GIS Cut Line= 2
597571.8794035995420564.08708309597025.4067035985420630.16758309
#Sta/Elev= 30
       0   54.97    5.99   52.16   10.99   52.75   13.99    50.6   24.98   50.82
   30.97   53.07   40.96   52.24   42.96    50.5   51.95   51.39   56.94   53.78
   67.93   52.54   85.91    54.8   102.9   51.27  113.89   52.68  116.88    49.8
  151.85   51.97  165.84   49.86  175.83   51.48  177.82   49.52  190.81   46.93
   205.8   47.64  210.79   49.36  213.79   51.33  216.78   56.29  223.78   59.85
  257.74   61.02  269.73   63.82  363.64   65.55  414.59   64.48  550.45   68.05
#Mann= 3 , 0 , 0
       0    .035       0       0      .1       0  216.78     .12       0
Bank Sta=0,216.78
XS Rating Curve= 0 ,0
Exp/Cntr=0.3,0.1

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
Type RM Length L Ch R = 1 ,42.9919 ,159.65,115.34,119.86
XS GIS Cut Line= 2
597531.1858035985420409.68748309596992.9203035985420476.67608309
#Sta/Elev= 30
       0   52.98    8.39   49.98   13.98   48.94   17.98   46.98   25.97   44.95
   54.94   44.75   56.94   43.82   79.91   42.49   85.91   42.64  104.89   46.58
  118.87   43.75  124.87    45.6  160.71   45.58  167.82   45.69  173.81   47.17
  178.81   45.86   185.8   46.71  202.78   46.48  223.76   47.04  230.75   47.85
  233.75   48.65  256.72    64.4  260.72   66.07  288.69   66.06  307.67   64.33
   374.6   64.51  394.58   65.18  406.56   67.03  428.54   64.91  542.42    65.4
#Mann= 3 , 0 , 0
       0    .035       0    8.39      .1       0  160.71     .12       0
Bank Sta=8.39,160.71
XS Rating Curve= 0 ,0
Exp/Cntr=0.3,0.1

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
Type RM Length L Ch R = 1 ,42.8601 ,54.26,58.64,95.11
XS GIS Cut Line= 3
597495.0681035985420306.46288309597212.0706035985420331.30568309
597193.7150035985420278.68958309
#Sta/Elev= 30
       0      54   12.96   53.42   22.93    49.6   35.88   47.81   41.87   45.13
   47.85   44.17    62.8   43.72   77.75   44.67   85.72    42.1   88.71   39.39
    91.7   37.86   97.69   37.66  107.65    35.5  108.91   34.38  110.64   32.19
  114.63   31.54  131.58   31.65  139.55   32.98  141.54   34.79  145.53   44.26
  146.01   44.55  152.51   44.58  159.49   46.08  167.46   45.78  213.31   52.82
  219.29   55.07  233.25   62.74  238.23   64.05  275.11   65.61  339.81   70.57
#Mann= 3 , 0 , 0
       0      .1       0  108.91      .1       0  146.01     .12       0
Bank Sta=108.91,146.01
XS Rating Curve= 0 ,0
Exp/Cntr=0.3,0.1

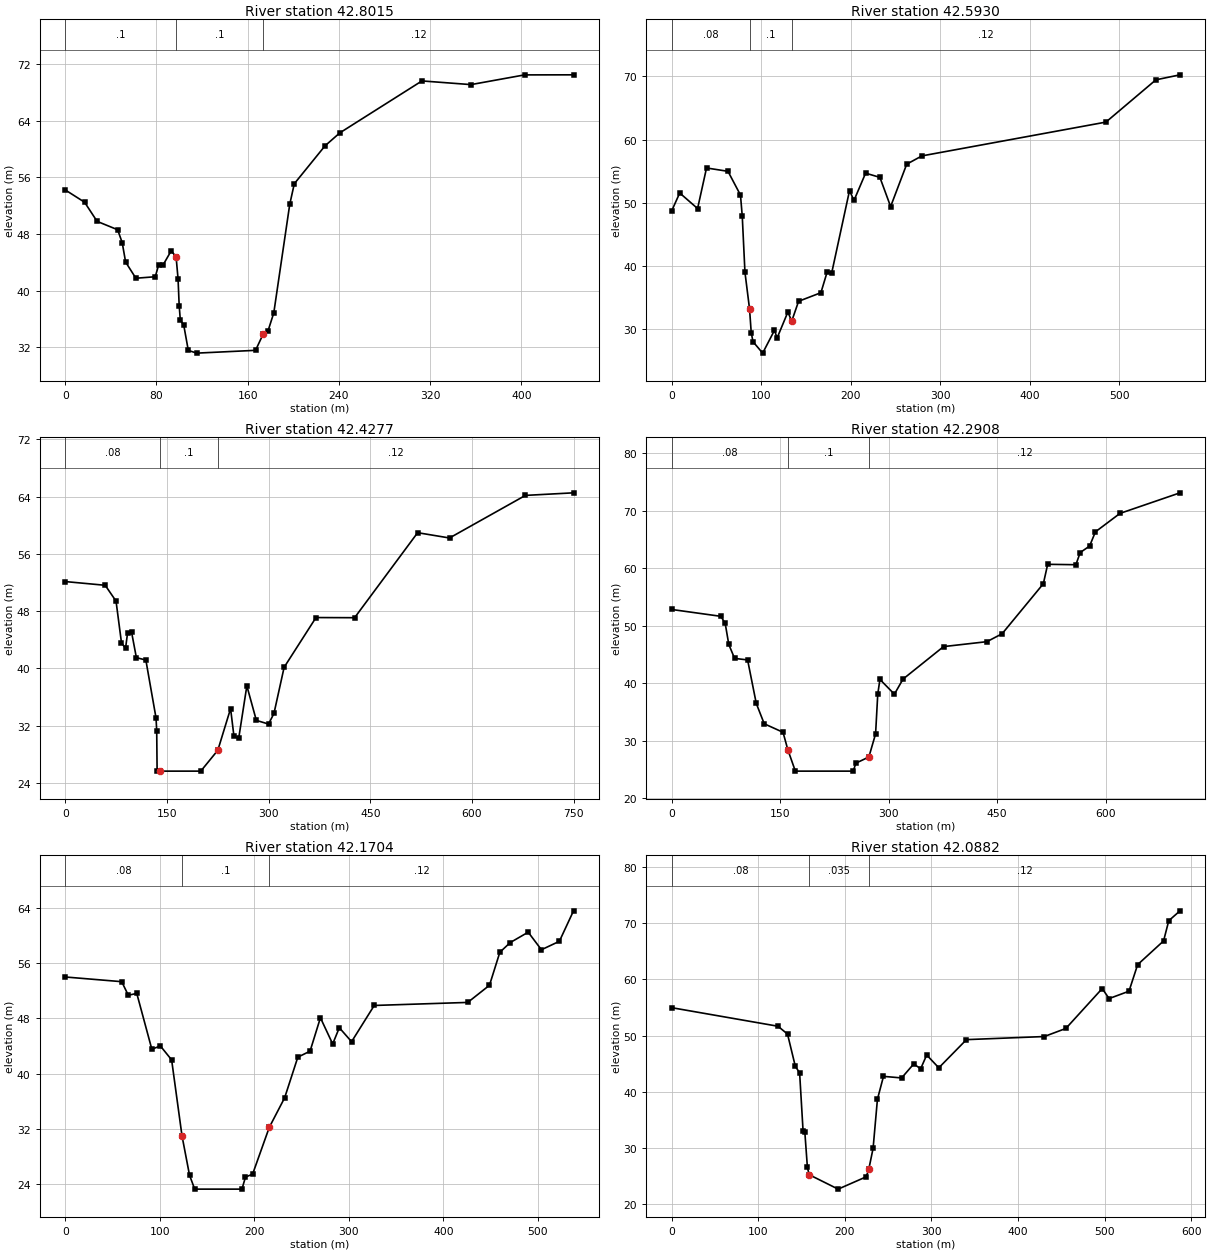
Type RM Length L Ch R = 1 ,42.8015 ,102.18,117.27,109.27
XS GIS Cut Line= 2
597492.4103035985420297.95878309597074.4635035985420142.98428309
#Sta/Elev= 30
       0   54.23   16.99   52.49   27.98   49.79   45.97   48.61   49.97    46.8
   52.97   44.05   61.97   41.77   78.96   41.98   81.95   43.65   85.95   43.68
   92.95   45.64   97.23    44.8   98.95    41.7   99.94   37.92  100.94   35.87
  103.94   35.16  107.94   31.59 115.385  31.206  166.91    31.6  173.67   33.92
   177.9   34.37   182.9   36.88  196.89   52.19  200.89    55.1  227.87   60.45
  240.87   62.28  312.83    69.6   355.8   69.08  402.78   70.45  445.75   70.46
#Mann= 3 , 0 , 0
       0      .1       0   97.23      .1       0  173.67     .12       0
Bank Sta=97.23,173.67
XS Rating Curve= 0 ,0
Exp/Cntr=0.3,0.1

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
Type RM Length L Ch R = 1 ,42.5930 ,94.2,110.19,126.55
XS GIS Cut Line= 3
597540.0600035985420134.24288309597136.0700035985419954.32478309
597055.4412035985420050.61358309
#Sta/Elev= 30
       0   48.71    8.98   51.55   28.95   49.09   38.93   55.51   62.89   54.98
   76.87   51.22   78.86   47.84   81.86      39   86.99    33.2   88.85   29.47
   90.84   28.02  101.64  26.207   114.8   29.81   117.8   28.61  129.78    32.7
  134.13   31.28  141.76   34.41  166.71   35.77   173.7   39.06  178.69   38.85
  198.66   51.93  203.65   50.37  216.63   54.69   232.6   54.02  244.58    49.4
  262.55   56.11  279.52   57.42   485.1   62.77  540.92   69.46  567.83   70.25
#Mann= 3 , 0 , 0
       0     .08       0   86.99      .1       0  134.13     .12       0
Bank Sta=86.99,134.13
XS Rating Curve= 0 ,0
Exp/Cntr=0.3,0.1

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
Type RM Length L Ch R = 1 ,42.4277 ,122.94,136.96,163.24
BEGIN DESCRIPTION:
Grand Falls Powerhouse
END DESCRIPTION:
XS GIS Cut Line= 2
597612.5543035995420143.22608309597357.4101035995419438.13158309
#Sta/Elev= 30
       0   52.14   58.99   51.62   74.98   49.41   82.98    43.6   88.98    42.8
   91.98   44.95   97.98   45.03  104.98   41.51  118.97   41.17  133.97   33.08
  134.97   31.31  135.56  25.707 139.829  25.707     140   25.65     200   25.65
  225.14   28.57  243.95   34.39  248.95   30.49  255.94   30.24  267.94   37.57
  281.94   32.74  299.93   32.23  307.93   33.71  322.93   40.16  369.92   47.11
  426.91   47.09  519.89   58.97  566.88   58.23  678.85   64.18  749.84   64.54
#Mann= 3 , 0 , 0
       0     .08       0 139.829      .1       0  225.14     .12       0
Bank Sta=139.829,225.14
XS Rating Curve= 0 ,0
Exp/Cntr=0.3,0.1

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
Type RM Length L Ch R = 1 ,42.2908 ,102.61,105.32,118.92
XS GIS Cut Line= 2
597687.2405035985420126.97068309597644.8885035985419425.34598309
#Sta/Elev= 30
       0   52.83   67.99   51.64   73.99   50.42   78.99   46.74   86.99   44.32
  104.99   44.05  116.98   36.48  127.98   32.94  153.98   31.46  160.55   28.45
     171    24.7     251    24.7  254.75  26.087  272.67   27.16  281.96   31.18
  284.96   38.08  287.96   40.66  307.96   38.09  319.95   40.72  375.95   46.37
  435.94   47.23  456.94   48.61  513.93   57.31  519.93   60.69  558.92   60.62
  564.92   62.74  577.92   63.87  585.92   66.34  619.91   69.55   702.9   73.13
#Mann= 3 , 0 , 0
       0     .08       0  160.55      .1       0  272.67     .12       0
Bank Sta=160.55,272.67
XS Rating Curve= 0 ,0
Exp/Cntr=0.3,0.1

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
Type RM Length L Ch R = 1 ,42.1704 ,99.05,82.24,54.4
XS GIS Cut Line= 3
597775.8355035995420082.58128309597808.5226035985419810.51958309
597692.5833035995419573.53828309
#Sta/Elev= 30
       0   53.99   59.79   53.31   66.76   51.35   75.73   51.61   91.67   43.53
  100.64   44.02   112.6      42  123.57   31.01  131.53   25.32     137    23.3
     187    23.3  190.75  25.042  198.29   25.47  215.93   32.24  232.17   36.51
  246.12   42.39  259.07   43.26  270.03   48.09  283.01    44.3  290.01   46.65
     303   44.63  326.98   49.87  425.92   50.31   448.9   52.79  459.89   57.57
  470.89   58.97  489.87   60.47  503.86   57.93  522.85   59.15  537.84   63.56
#Mann= 3 , 0 , 0
       0     .08       0  123.57      .1       0  215.93     .12       0
Bank Sta=123.57,215.93
XS Rating Curve= 0 ,0
Exp/Cntr=0.3,0.1

Type RM Length L Ch R = 1 ,42.0882 ,39.86,40.01,40.58
BEGIN DESCRIPTION:
US Mill Bridge
END DESCRIPTION:
XS GIS Cut Line= 2
597955.2319035995420067.01388309597690.6361035985419542.94588309
#Sta/Elev= 30
       0   54.97  122.81   51.67  133.79   50.28  142.78   44.56  147.77   43.38
  151.76   33.03  153.76   32.92  156.75   26.58  158.75   25.28 192.265  22.712
  224.65    24.9  227.74   26.31  232.63   29.97  237.63   38.68  244.62   42.76
  265.58   42.48  279.56   44.97  287.55   44.11  294.54   46.56  308.51   44.28
  340.46   49.29  430.32   49.84  455.28   51.28  497.22   58.37   505.2   56.59
  528.17    57.9  538.15   62.62  568.11   66.84   574.1   70.43  587.08   72.19
#Mann= 3 , 0 , 0
       0     .08       0  158.75    .035       0  227.74     .12       0
Bank Sta=158.75,227.74
XS Rating Curve= 0 ,0
Exp/Cntr=0.3,0.1

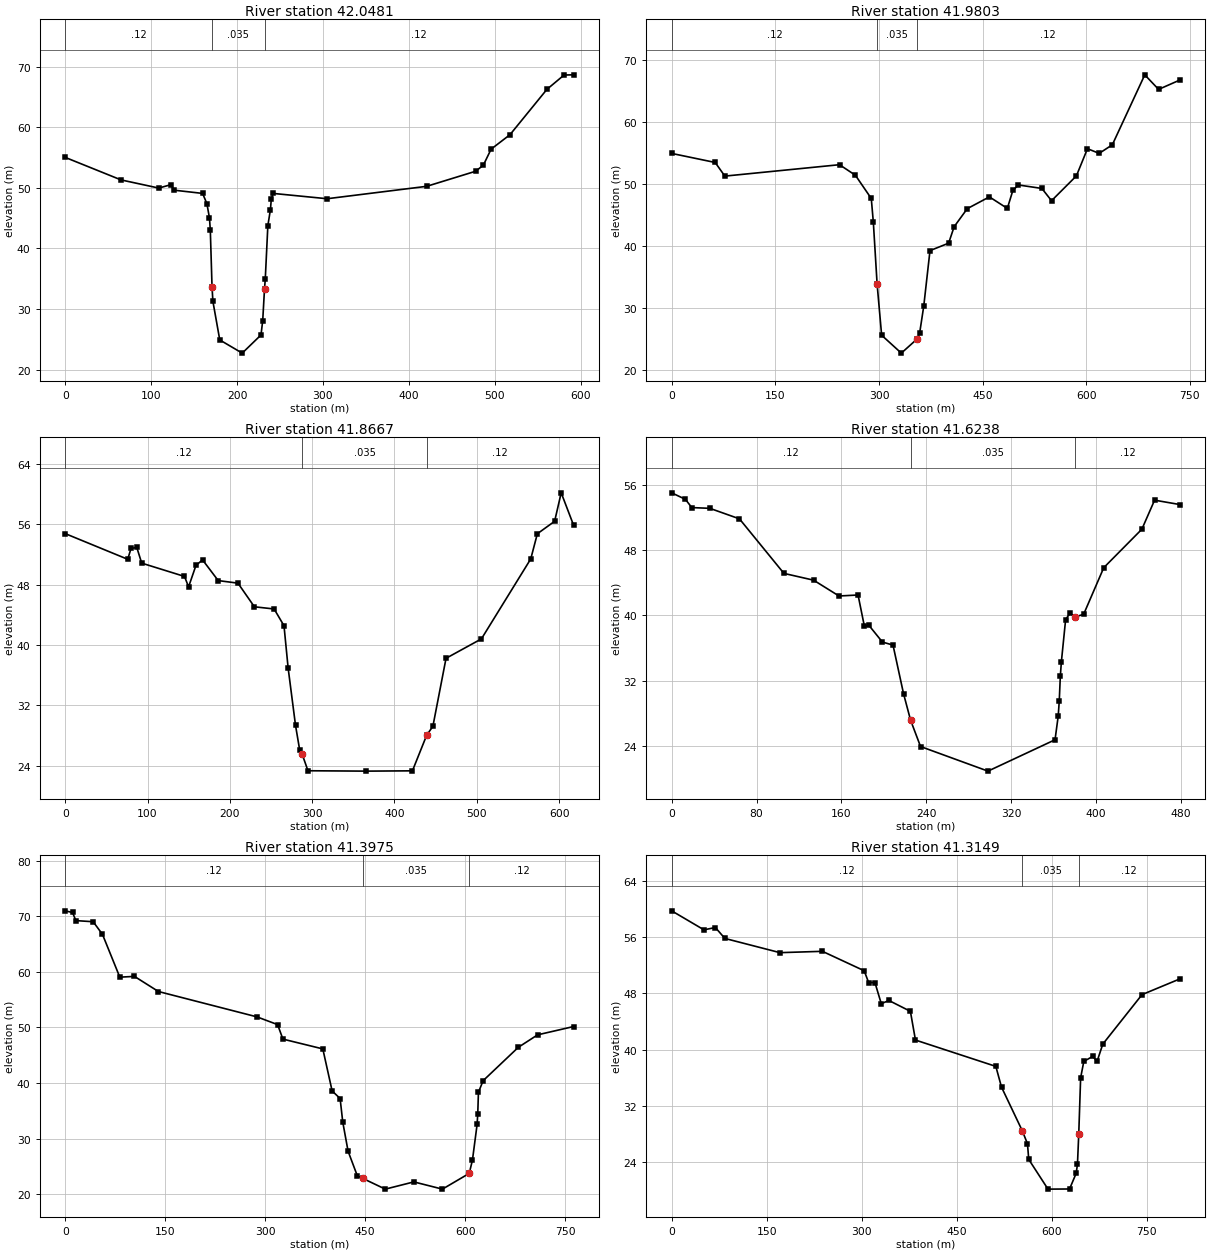
Type RM Length L Ch R = 1 ,42.0481 ,69.91,67.89,65.71
BEGIN DESCRIPTION:
DS Mill Bridge
END DESCRIPTION:
XS GIS Cut Line= 2
597997.0352035985420060.35468309597728.8329035985419533.00958309
#Sta/Elev= 30
       0   55.05   64.96   51.33  108.93   49.98  122.92   50.54  126.92   49.63
   159.9    49.1   164.9   47.41  167.89   45.05  168.89   43.03  170.89   33.66
  171.89   31.27  179.89   24.89 206.025  22.712  227.86   25.71  229.86   28.05
  231.98   33.35  232.85   34.94  235.85   43.77  238.85   46.43  239.85   48.12
  241.85    49.1  304.81   48.22  420.74   50.27   477.7   52.76  486.69   53.77
  495.69   56.41  517.67    58.8  560.65   66.29  580.64   68.66  591.63   68.69
#Mann= 3 , 0 , 0
       0     .12       0  170.89    .035       0  231.98     .12       0
Bank Sta=170.89,231.98
XS Rating Curve= 0 ,0
Exp/Cntr=0.3,0.1

Type RM Length L Ch R = 1 ,41.9803 ,105.17,113.56,170.98
XS GIS Cut Line= 2
598131.3099035985420112.89648309597740.0376035985419490.01148309
#Sta/Elev= 30
       0   54.93   62.96   53.47   76.96   51.27  242.86   53.11  265.85   51.41
  288.84   47.66  291.83   43.82   297.3   33.82  303.83    25.6 332.335  22.712
  354.62   24.94   358.8   25.92  364.79   30.31  373.79   39.25  400.77   40.45
  408.77   43.11  427.76   46.02  459.74   47.92  485.72   46.06  493.72   48.96
  501.71   49.84   535.7   49.28  549.69    47.3  585.67   51.31  601.66   55.69
  618.65   54.94  637.64   56.32  684.61   67.61   704.6   65.26  735.58   66.78
#Mann= 3 , 0 , 0
       0     .12       0   297.3    .035       0  354.62     .12       0
Bank Sta=297.3,354.62
XS Rating Curve= 0 ,0
Exp/Cntr=0.3,0.1

Type RM Length L Ch R = 1 ,41.8667 ,94.84,121.425,152.8
XS GIS Cut Line= 2
598145.1294035995420109.78868309597982.5971035995419513.98098309
#Sta/Elev= 30
       0   54.75   75.95   51.35   79.95   52.78   86.94   52.93   92.94   50.84
   144.9   49.08   149.9    47.7  158.89   50.55  166.89   51.27  185.87   48.53
  209.86   48.19  229.84   45.06  253.83   44.77  265.82   42.55  270.82   36.97
  279.81   29.36  284.81   26.14  287.96   25.52  294.93   23.35  365.47    23.3
  421.85   23.34  439.22   28.07   446.7   29.23  462.68   38.24  505.66   40.81
  565.61    51.4  573.61   54.73  594.59   56.38  602.59   60.15  617.58   55.88
#Mann= 3 , 0 , 0
       0     .12       0  287.96    .035       0  439.22     .12       0
Bank Sta=287.96,439.22
XS Rating Curve= 0 ,0
Exp/Cntr=0.3,0.1

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
Type RM Length L Ch R = 1 ,41.6238 ,150.015,113.19,92.86
XS GIS Cut Line= 2
  598156.4052036 5420113.0567831  598336.5925036 5419668.8636831
#Sta/Elev= 30
       0   55.04   12.98   54.24   18.97   53.23   35.95   53.14   63.91   51.85
  105.86   45.16  133.82   44.33  157.79   42.39  175.76   42.51  181.75   38.66
  185.75   38.83  198.73   36.74  208.72   36.37   218.7   30.38  225.31   27.15
  234.68   23.93 298.275  20.914  361.51   24.76  364.51   27.67   365.5   29.54
   366.5   32.55   367.5   34.34   371.5    39.5  375.49   40.25  380.76   39.84
  388.47   40.14  407.45   45.86   443.4   50.58  455.38   54.14  479.35    53.6
#Mann= 3 , 0 , 0
       0     .12       0  225.31    .035       0  380.76     .12       0
Bank Sta=225.31,380.76
XS Rating Curve= 0 ,0
Exp/Cntr=0.3,0.1

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
Type RM Length L Ch R = 1 ,41.3975 ,123.69,82.54,74.28
XS GIS Cut Line= 3
  598528.7382036 5420435.1340831  598524.4723036 5420116.4904831
  598434.5741036 5419681.6617831
#Sta/Elev= 30
       0   70.96   10.99   70.66   15.98    69.2   41.96      69   55.94   66.72
   81.92   59.03  103.89   59.17  139.86   56.45   287.7   51.89  318.67    50.5
  326.66   47.89  386.52   46.13  400.49   38.57  412.47   37.21  416.46   32.96
  424.44   27.73  438.41   23.27  446.16   22.86  480.27  20.914  523.13  22.214
  565.99  20.914  606.19   23.74  611.03   26.14  618.02   32.55  619.01   34.49
  620.01   38.32     627   40.41  679.88   46.42  708.82   48.66   762.7   50.15
#Mann= 3 , 0 , 0
       0     .12       0  446.16    .035       0  606.19     .12       0
Bank Sta=446.16,606.19
XS Rating Curve= 0 ,0
Exp/Cntr=0.3,0.1

Type RM Length L Ch R = 1 ,41.3149 ,99.285,88.355,80.53
XS GIS Cut Line= 3
  598663.5854036 5420441.1382831  598662.2569036 5420130.2724831
  598477.5198036 5419674.8176831
#Sta/Elev= 30
       0   59.71   50.98   57.01   68.97   57.34   83.96   55.79  170.93   53.77
   237.9   53.96  303.87    51.2  310.87   49.53  320.86   49.52  330.85   46.52
  342.84   46.98   376.8   45.44  384.79   41.36  511.66   37.62  520.65   34.67
  553.45   28.47  561.61   26.63  563.61   24.41  593.99   20.19  628.03   20.21
  638.53   22.45  640.53   23.76  642.53   27.98  645.52      36  650.52   38.32
   664.5   39.04   671.5   38.34  680.49   40.78  742.42   47.81  802.36   50.05
#Mann= 3 , 0 , 0
       0     .12       0  553.45    .035       0  642.53     .12       0
Bank Sta=553.45,642.53
XS Rating Curve= 0 ,0
Exp/Cntr=0.3,0.1

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
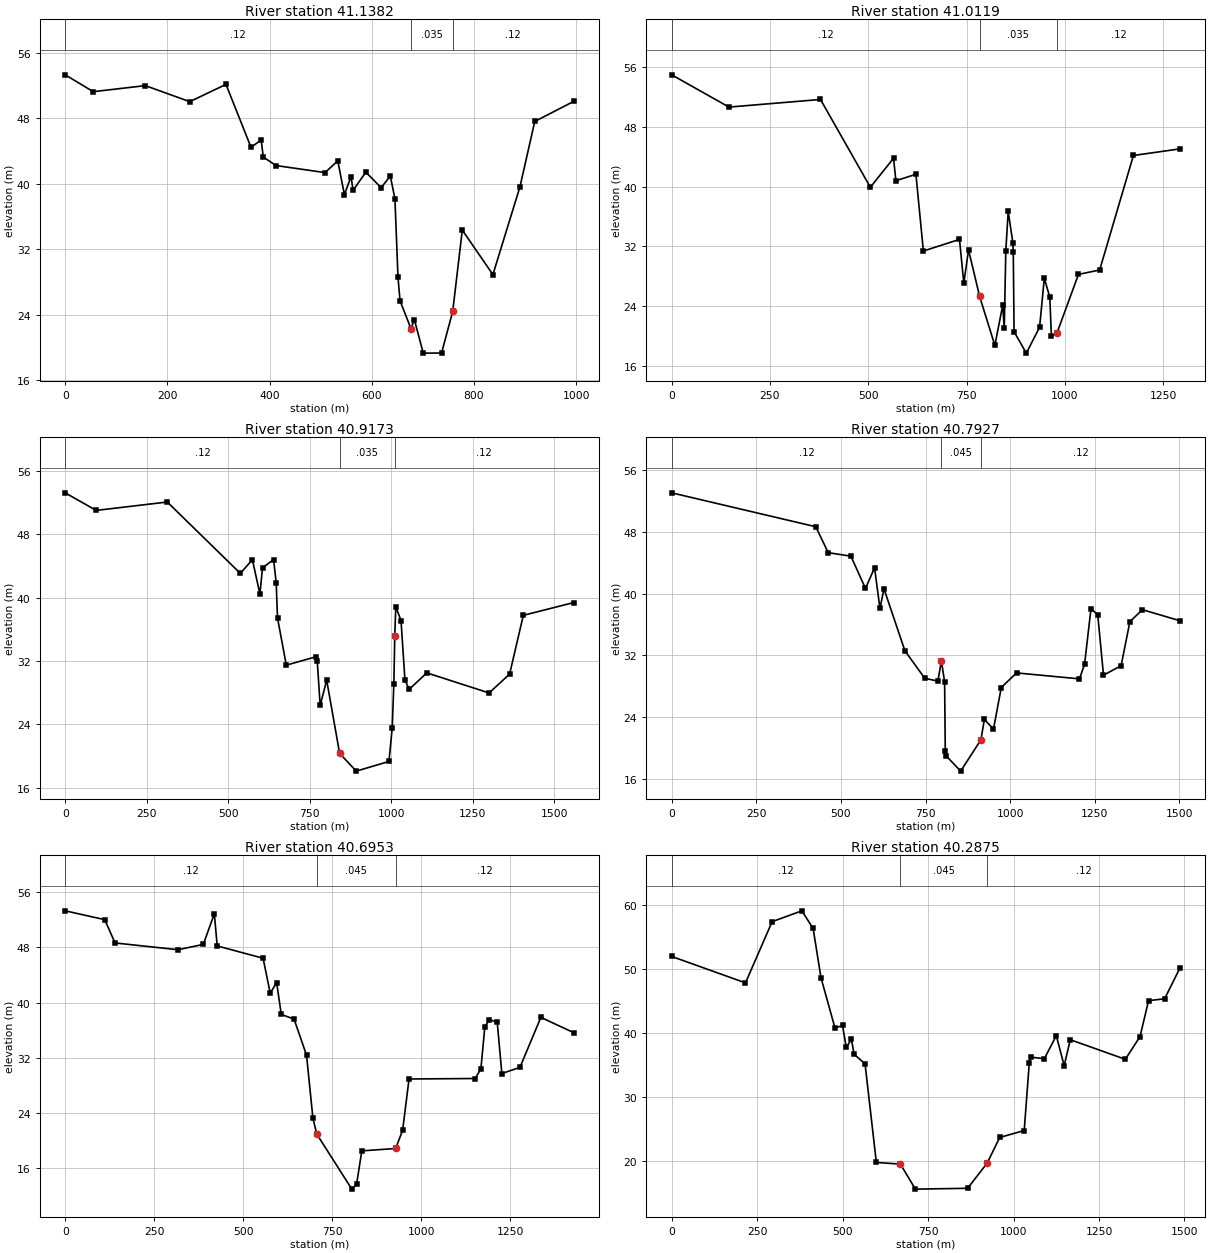
Type RM Length L Ch R = 1 ,41.1382 ,63.25,126.28,148.07
XS GIS Cut Line= 3
  598800.5850036 5420456.0698831  598795.8666036 5419849.6393831
  598489.4724036 5419610.6914831
#Sta/Elev= 30
       0   53.32   54.95   51.26  156.86      52  243.78   50.04  314.71   52.15
  363.67   44.46  383.65   45.36  387.65   43.27  412.62   42.23  508.54   41.37
  533.52    42.8   546.5   38.68  559.49   40.88  563.49    39.2  588.47   41.42
  618.44   39.53  636.41   40.95   645.4   38.17   651.4   28.57  655.39    25.7
  676.79   22.29  683.36   23.41  700.87    19.3  736.68   19.31  758.51    24.4
  777.25   34.34  837.18    28.9  890.12   39.63  919.09   47.62     995   50.06
#Mann= 3 , 0 , 0
       0     .12       0  676.79    .035       0  758.51     .12       0
Bank Sta=676.79,758.51
XS Rating Curve= 0 ,0
Exp/Cntr=0.3,0.1

Type RM Length L Ch R = 1 ,41.0119 ,22.93,94.61,179.55
XS GIS Cut Line= 4
  598905.8685036 5420527.1683831  598858.6945036 5419869.8341831
  598539.9867036 5419427.5964831  598454.2653036 5419405.6642831
#Sta/Elev= 30
       0   54.99  145.78   50.67  378.44   51.69  505.25   39.93  564.17   43.82
  570.16   40.81  621.08   41.67  640.05   31.39  731.91   32.95  742.89   27.07
  754.87   31.55  783.07   25.31  821.82  18.745  841.73   24.12  845.72   21.05
  849.71   31.45   855.7    36.7  867.68   32.48  868.68   31.22  870.68   20.58
  901.83  17.715  935.57   21.18  947.55   27.74  961.53   25.22  965.52   20.07
  979.56   20.38 1034.41   28.26 1088.32   28.85 1174.18   44.19 1292.62   45.07
#Mann= 3 , 0 , 0
       0     .12       0  783.07    .035       0  979.56     .12       0
Bank Sta=783.07,979.56
XS Rating Curve= 0 ,0
Exp/Cntr=0.3,0.1

Type RM Length L Ch R = 1 ,40.9173 ,104.51,124.65,154.26
XS GIS Cut Line= 4
  599026.1086036 5420540.6695831  598902.4502036 5419926.0542831
  598790.4353036 5419769.2360831  598869.5036036 5419034.6033831
#Sta/Elev= 30
       0   53.22   94.99      51  312.97   52.06  536.94   43.05  573.94   44.78
  596.94   40.45  604.93   43.75  638.91   44.79   646.9   41.87   650.9   37.43
  677.86   31.46  767.73   32.51  772.72   32.01  781.71   26.38  801.68   29.57
  841.38   20.32  892.32   18.08  992.62    19.3 1002.62   23.53 1007.62   29.14
 1010.45   35.17 1013.61   38.83 1029.61   37.08 1041.61   29.61 1054.61    28.4
  1108.6   30.49 1299.58   27.95 1362.57   30.33 1404.56   37.75 1558.54   39.36
#Mann= 3 , 0 , 0
       0     .12       0  841.38    .035       0 1010.45     .12       0
Bank Sta=841.38,1010.45
XS Rating Curve= 0 ,0
Exp/Cntr=0.3,0.1

Type RM Length L Ch R = 1 ,40.7927 ,135.24,97.35,89.19
XS GIS Cut Line= 5
  599071.2521036 5420532.4645831  598959.0884036 5419969.0653831
  598863.4854036 5419835.5306831  598920.5291036 5419682.8368831
  598977.4507036 5419085.5791831
#Sta/Elev= 30
       0   53.04   425.6   48.65  462.56   45.29   529.5   44.84  572.46   40.67
  599.34   43.33  615.26   38.08  627.21   40.61  688.92    32.6  747.63   29.03
  786.39   28.67   796.8   31.28  806.27   28.57  808.26   19.59  810.24   19.02
 853.695  17.016  913.63   21.08  923.68    23.7  950.68   22.46  973.68   27.84
 1018.68   29.73 1204.66   28.96 1219.66   30.84 1238.66   38.04 1258.66   37.25
 1275.65   29.44 1327.65   30.66 1353.65   36.37 1390.64   37.91 1501.64   36.48
#Mann= 3 , 0 , 0
       0     .12       0   796.8    .045       0  913.63     .12       0
Bank Sta=796.8,913.63
XS Rating Curve= 0 ,0
Exp/Cntr=0.3,0.1

Type RM Length L Ch R = 1 ,40.6953 ,368.69,407.83,456.42
BEGIN DESCRIPTION:
R13 (RIS 2013)
END DESCRIPTION:
XS GIS Cut Line= 3
  599099.2065036 5420529.6327831  598954.0399036 5419398.3266831
  598982.9888036 5419112.7675831
#Sta/Elev= 30
       0   53.31  110.96   52.03  139.95   48.65  316.88   47.67  387.86   48.44
  418.85   52.89  426.84   48.22   555.8   46.43  575.79   41.36  593.78   42.91
  606.78   38.29  642.76    37.6  677.75   32.37  695.75   23.21   706.6   20.92
  804.92  12.946  818.38  13.676  833.05  18.496  928.07   18.84  947.65   21.49
  965.65   28.92 1151.55   28.99 1167.49   30.41 1178.46   36.48 1191.41   37.54
 1213.34   37.13 1226.29   29.71 1277.12   30.61 1335.92   37.86 1427.61   35.65
#Mann= 3 , 0 , 0
       0     .12       0   706.6    .045       0  928.07     .12       0
Bank Sta=706.6,928.07
XS Rating Curve= 0 ,0
Exp/Cntr=0.3,0.1

Type RM Length L Ch R = 1 ,40.2875 ,574.92,574.64,644.45
BEGIN DESCRIPTION:
R14 (RIS 2013)
END DESCRIPTION:
XS GIS Cut Line= 4
599214.1084035985420543.04368309599438.2531035985419613.21718309
599419.7029035995419515.35288309599491.4356035985419090.56948309
#Sta/Elev= 30
       0   51.91  215.88   47.79  293.83   57.33  380.79   59.02  413.77   56.27
  436.75   48.59  477.73   40.75  499.72   41.15  510.71   37.74   525.7   38.98
   533.7   36.67  565.68   35.16  598.66    19.8  669.01   19.55  712.83  15.647
  865.61  15.777  922.84    19.7  959.46    23.7 1031.17   24.78 1046.11   35.38
  1050.1   36.22 1090.06   35.97 1125.04   39.57 1148.03   34.88 1166.02   38.93
 1326.94   35.88 1369.92   39.42  1394.9   45.02 1441.88   45.31 1486.86   50.13
#Mann= 3 , 0 , 0
       0     .12       0  669.01    .045       0  922.84     .12       0
Bank Sta=669.01,922.84
XS Rating Curve= 0 ,0
Exp/Cntr=0.3,0.1

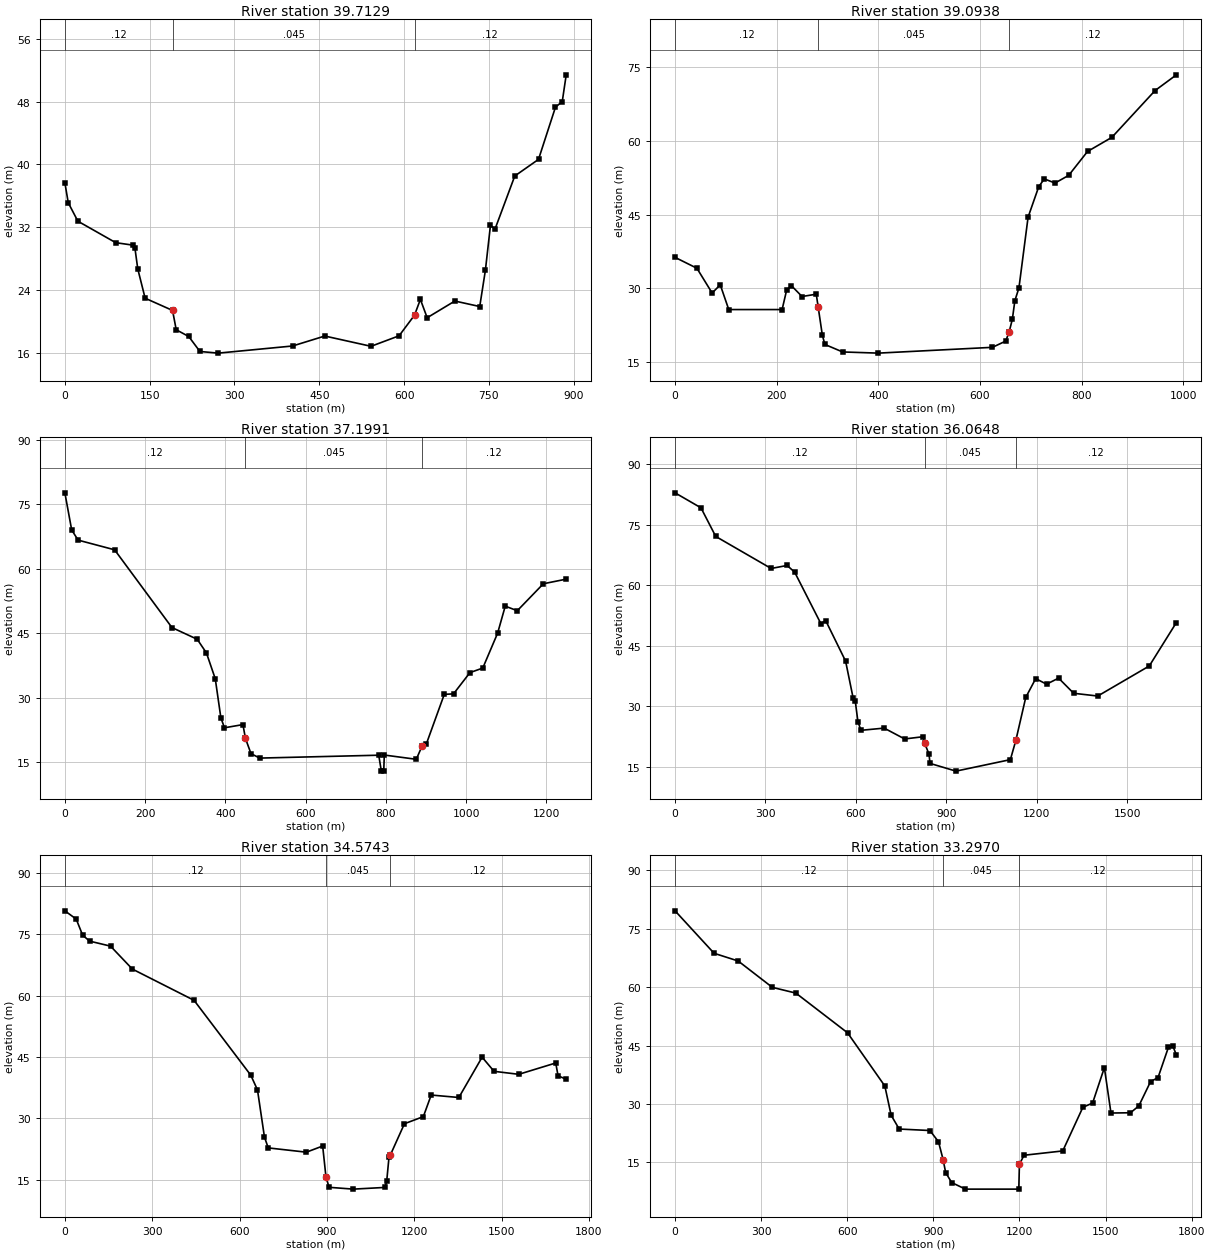
Type RM Length L Ch R = 1 ,39.7129 ,581.88,619.1,724.22
BEGIN DESCRIPTION:
Gorge Park - R15 (RIS 2013)
END DESCRIPTION:
XS GIS Cut Line= 2
599798.9278035985420261.30898309600162.7547035985419452.58748309
#Sta/Elev= 30
       0   37.66       6    35.1   22.99   32.75   89.98   30.01  120.97   29.69
  123.97    29.3  128.97   26.67  141.97   22.93   190.5   21.37  196.95   18.91
  219.12  18.048  238.91  16.138  271.27  15.928  402.76  16.838  459.76  18.108
   541.6  16.798  591.18  18.138  618.51   20.77  628.85   22.78  640.85   20.44
  689.84   22.57  733.83   21.87  743.83   26.48  752.82   32.23  760.82   31.73
  795.81   38.51   837.8   40.63   867.8   47.29   879.8      48  886.79   51.41
#Mann= 3 , 0 , 0
       0     .12       0   190.5    .045       0  618.51     .12       0
Bank Sta=190.5,618.51
XS Rating Curve= 0 ,0
Exp/Cntr=0.3,0.1

Type RM Length L Ch R = 1 ,39.0938 ,1968.28,1894.64,1905.81
BEGIN DESCRIPTION:
Grand Falls Wastewater Treatment Facility - R16 (RIS 2013)
END DESCRIPTION:
XS GIS Cut Line= 2
600233.6252035985420499.83648309600857.4626035985419735.54198309
#Sta/Elev= 30
       0   36.33   42.98   34.12   72.97   29.08   88.96   30.75  105.68  25.717
  210.66  25.717  219.69  29.717   228.9   30.58  249.89   28.37  277.88   28.84
  281.69    26.2  289.87   20.49  294.87   18.62  329.73  17.097  399.88  16.857
  624.63  18.037  650.72   19.31  657.48   21.19  663.71   23.73  668.71   27.52
  676.71   30.12   694.7    44.5  715.69   50.71  726.69   52.29  747.68   51.44
  774.67   53.01  811.65   57.86  859.63   60.74   944.6   70.25  986.58   73.45
#Mann= 3 , 0 , 0
       0     .12       0  281.69    .045       0  657.48     .12       0
Bank Sta=281.69,657.48
XS Rating Curve= 0 ,0
Exp/Cntr=0.3,0.1

Type RM Length L Ch R = 1 ,37.1991 ,1163.25,1134.34,1181.21
BEGIN DESCRIPTION:
R17 (RIS 2013)
END DESCRIPTION:
XS GIS Cut Line= 2
601348.7466035985422054.15248309602165.4492035985421108.26418309
#Sta/Elev= 30
       0   77.64      17   69.02   32.99   66.65  123.97    64.4  266.93   46.33
  329.92   43.61  352.91   40.43   374.9   34.43   388.9   25.35   397.9   23.04
  443.89   23.78  450.13   20.57  463.94  17.037   485.7  15.997  782.41  16.667
  788.66  13.057  794.85  12.967  796.27  16.707  875.96  15.717  890.69   18.86
  900.77   19.21  945.76   30.81  968.75   30.92 1009.74   35.86 1041.73   36.92
 1078.72   45.03 1097.72   51.31 1127.71   50.24  1192.7   56.51 1249.68   57.58
#Mann= 3 , 0 , 0
       0     .12       0  450.13    .045       0  890.69     .12       0
Bank Sta=450.13,890.69
XS Rating Curve= 0 ,0
Exp/Cntr=0.3,0.1

Type RM Length L Ch R = 1 ,36.0648 ,1505.09,1490.5,1521.76
BEGIN DESCRIPTION:
R18 (RIS 2013)
END DESCRIPTION:
XS GIS Cut Line= 2
601977.4418035985422849.76258309603229.9842035985421755.09568309
#Sta/Elev= 30
       0   82.94   85.97   79.22  134.96   72.12   318.9   64.17  371.88   64.92
  396.88   63.25  483.85   50.48  499.84   51.24  565.82   41.19  590.81   32.05
  597.81   31.31  606.81   26.14  616.81   24.01  693.78   24.56  761.76   21.87
  823.74   22.43  828.53   20.75  842.73   18.07  845.86  15.806  932.16  13.886
 1112.65   16.74  1130.8   21.53 1163.63   32.18 1196.62   36.84 1232.61   35.46
  1272.6   36.96 1322.58    33.2 1402.55   32.52  1573.5   39.98 1663.47   50.76
#Mann= 3 , 0 , 0
       0     .12       0  828.53    .045       0  1130.8     .12       0
Bank Sta=828.53,1130.8
XS Rating Curve= 0 ,0
Exp/Cntr=0.3,0.1

Type RM Length L Ch R = 1 ,34.5743 ,1277.25,1277.25,1303.61
XS GIS Cut Line= 2
603096.5604035985423984.08028309604262.4876035985422716.83918309
#Sta/Elev= 30
       0   80.79   38.98   78.77   60.96   74.85   84.95   73.38  156.91   72.15
  231.87   66.54  443.74    58.9  638.63   40.58  661.62   36.98   685.6   25.43
   698.6    22.8  829.52   21.75  885.49   23.26  896.75   15.75  907.48   13.16
  990.71  12.715 1099.37   13.13 1105.36    14.6 1113.36   20.55 1118.34   21.12
 1166.32   28.71 1231.29   30.45 1258.27   35.73 1353.21   35.13 1433.16   44.99
 1474.14   41.53 1559.08    40.8 1686.01   43.57    1694   40.44 1721.98   39.59
#Mann= 3 , 0 , 0
       0     .12       0  896.75    .045       0 1118.34     .12       0
Bank Sta=896.75,1118.34
XS Rating Curve= 0 ,0
Exp/Cntr=0.3,0.1

Type RM Length L Ch R = 1 ,33.2970 ,1594.23,1637.46,1749.33
BEGIN DESCRIPTION:
R20 (RIS 2013)
END DESCRIPTION:
XS GIS Cut Line= 2
603972.1877035985424861.26948309605192.9212035985423611.68818309
#Sta/Elev= 30
       0   79.59  135.99   68.69  219.99   66.71  338.98   59.94  420.98   58.47
  600.97   48.28  730.96   34.62  752.96   27.11  780.96   23.57  887.95   23.19
  917.95   20.31  933.89   15.75  942.97  12.384   963.8   9.834  1011.7   8.144
 1197.74   8.144 1199.93   14.52 1215.93   16.84 1350.92   17.95 1420.92   29.14
 1454.92   30.25 1495.91   39.33 1518.91   27.68 1586.91   27.75  1615.9    29.5
  1656.9   35.75  1682.9   36.78  1718.9   44.51  1733.9   44.97  1746.9   42.59
#Mann= 3 , 0 , 0
       0     .12       0  933.89    .045       0 1199.93     .12       0
Bank Sta=933.89,1199.93
XS Rating Curve= 0 ,0
Exp/Cntr=0.3,0.1

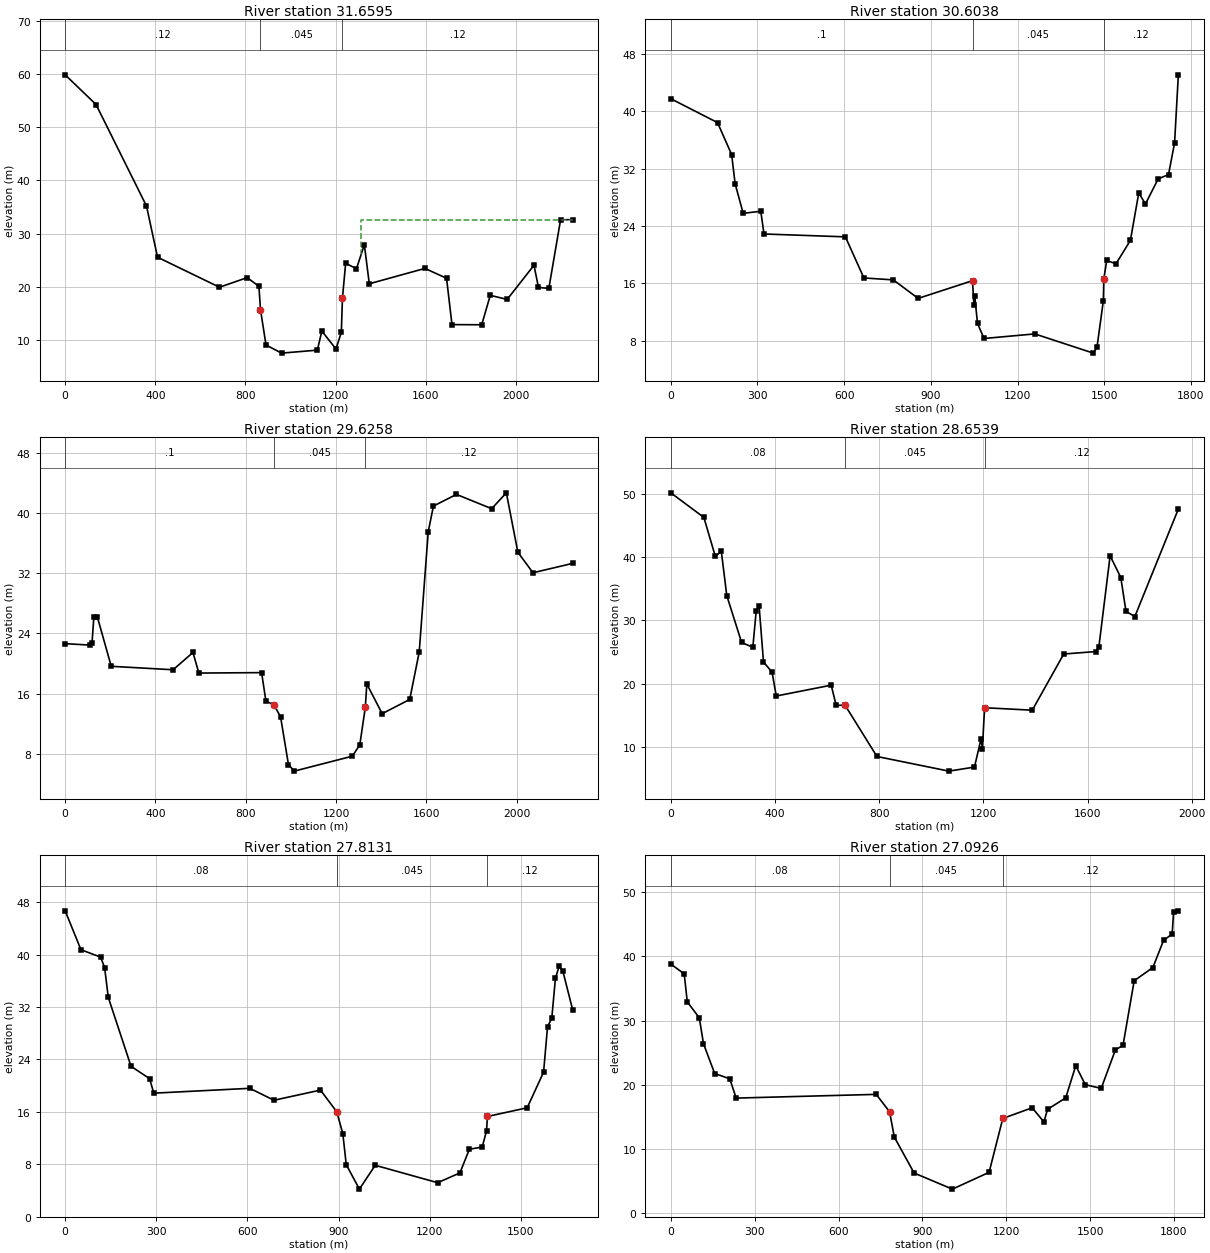
Type RM Length L Ch R = 1 ,31.6595 ,1164.99,1055.65,1002.89
BEGIN DESCRIPTION:
Great Rattling Brook - R21 (RIS 2013)
END DESCRIPTION:
XS GIS Cut Line= 2
604876.8866035985425792.79938309606859.2917035995424723.62268309
#Sta/Elev= 30
       0   59.85  136.96   54.27   360.9    35.2  409.88   25.58   684.8   19.94
  807.77   21.75  859.76   20.11   866.8   15.71  891.32   9.091  960.35   7.561
 1119.26   8.121 1138.94  11.711 1201.65   8.341 1225.53  11.461 1230.45   17.88
 1244.64   24.44 1292.63   23.42 1327.62   27.94 1349.61   20.59 1596.54   23.48
 1692.51   21.62  1716.5   12.92 1848.46   12.89 1886.45   18.42 1961.43   17.65
  2080.4   24.07 2100.39    19.9 2146.38   19.73 2198.37   32.59 2252.35   32.66
#Mann= 3 , 0 , 0
       0     .12       0   866.8    .045       0 1230.45     .12       0
#XS Ineff= 2 , 0
       0                    1312       0    32.5
Permanent Ineff=
       F       T
Bank Sta=866.8,1230.45
XS Rating Curve= 0 ,0
Exp/Cntr=0.3,0.1

Type RM Length L Ch R = 1 ,30.6038 ,995.75,978.05,1026.58
BEGIN DESCRIPTION:
R22 (RIS 2013)
END DESCRIPTION:
XS GIS Cut Line= 3
605516.7172035985426827.71408309605840.1641035985426776.41938309
606811.6739035985425728.32808309
#Sta/Elev= 30
       0   41.75  161.75   38.42  210.67   33.96  222.65   29.89  250.61   25.77
  311.51   26.06   322.5   22.89  604.32   22.49  668.28   16.76  770.21   16.49
  856.16   13.91 1044.21   16.38 1049.04   13.05 1051.88  14.199 1061.61  10.419
  1084.1   8.319 1259.67   8.959 1462.36   6.279 1474.97   7.079  1497.1  13.589
 1498.76   16.65 1508.75    19.2 1540.73   18.73  1590.7      22 1619.68   28.62
 1642.67   27.07 1686.64   30.56 1722.62   31.18  1743.6    35.6  1756.6   45.08
#Mann= 3 , 0 , 0
       0      .1       0 1044.21    .045       0 1498.76     .12       0
Bank Sta=1044.21,1498.76
XS Rating Curve= 0 ,0
Exp/Cntr=0.3,0.1

Type RM Length L Ch R = 1 ,29.6258 ,978.79,971.85,1004.28
BEGIN DESCRIPTION:
R23 (RIS 2013)
END DESCRIPTION:
XS GIS Cut Line= 3
606181.7716035985427331.43518309607036.3379035985426949.59128309
607814.8299035985425893.65648309
#Sta/Elev= 30
       0   22.64     110   22.45     119   22.75     127   26.19     142   26.25
     204   19.63     478   19.17     566   21.47     592   18.73     870   18.79
     889      15  924.81    14.5     954   12.91  988.89   6.559  1014.5   5.689
 1272.22   7.679 1304.99   9.209 1329.31   14.17 1335.96   17.28 1403.95   13.33
 1525.94   15.22 1567.94   21.51 1607.93   37.52 1630.93   40.94 1732.92   42.49
 1888.91   40.59  1953.9    42.7 2004.89    34.8 2071.89   32.07 2247.88   33.32
#Mann= 3 , 0 , 0
       0      .1       0  924.81    .045       0 1329.31     .12       0
Bank Sta=924.81,1329.31
XS Rating Curve= 0 ,0
Exp/Cntr=0.3,0.1

Type RM Length L Ch R = 1 ,28.6539 ,904.14,840.86,800.26
BEGIN DESCRIPTION:
Hobbs Park - R24 (RIS 2013)
END DESCRIPTION:
XS GIS Cut Line= 2
607336.8447035985428123.65878309608544.8664035985426594.53308309
#Sta/Elev= 30
       0   50.13  126.98   46.25  170.98   40.09  193.97   40.91  214.97    33.9
  271.96    26.5  314.96   25.74  327.95   31.45  338.95   32.32  355.95   23.43
  388.95    21.8  404.94   18.05  615.92   19.76  634.91   16.57     669    16.6
  791.59     8.5  1067.7    6.19 1165.96    6.83 1191.56   11.34 1196.35    9.71
 1204.83    16.2 1387.81   15.81 1508.79   24.68 1632.77   25.07 1643.77   25.86
 1686.76   40.19 1727.75   36.76 1747.75   31.41 1781.75    30.6 1948.72   47.57
#Mann= 3 , 0 , 0
       0     .08       0     669    .045       0 1204.83     .12       0
Bank Sta=669,1204.83
XS Rating Curve= 0 ,0
Exp/Cntr=0.3,0.1

Type RM Length L Ch R = 1 ,27.8131 ,616.01,720.41,859.47
BEGIN DESCRIPTION:
Greenridge Rd - R25 (RIS 2013)
END DESCRIPTION:
XS GIS Cut Line= 2
608158.5093035995428760.83048309608918.8907035985427272.76338309
#Sta/Elev= 30
       0   46.69   51.97   40.75  116.94   39.62  129.93      38  141.92   33.48
  216.88   22.95  277.85   21.07  291.84   18.85  607.67   19.59  687.62   17.77
  840.54   19.32  894.17   16.01  914.14  12.679  925.42   7.939   968.7   4.199
 1020.79   7.839 1226.45   5.179 1299.72   6.679 1330.83  10.289 1373.01  10.619
 1387.32  13.089 1390.24   15.29 1521.17   16.62 1575.15   22.06 1588.14      29
 1602.13   30.29 1614.12   36.38 1626.12    38.2 1638.11   37.57 1671.09   31.55
#Mann= 3 , 0 , 0
       0     .08       0  894.17    .045       0 1390.24     .12       0
Bank Sta=894.17,1390.24
XS Rating Curve= 0 ,0
Exp/Cntr=0.3,0.1

Type RM Length L Ch R = 1 ,27.0926 ,742.06,743.57,752.95
BEGIN DESCRIPTION:
Market Rd - R26 (RIS 2013)
END DESCRIPTION:
XS GIS Cut Line= 2
608355.4606035995428872.55618309609808.3645035985427783.83918309
#Sta/Elev= 30
       0   38.82   47.99   37.29   58.99   32.94  101.97   30.44  116.97   26.41
  156.96   21.77  210.95   20.95  233.94   17.94  734.82   18.52  782.67   15.81
  799.56  11.869  870.32   6.269 1007.23   3.759 1138.53   6.369 1187.63   14.77
 1292.68   16.43 1334.67   14.23 1347.66   16.19 1412.65   17.97 1448.64   22.99
 1482.63   20.03 1539.62   19.45 1590.61   25.47  1617.6   26.14 1657.59   36.22
 1724.58   38.28 1762.57    42.5 1793.56    43.5 1798.56   46.91 1815.56   47.11
#Mann= 3 , 0 , 0
       0     .08       0  782.67    .045       0 1187.63     .12       0
Bank Sta=782.67,1187.63
XS Rating Curve= 0 ,0
Exp/Cntr=0.3,0.1