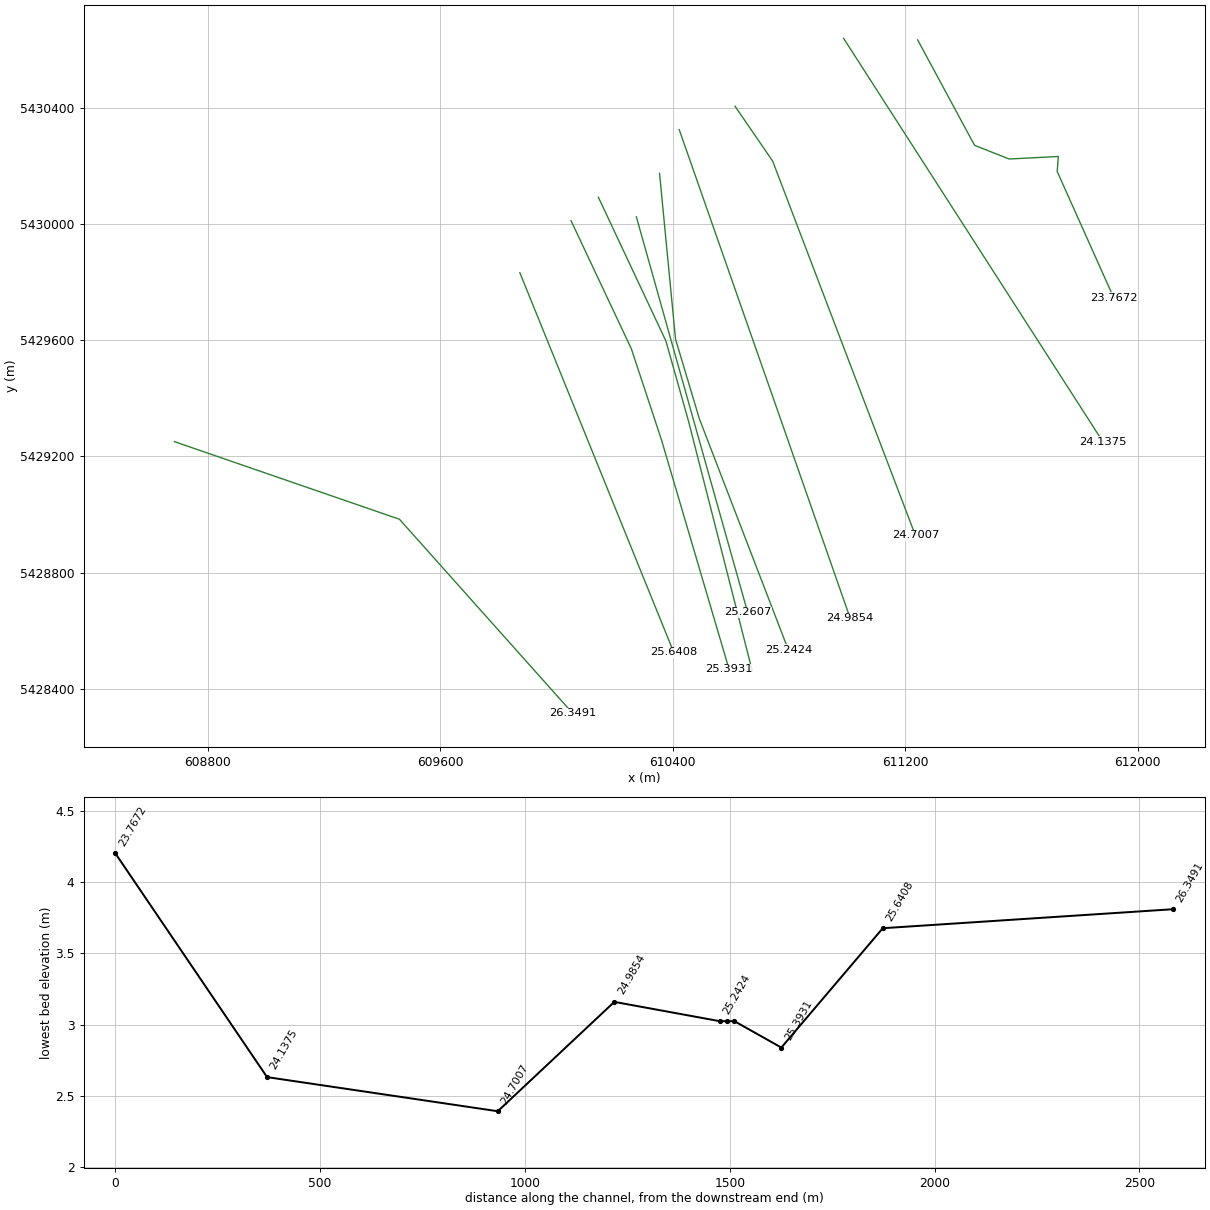
HEC-RAS study Unsteady_RAS.prj: Unsteady_RAS

--- Unsteady_RAS.g01 (geometry) --- (continued)

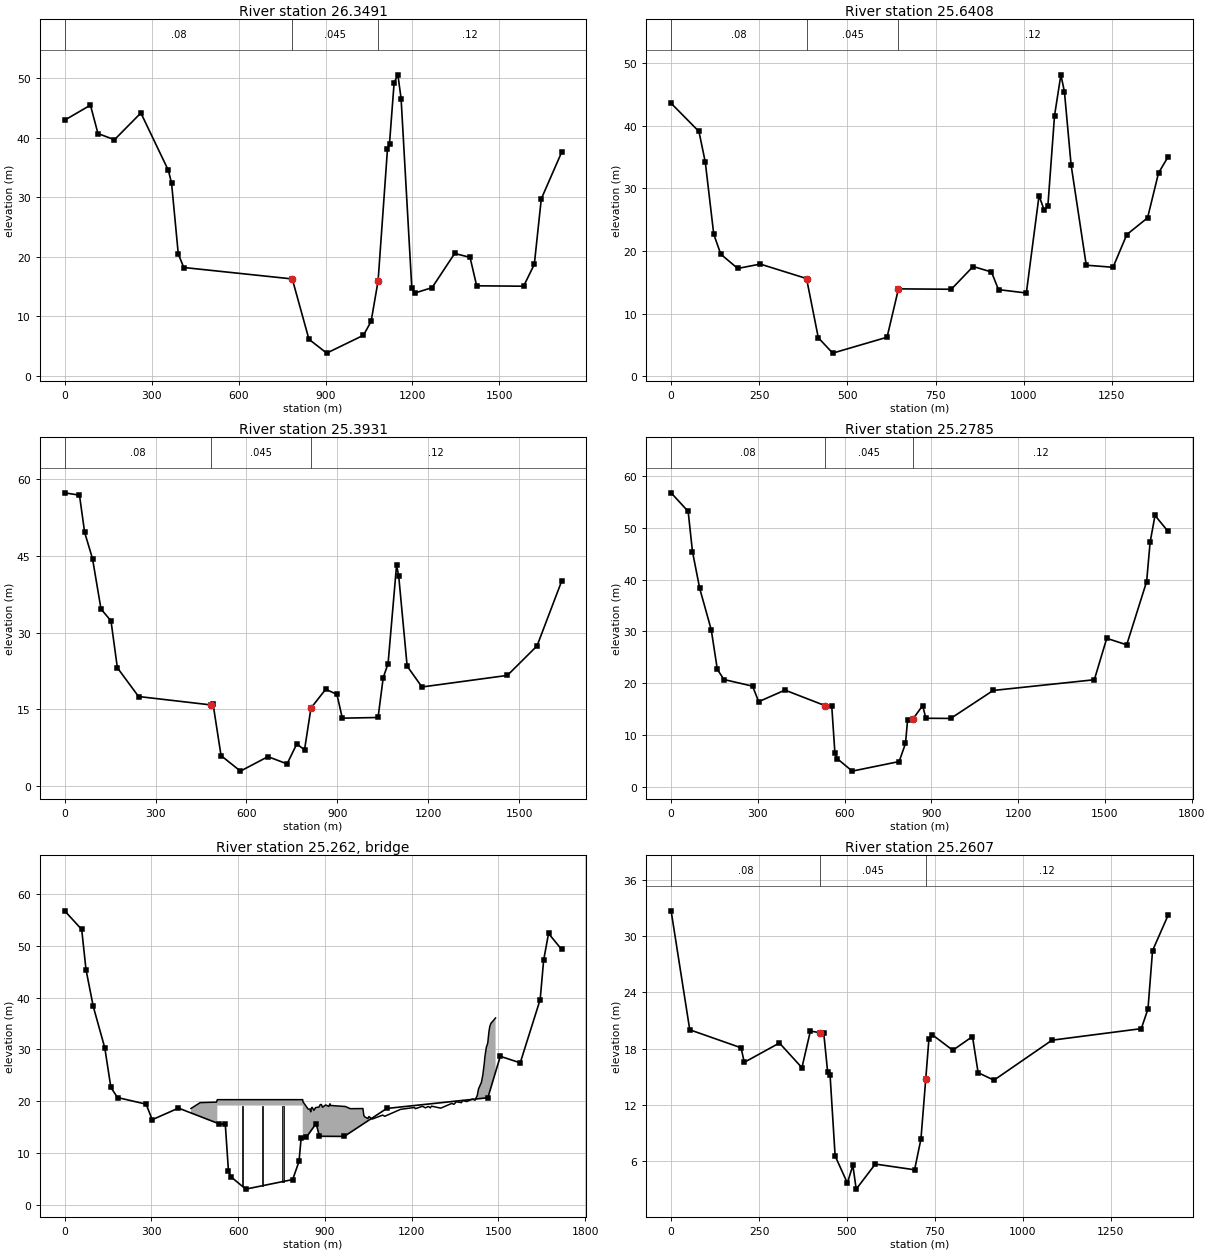
Type RM Length L Ch R = 1 ,26.3491 ,771.02,708.28,710.07
BEGIN DESCRIPTION:
Exploits Ln - R27 (RIS 2013)
END DESCRIPTION:
XS GIS Cut Line= 3
608685.2408035985429250.72878309609459.4595035995428983.85958309
610055.9901035995428316.22838309
#Sta/Elev= 30
       0   42.91   88.99   45.43  114.99   40.66  171.98   39.63  262.98   44.12
  357.97   34.47  368.97    32.3  391.96   20.48  410.96   18.18  785.28   16.26
  842.77   6.139  904.04   3.809  1030.9   6.809 1057.31   9.149 1081.32   15.93
 1113.69   38.03 1120.69   38.98 1136.68   49.22 1149.67   50.52 1160.66   46.54
 1197.63   14.74 1207.62   13.89 1267.58    14.8 1345.52   20.54 1398.48   19.88
 1421.46   15.11 1583.34   15.04 1620.31   18.72 1644.29    29.7 1714.24   37.49
#Mann= 3 , 0 , 0
       0     .08       0  785.28    .045       0 1081.32     .12       0
Bank Sta=785.28,1081.32
XS Rating Curve= 0 ,0
Exp/Cntr=0.3,0.1

Type RM Length L Ch R = 1 ,25.6408 ,257.43,247.69,261.1
BEGIN DESCRIPTION:
Doves Ln - R28 (RIS 2013)
END DESCRIPTION:
XS GIS Cut Line= 2
609873.9750035985429831.75668309610403.7701035985428525.84358309
#Sta/Elev= 30
       0   43.59   78.96   39.08   96.95   34.18  120.94   22.67  140.93   19.48
   188.9    17.2  252.87    17.9  384.16   15.59  417.51   6.126  458.32   3.676
  612.44   6.216   644.8   13.94   794.6   13.88  856.57   17.51  908.54   16.64
  928.53   13.82 1007.49   13.28 1043.47   28.82 1057.47   26.61 1068.46   27.12
 1087.45   41.62 1105.44   48.13 1115.44   45.45 1134.43   33.73  1177.4   17.72
 1253.37   17.39 1292.35   22.61 1351.32   25.29  1382.3   32.44 1409.29   35.02
#Mann= 3 , 0 , 0
       0     .08       0  384.16    .045       0   644.8     .12       0
Bank Sta=384.16,644.8
XS Rating Curve= 0 ,0
Exp/Cntr=0.3,0.1

Type RM Length L Ch R = 1 ,25.3931 ,120.13,114.65,111.21
BEGIN DESCRIPTION:
Cannings Ln - R28A (SEM 2019)
END DESCRIPTION:
XS GIS Cut Line= 4
610050.0674035995430010.72108309610257.7009035985429570.22728309
610361.8800035995429255.41998309610594.2340035985428467.55488309
#Sta/Elev= 30
       0   57.38      49   56.92      66   49.63      92   44.48  119.99   34.61
  152.99   32.28  173.99    23.1  243.99   17.46  483.55   15.81  489.97   15.95
  516.19    5.88  580.28    2.84  670.94    5.68  734.13    4.26  766.11    8.16
   791.7    7.02     813   15.21  861.55   18.88  898.52   17.88  916.51   13.22
 1034.42   13.35 1051.41   21.16  1067.4    23.9 1095.38   43.15 1102.37   41.17
 1130.35   23.42 1179.31   19.33 1461.11    21.6 1559.03   27.38 1639.97   40.02
#Mann= 3 , 0 , 0
       0     .08       0  483.55    .045       0     813     .12       0
Bank Sta=483.55,813
XS Rating Curve= 0 ,0
Exp/Cntr=0.3,0.1

Type RM Length L Ch R = 1 ,25.2785 ,20.11,17.77,18.26
BEGIN DESCRIPTION:
US of Bishop's Falls Trestle - R29-1 (RIS 2013)
END DESCRIPTION:
XS GIS Cut Line= 4
610144.2476035985430091.33098309610376.7635035985429596.68548309
610454.8157035985429320.19548309610673.6588035985428463.30998309
#Sta/Elev= 30
       0   56.76   58.95   53.17   73.94   45.39   98.92    38.3  138.89   30.29
  159.87   22.66  182.86   20.71  281.78   19.43  302.76   16.43  393.69   18.67
  532.79   15.66  555.55   15.52  566.38   6.565  573.94   5.455  626.34   3.025
   788.5   4.875  810.42   8.365  817.69  12.855  836.27   13.09  869.84   15.69
  880.83   13.23  966.77    13.2 1113.67    18.6 1463.43   20.67  1506.4   28.67
 1575.35   27.41  1644.3   39.63 1656.29   47.21 1673.28   52.39 1718.25   49.32
#Mann= 3 , 0 , 0
       0     .08       0  532.79    .045       0  836.27     .12       0
Bank Sta=532.79,836.27
XS Rating Curve= 0 ,0
Exp/Cntr=0.3,0.1

Type RM Length L Ch R = 3 ,25.262  ,,,
BEGIN DESCRIPTION:
Bishop's Falls Trestle
END DESCRIPTION:
Bridge Culvert--1,0,-1,-1, 0
Deck Dist Width WeirC Skew NumUp NumDn MinLoCord MaxHiCord MaxSubmerge Is_Ogee
0.1,5,1.4,0, 60, 60, , , 0.98, 0, 3,3,,
     437 468.696 525.112     528  823.22 824.219 842.089 847.988 850.937 852.903
 855.852 861.813 867.786 879.733 883.716 887.694 891.669 902.599 913.529 917.504
 919.491  970.94 987.7361031.3921034.3641037.3361048.2331052.1951063.0921099.745
1106.7291161.6671209.613 1212.611237.581 1247.561257.5341264.5161268.5061300.424
1338.3261346.3051354.2851372.2381376.2281390.192 1410.141419.1171427.1021431.097
1441.086 1446.081451.0741453.0711458.0651463.0591467.0551470.0511474.0461490.027
  18.604  19.726  19.821    20.3    20.3  19.871  18.481  18.467  17.952  18.627
  18.816  18.236  18.771  18.882   19.34  19.365  18.833   19.28  18.997  19.507
  19.179  18.977  18.562  18.583  17.287  16.991  16.666  17.037  16.544  17.316
  17.087  18.431  18.788  18.558  19.023  18.716  18.992  18.723  19.046  18.661
  19.565  19.407   19.89  19.724   20.14  19.931  20.422  20.191  21.172  22.374
  23.644  25.097  27.305  28.529  30.393  31.223  33.377  34.421  35.039  36.071
                           19.16   19.16
                                                                                
                                                                                
                                                                                
                                                                                
                                                                                
     350 381.696 438.112     441  736.22 737.219 755.089 760.988 763.937 765.903
 768.852 774.813 780.786 792.733 796.716 800.694 804.669 815.599 826.529 830.504
 832.491  883.94 900.736 944.392 947.364 950.336 961.233 965.195 976.0921012.745
1019.7291074.6671122.613 1125.611150.581 1160.561170.5341177.5161181.5061213.424
1251.3261259.3051267.2851285.2381289.2281303.192 1323.141332.1171340.1021344.097
1354.086 1359.081364.0741366.0711371.0651376.0591380.0551383.0511387.0461403.027
  18.604  19.726  19.821    20.3    20.3  19.871  18.481  18.467  17.952  18.627
  18.816  18.236  18.771  18.882   19.34  19.365  18.833   19.28  18.997  19.507
  19.179  18.977  18.562  18.583  17.287  16.991  16.666  17.037  16.544  17.316
  17.087  18.431  18.788  18.558  19.023  18.716  18.992  18.723  19.046  18.661
  19.565  19.407   19.89  19.724   20.14  19.931  20.422  20.191  21.172  22.374
  23.644  25.097  27.305  28.529  30.393  31.223  33.377  34.421  35.039  36.071
                           19.16   19.16
                                                                                
                                                                                
                                                                                
                                                                                
                                                                                
Pier Skew, UpSta & Num, DnSta & Num=  ,615, 2 ,506.25, 2 , 0 , 0 , 0 ,,
       4       4
       0    19.7
       4       4
       0    19.7
Pier Skew, UpSta & Num, DnSta & Num=  ,685, 2 ,587.5, 2 , 0 , 0 , 0 ,,
       4       4
       0    19.7
       4       4
       0    19.7
Pier Skew, UpSta & Num, DnSta & Num=  ,755, 2 ,668.75, 2 , 0 , 0 , 0 ,,
       4       4
       0    19.7
       4       4
       0    19.7
BR Coef=-1 , 0 , 0 ,, 0 ,,,0.8,-1,,0,
WSPro=,,,, 1 ,,,, 0 ,,,, 0 ,,,,-1 ,-1 ,-1 , 0 , 0 , 0 , 0 , 0
BC Design=,, 0 ,, 0 ,,,,,,
BC HTab HWMax=30
BC Use User HTab Curves=0
BC User HTab FreeFlow(D)= 0

Type RM Length L Ch R = 1 ,25.2607 ,18.92,18.24,21.96
BEGIN DESCRIPTION:
DS of Bishop's Falls Trestle - R29-2 (RIS 2013)
END DESCRIPTION:
XS GIS Cut Line= 2
610274.9696035985430023.95548309610657.9911035985428663.86218309
#Sta/Elev= 30
       0   32.67      53      20     199   18.08     208   16.53     308   18.59
     372   15.96     396   19.86   424.7   19.68     434   19.66     445   15.55
     452   15.19  466.38   6.565   501.2   3.675  516.82   5.555  526.34   3.025
  580.65   5.695  692.35   5.085  710.42   8.365  724.14   14.78     733   18.97
     742   19.49     801   17.82     857   19.28     873   15.43     918   14.63
    1083   18.89 1336.99   20.12 1355.99   22.22 1368.99   28.43 1412.99   32.18
#Mann= 3 , 0 , 0
       0     .08       0   424.7    .045       0  724.14     .12       0
Bank Sta=424.7,724.14
XS Rating Curve= 0 ,0
Exp/Cntr=0.3,0.1

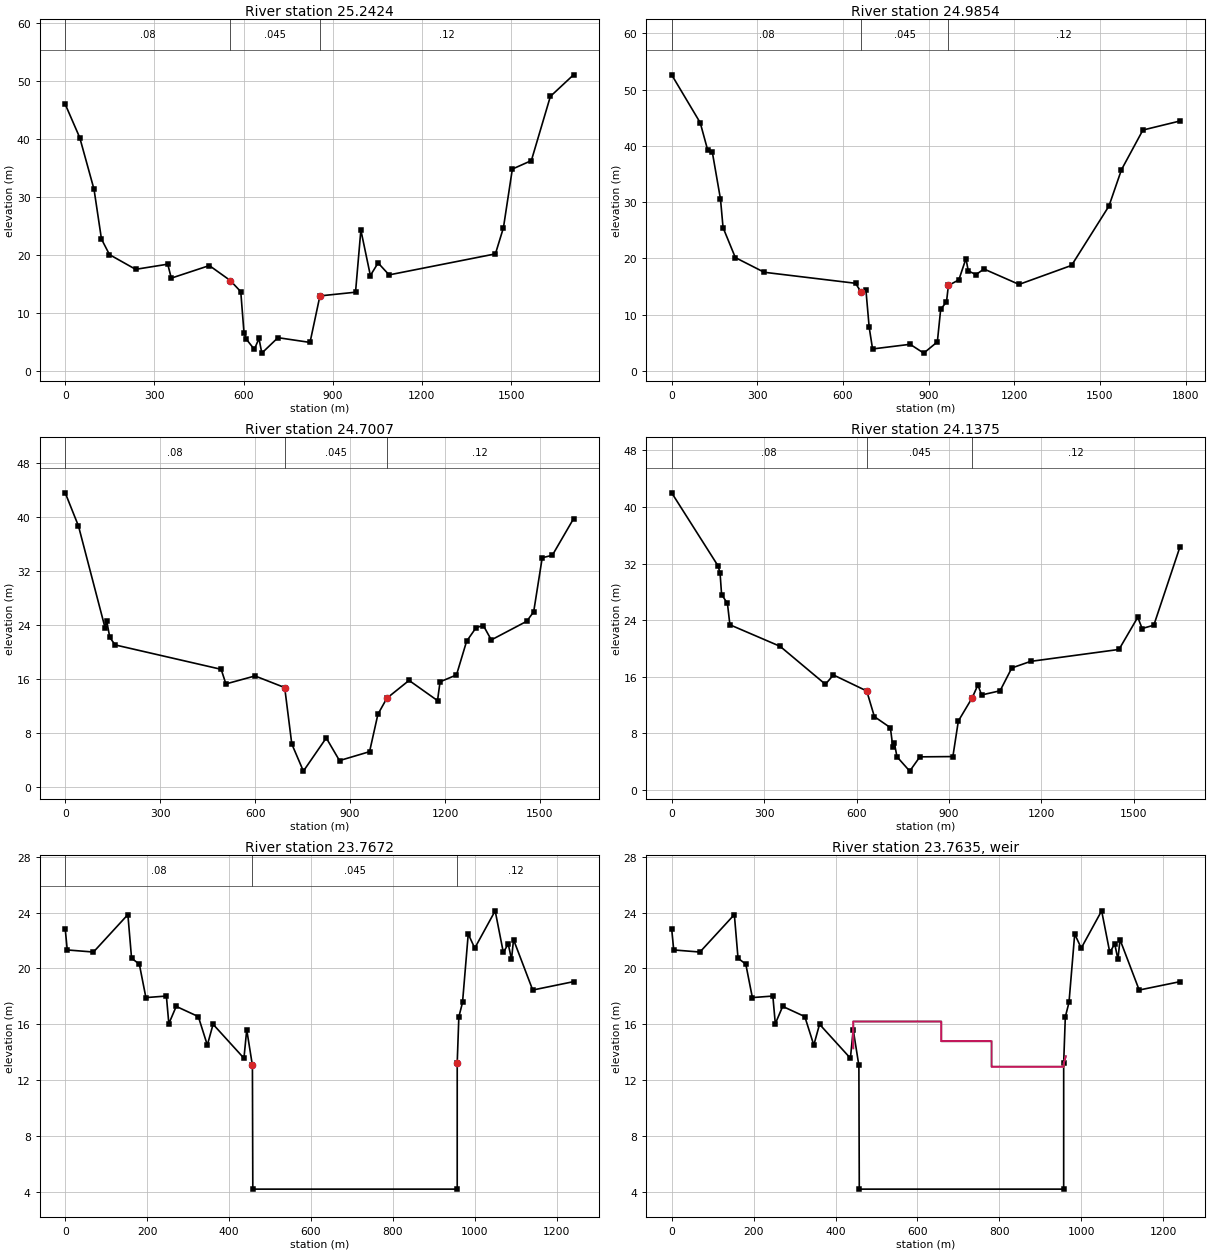
Type RM Length L Ch R = 1 ,25.2424 ,246.1,257.07,267.74
BEGIN DESCRIPTION:
NLENHM0003 ER at Bishop's Falls Trestle
END DESCRIPTION:
XS GIS Cut Line= 4
610354.8152035985430173.47438309610409.8365035985429603.30008309
610491.8574035985429329.45598309610797.9386035995428535.14458309
#Sta/Elev= 30
       0   46.03   48.98   40.24   96.97   31.31  121.96   22.73  148.95   20.04
  236.93    17.5  344.89   18.39  356.89   15.98  484.85   18.15  555.25   15.57
  590.54  13.645  601.38   6.565  608.94   5.455   636.2   3.675  651.82   5.555
  661.34   3.025  715.65   5.695   823.5   4.875  856.84   12.91  976.58   13.55
  994.56   24.28 1026.53   16.43 1052.51   18.61 1089.48   16.54 1447.17   20.17
 1474.15   24.69 1504.12   34.82 1568.06   36.28 1632.01   47.37 1709.94    51.1
#Mann= 3 , 0 , 0
       0     .08       0  555.25    .045       0  856.84     .12       0
Bank Sta=555.25,856.84
XS Rating Curve= 0 ,0
Exp/Cntr=0.3,0.1

Type RM Length L Ch R = 1 ,24.9854 ,281.37,284.66,290.76
BEGIN DESCRIPTION:
Kinsmen Dr - R29-2A (SEM 2019)
END DESCRIPTION:
XS GIS Cut Line= 4
610422.5005035985430323.93238309610645.3163035985429687.96708309
610741.2790035985429414.51798309611010.8034035985428643.77428309
#Sta/Elev= 30
       0   52.65   99.98   44.13  125.98   39.29  141.97   39.01  170.97   30.54
  179.96   25.48  222.96   20.15  323.94   17.54  643.88   15.58  663.45      14
  680.29   14.38  691.65    7.75  703.53     3.9  835.07    4.73  882.72    3.16
   930.4    5.16  942.07   10.96  962.42   12.26  969.07   15.19 1005.64   16.19
 1030.62   19.97 1038.62   17.79  1065.6   17.12 1093.59   18.12 1216.51   15.38
 1400.39   18.76 1531.31   29.31 1575.28   35.79 1650.23   42.83 1780.15   44.44
#Mann= 3 , 0 , 0
       0     .08       0  663.45    .045       0  969.07     .12       0
Bank Sta=663.45,969.07
XS Rating Curve= 0 ,0
Exp/Cntr=0.3,0.1

Type RM Length L Ch R = 1 ,24.7007 ,537.64,563.23,612.52
BEGIN DESCRIPTION:
Riverside Dr - R30 (RIS 2013)
END DESCRIPTION:
XS GIS Cut Line= 3
610614.6886035995430404.38208309610744.1562035985430215.60338309
611235.2131035985428928.88678309
#Sta/Elev= 30
       0   43.58   41.98   38.66  125.95    23.6  130.95   24.65  140.94   22.17
  157.94   21.07  492.76   17.46  507.75    15.3   599.7   16.48   693.5   14.76
  715.93   6.414  752.57   2.394   824.8   7.304  866.69   3.954  961.67   5.274
  988.07  10.814 1016.27   13.18 1086.43   15.82 1176.38   12.83 1184.38   15.61
 1236.35   16.63 1268.33   21.62 1298.32   23.63  1321.3   23.93 1346.29   21.81
 1458.23   24.57 1480.22   25.97  1507.2   33.97 1539.19   34.34 1606.15   39.74
#Mann= 3 , 0 , 0
       0     .08       0   693.5    .045       0 1016.27     .12       0
Bank Sta=693.5,1016.27
XS Rating Curve= 0 ,0
Exp/Cntr=0.3,0.1

Type RM Length L Ch R = 1 ,24.1375 ,197.35,370.28,378.31
BEGIN DESCRIPTION:
Sydney St - R31 (RIS 2013)
END DESCRIPTION:
XS GIS Cut Line= 2
610988.3413035985430637.88788309611880.7428035985429250.63758309
#Sta/Elev= 30
       0   42.01  149.95   31.71  156.95   30.71  161.95   27.62  180.94   26.37
  188.94   23.34  351.89   20.29  498.85   14.92  524.84   16.24  632.99  13.973
  657.79  10.343  709.65   8.783  717.56   6.103  722.78   6.583  731.11   4.663
  772.46   2.633  805.33   4.653  912.48   4.693  930.23   9.723   975.2  13.013
   993.7   14.82  1005.7   13.41 1065.68      14 1103.67   17.23 1164.65   18.16
 1451.56   19.85 1512.55   24.41 1526.54   22.81 1564.53   23.28  1649.5   34.38
#Mann= 3 , 0 , 0
       0     .08       0  632.99    .045       0   975.2     .12       0
Bank Sta=632.99,975.2
XS Rating Curve= 0 ,0
Exp/Cntr=0.3,0.1

Type RM Length L Ch R = 1 ,23.7672 ,284.19,49.69,32.96
BEGIN DESCRIPTION:
US of Bishop's Falls Dam
END DESCRIPTION:
XS GIS Cut Line= 6
  611243.3111036 5430632.4161831  611439.1032036 5430269.9362831
  611558.4305036 5430222.8402831  611727.4996036 5430231.5715831
  611723.5308036 5430179.9777831  611918.3175036 5429745.2664831
#Sta/Elev= 30
       0   22.83       5   21.32      69   21.17  152.99   23.85  161.99   20.73
  180.99    20.3  196.99   17.91  246.99   18.02  252.99   16.04  270.99   17.28
  324.98   16.55  346.98   14.51  360.98      16  436.34   13.57  443.16   15.61
  457.03   13.05     458     4.2     957     4.2  957.02   13.26     961   16.53
  969.96   17.56  983.91   22.46  999.85   21.45 1049.67   24.12 1069.59   21.14
 1081.55   21.75 1089.52   20.65  1094.5   22.06 1141.33   18.45 1240.97   19.05
#Mann= 3 , 0 , 0
       0     .08       0  457.03    .045       0  957.02     .12       0
Bank Sta=457.03,957.02
XS Rating Curve= 0 ,0
Exp/Cntr=0.3,0.1

Type RM Length L Ch R = 5 ,23.7635 ,,,
BEGIN DESCRIPTION:
Bishop's Falls Dam
END DESCRIPTION:
IW Pilot Flow=0
#Inline Weir SE= 11
  443.16  14.282  443.16  16.202     658  16.202     658  14.792     706  14.792
     706  14.792     781  14.792     781  12.962   956.9  12.962   957.3  13.229
   962.1  13.702
IW Dist,WD,Coef,Skew,MaxSub,Min_El,Is_Ogee,SpillHt,DesHd
10,10,1.8,0,0.98,, 0 ,,,3,3,
IW Gate Name Wd,H,Inv,GCoef,Exp_T,Exp_O,Exp_H,Type,WCoef,Is_Ogee,SpillHt,DesHd,#Openings
BF Gates    ,5.5,4.328,4.577,0.555,0,1,0.5, 0 ,1.45, 0 ,,, 9 ,0,0.8, 0 ,0.555,,0,0,0, 0
     720     727     734     741     748     755     762     769     776
IW Gate Name Wd,H,Inv,GCoef,Exp_T,Exp_O,Exp_H,Type,WCoef,Is_Ogee,SpillHt,DesHd,#Openings
BF Fboards  ,175.9,1.22,11.742,,0,1,0.5, 3 ,1.8, 0 ,,, 1 ,0,0.8, 0 ,,,0,0,0, 0
  868.95
Inline Weir Flap Gates= 0