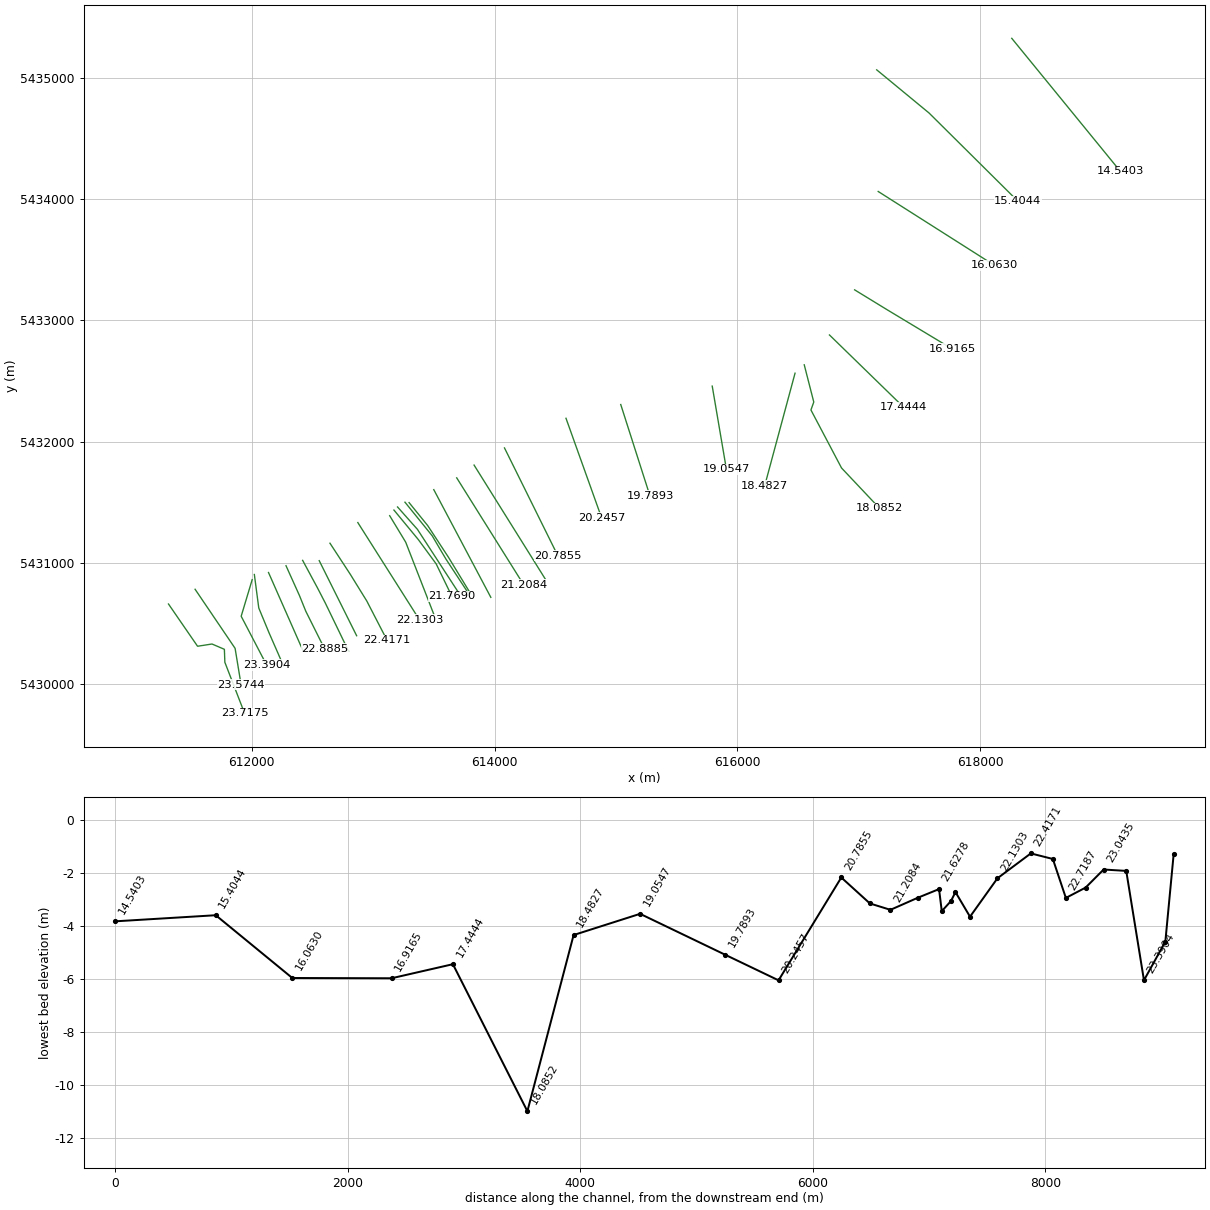
HEC-RAS study Unsteady_RAS.prj: Unsteady_RAS

--- Unsteady_RAS.g01 (geometry) --- (continued)

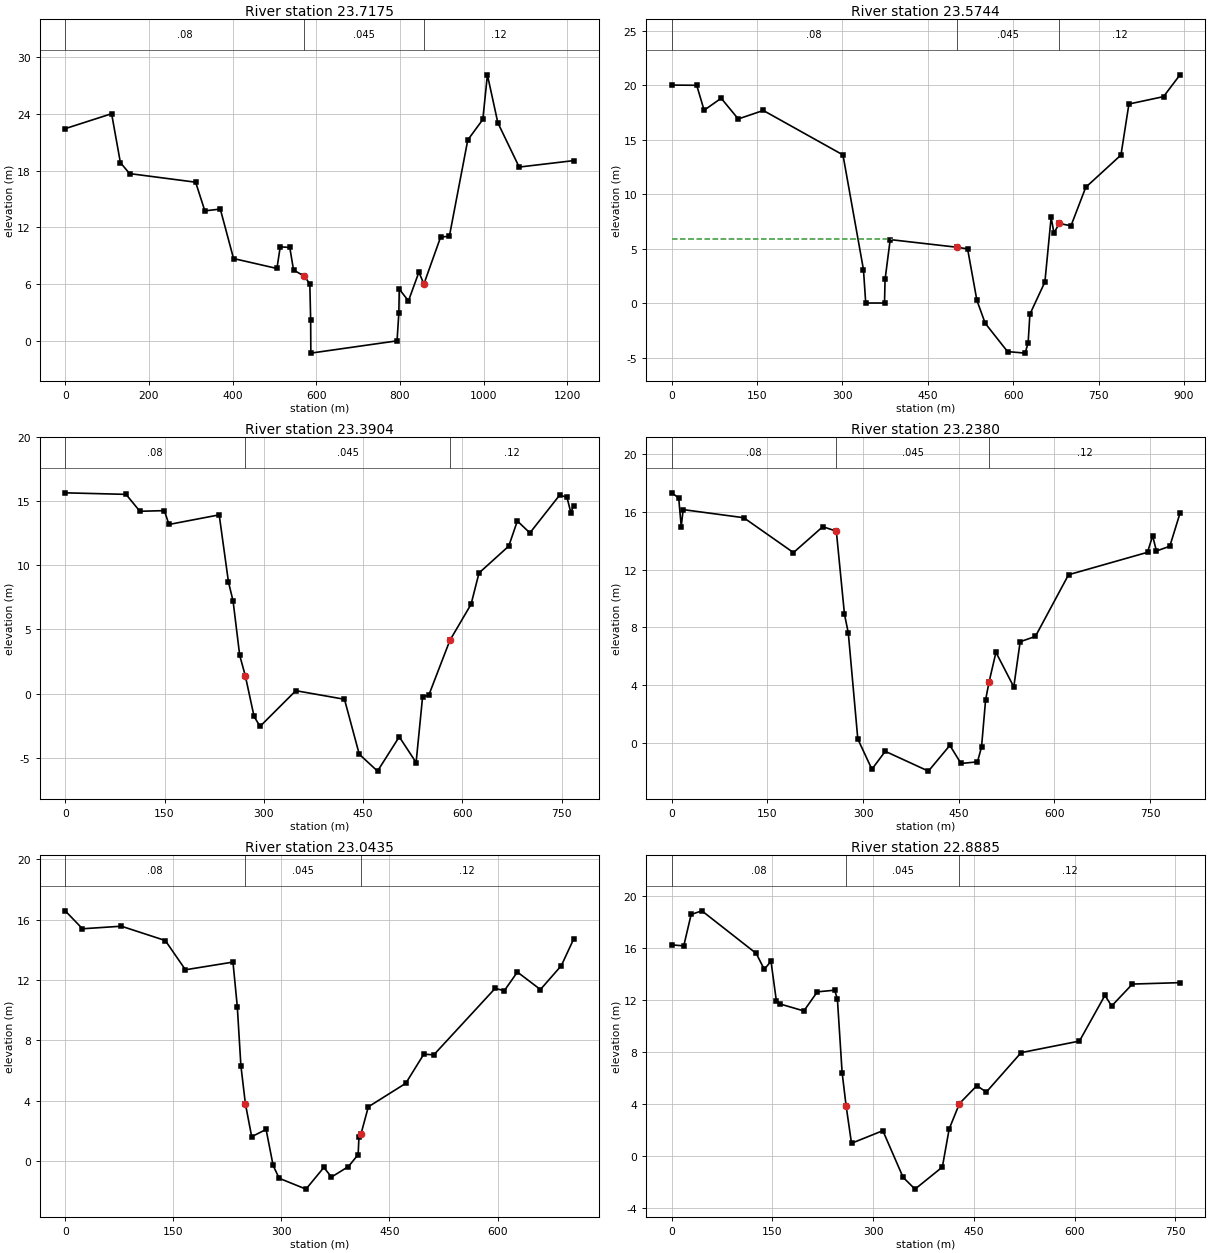
Type RM Length L Ch R = 1 ,23.7175 ,53.31,71.56,87.51
BEGIN DESCRIPTION:
DS of Bishop's Falls Dam
END DESCRIPTION:
XS GIS Cut Line= 6
  611313.4258036 5430662.8432831  611552.8742036 5430314.9154831
  611671.9370036 5430333.4363831  611773.8017036 5430289.7800831
  611777.7549036 5430182.9476831  611940.4896036 5429761.9352831
#Sta/Elev= 30
       0   22.43  110.89   24.01  131.87   18.84  153.85   17.68   311.7   16.77
  333.68   13.74  370.65   13.93  402.27     8.7  505.94    7.65  513.88    9.94
   536.7    9.87  545.63    7.49  571.59    6.83  584.57    6.02  586.57    2.17
     587  -1.298     793       0  797.31    2.93   798.3    5.47  820.27    4.22
  845.22    7.26   857.2    6.01  897.13   10.97  918.09   11.06  962.02   21.23
  997.96    23.4 1008.94   28.12 1033.89   23.05 1084.84   18.37 1214.77   19.05
#Mann= 3 , 0 , 0
       0     .08       0  571.59    .045       0   857.2     .12       0
Bank Sta=571.59,857.2
XS Rating Curve= 0 ,0
Exp/Cntr=0.3,0.1

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
Type RM Length L Ch R = 1 ,23.5744 ,273.17,183.95,201.98
BEGIN DESCRIPTION:
Fallsview Park - RB01 (RIS 2012)
END DESCRIPTION:
XS GIS Cut Line= 3
611532.4663035985430784.47778309611862.0448035985430297.78958309
611911.6487035985429996.71668309
#Sta/Elev= 30
       0      20   43.98   19.98   56.98   17.69   86.97   18.79  116.96   16.89
  160.94   17.67  300.89   13.59  336.88    3.07  340.87       0  373.86       0
  374.86    2.17  383.86    5.82  500.76    5.12  519.81    4.97  536.13    .252
  550.71  -1.858     590  -4.458  620.86  -4.598  626.14  -3.658  629.24  -1.028
  655.59    1.93  666.56    7.86  671.55    6.41  680.56     7.3  701.46    7.09
  727.39   10.62  789.22   13.58  803.18   18.26  864.01   18.94  892.92   20.94
#Mann= 3 , 0 , 0
       0     .08       0  500.76    .045       0  680.56     .12       0
#XS Ineff= 2 , 0
       0     387    5.84               0
Permanent Ineff=
       T       F
Bank Sta=500.76,680.56
XS Rating Curve= 0 ,0
Exp/Cntr=0.3,0.1

Type RM Length L Ch R = 1 ,23.3904 ,138.39,152.45,147.72
BEGIN DESCRIPTION:
RB02 (RIS 2012)
END DESCRIPTION:
XS GIS Cut Line= 3
612002.7701035985430863.30138309611912.2141035985430562.14938309
612121.9974035985430160.23608309
#Sta/Elev= 30
       0   15.67   91.85   15.55  112.81   14.23  149.75   14.28  156.74    13.2
  232.61   13.95  246.59    8.71  253.57    7.22  263.56    2.99  271.97     1.4
  285.29  -1.788   294.3  -2.568  348.34    .222  421.84   -.448  444.15  -4.738
  471.75  -6.058   504.6  -3.378  530.04  -5.388  539.85   -.248  549.06   -.148
  581.06    4.15  613.06    6.97  625.04    9.41  669.98   11.51  682.96   13.47
  701.93   12.54  746.87   15.49  757.86   15.33  763.85   14.11  767.84   14.68
#Mann= 3 , 0 , 0
       0     .08       0  271.97    .045       0  581.06     .12       0
Bank Sta=271.97,581.06
XS Rating Curve= 0 ,0
Exp/Cntr=0.3,0.1

Type RM Length L Ch R = 1 ,23.2380 ,188.98,194.52,204.76
BEGIN DESCRIPTION:
RB02A (SEM 2019)
END DESCRIPTION:
XS GIS Cut Line= 4
612020.7285035985430905.86818309612057.1210035985430630.34298309
612141.3590035985430426.56098309612261.0617035985430153.06188309
#Sta/Elev= 30
       0    17.3      11   16.95      15   14.97   17.99   16.14  112.97   15.58
  190.94   13.17  236.93   14.96  258.16   14.65  270.92    8.91  276.92    7.62
  291.82     .29  313.92    -1.8  334.86    -.56   402.5   -1.93  436.18    -.15
  453.59    -1.4  479.47   -1.29  485.81    -.26   492.2       3  497.72    4.25
  508.41    6.28  536.37    3.89  546.35    7.01  570.32    7.38  622.24   11.64
  746.05   13.19  754.04   14.33  760.03   13.28     781   13.61  796.97   15.89
#Mann= 3 , 0 , 0
       0     .08       0  258.16    .045       0  497.72     .12       0
Bank Sta=258.16,497.72
XS Rating Curve= 0 ,0
Exp/Cntr=0.3,0.1

Type RM Length L Ch R = 1 ,23.0435 ,158.58,154.99,157.25
BEGIN DESCRIPTION:
RB03 (RIS 2012)
END DESCRIPTION:
XS GIS Cut Line= 2
612137.3516035985430922.37948309612422.0569035985430276.89158309
#Sta/Elev= 30
       0   16.58   23.98   15.39   77.94   15.56   138.9   14.61  166.88   12.67
  232.83   13.18  238.83   10.23  243.82    6.31  250.08    3.78  258.81     1.6
   278.8    2.08  288.56   -.308  296.93  -1.158  334.17  -1.878  358.99   -.438
  369.53  -1.078  393.13   -.378  406.55    .412   407.7    1.58   410.4    1.76
  420.69    3.58  472.66    5.14  497.64    7.07  511.63    7.03  596.57   11.43
  609.56   11.29  627.54   12.52  659.52   11.36   688.5   12.94  705.49   14.69
#Mann= 3 , 0 , 0
       0     .08       0  250.08    .045       0   410.4     .12       0
Bank Sta=250.08,410.4
XS Rating Curve= 0 ,0
Exp/Cntr=0.3,0.1

Type RM Length L Ch R = 1 ,22.8885 ,160.64,169.83,174.21
BEGIN DESCRIPTION:
RB03A (SEM 2019)
END DESCRIPTION:
XS GIS Cut Line= 4
612281.6944035985430978.09398309612392.5191035985430732.10658309
612444.5200035985430603.41298309612600.2783035985430291.78168309
#Sta/Elev= 30
       0   16.25   17.99   16.17   28.98   18.59   44.97   18.87  125.91   15.59
   137.9   14.36  147.89   14.99  155.88   11.94  161.88   11.69  196.85   11.16
  216.84   12.63  242.82   12.76  246.82   12.06  253.81    6.42  259.82    3.83
   267.8     .97  314.47    1.94  344.61   -1.65  362.37   -2.56  403.09    -.86
  413.24    2.07  428.57    4.03  454.52    5.41   468.5    4.91  520.41    7.95
  607.26    8.84  645.19   12.36  655.17   11.54  686.12   13.23  756.99   13.34
#Mann= 3 , 0 , 0
       0     .08       0  259.82    .045       0  428.57     .12       0
Bank Sta=259.82,428.57
XS Rating Curve= 0 ,0
Exp/Cntr=0.3,0.1

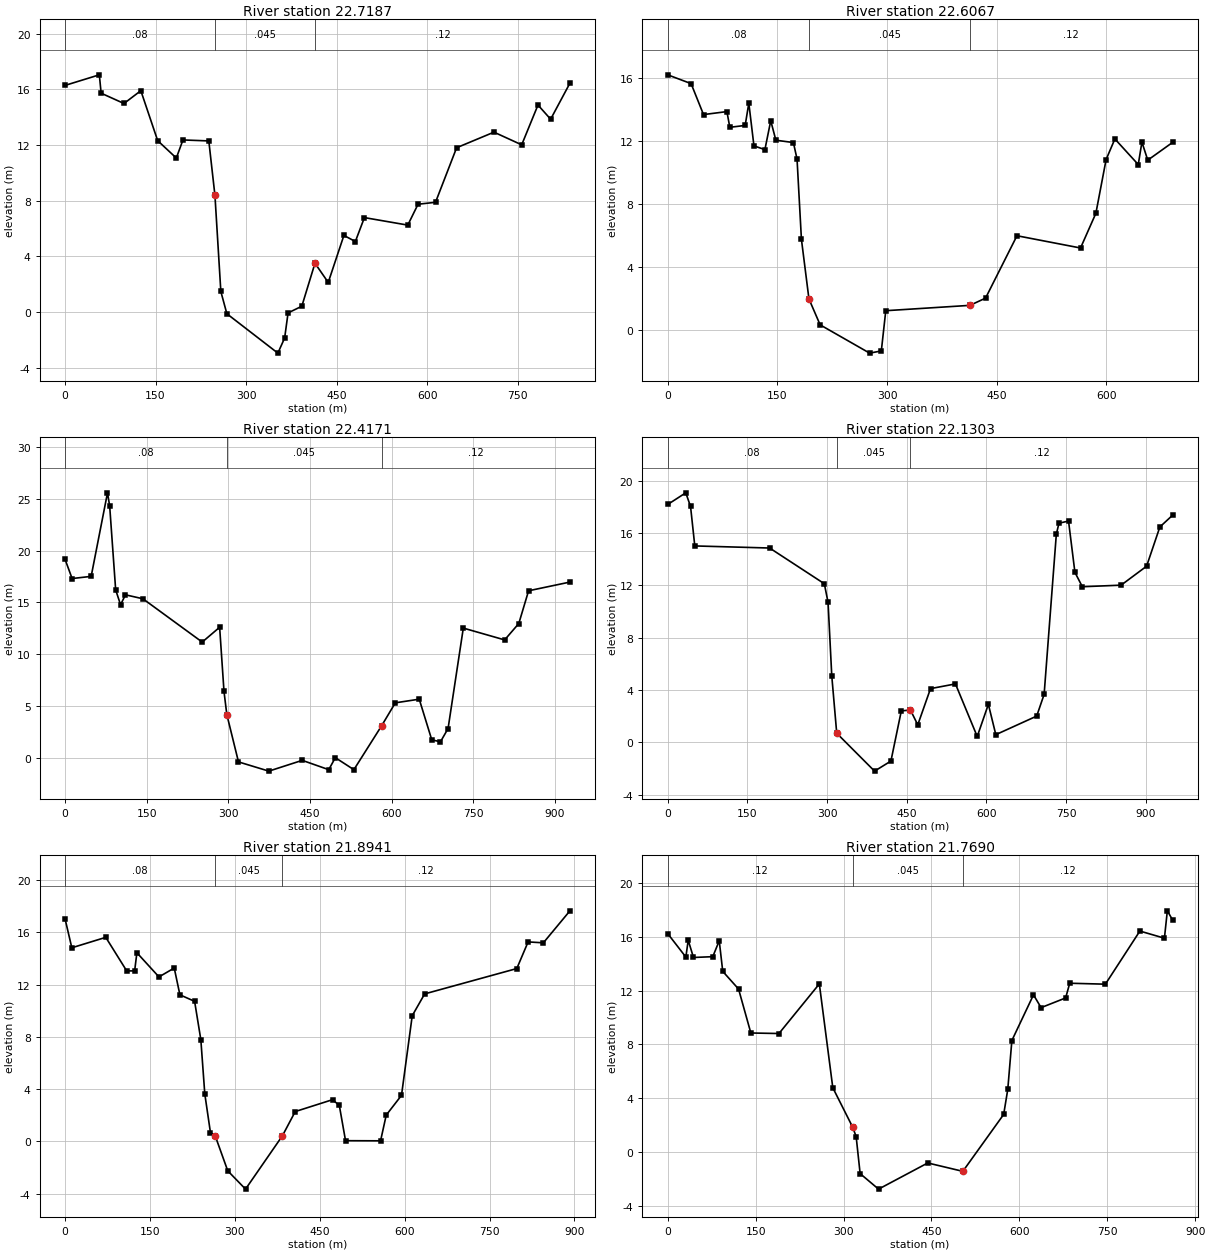
Type RM Length L Ch R = 1 ,22.7187 ,113.52,111.97,142.35
BEGIN DESCRIPTION:
RB03B (SEM 2019)
END DESCRIPTION:
XS GIS Cut Line= 4
612418.6857035985431022.22958309612542.5272035985430792.28738309
612606.3272035985430668.78338309612796.2655035985430275.84498309
#Sta/Elev= 30
       0   16.29   56.82   17.05   59.81   15.73   97.69   14.99   125.6   15.91
  153.51   12.32  184.41   11.07  195.38   12.37  238.24    12.3  248.41    8.38
  258.17    1.48  268.16    -.12  352.67   -2.95  363.91   -1.86  369.56    -.06
  392.35     .42  414.16    3.51  436.13    2.13   462.1    5.51  481.08    5.07
  496.06    6.79  567.96    6.25  584.94    7.75  613.91    7.89  648.86   11.81
  710.78   12.93  756.72   12.02  783.69   14.88  804.66   13.86  836.62   16.45
#Mann= 3 , 0 , 0
       0     .08       0  248.41    .045       0  414.16     .12       0
Bank Sta=248.41,414.16
XS Rating Curve= 0 ,0
Exp/Cntr=0.3,0.1

Type RM Length L Ch R = 1 ,22.6067 ,178.5,189.54,215.43
BEGIN DESCRIPTION:
RB04 (RIS 2012)
END DESCRIPTION:
XS GIS Cut Line= 2
612555.1334035985431019.94838309612863.2975035985430401.75718309
#Sta/Elev= 30
       0   16.23   31.99   15.67   48.98    13.7   80.97   13.89   84.97   12.89
  105.96   13.01  110.96   14.43  117.96   11.71  132.95   11.47  140.95   13.31
  147.94   12.07  171.94   11.92  176.93   10.87  182.93    5.76  193.21    1.97
  208.52     .32  276.26   -1.48  292.24   -1.34  298.33    1.22  413.47    1.56
  434.84    2.02  477.82    5.99  564.79    5.21  585.78    7.42  599.78   10.84
  611.77   12.15  643.76   10.52  648.76   11.95  656.76    10.8  690.74   11.93
#Mann= 3 , 0 , 0
       0     .08       0  193.21    .045       0  413.47     .12       0
Bank Sta=193.21,413.47
XS Rating Curve= 0 ,0
Exp/Cntr=0.3,0.1

Type RM Length L Ch R = 1 ,22.4171 ,289.91,286.85,309.42
BEGIN DESCRIPTION:
RB04A (SEM 2019)
END DESCRIPTION:
XS GIS Cut Line= 4
612643.6500035985431163.77218309612811.0750035985430907.63798309
612947.0970035985430687.52098309613113.5509035985430365.25808309
#Sta/Elev= 30
       0   19.17      13   17.31      48   17.52      78   25.58      82   24.31
      93   16.22     102   14.78     111   15.74     143   15.36     252   11.18
     284   12.61     292    6.42  297.19    4.19  318.61    -.38  374.38   -1.27
  435.76    -.23  484.46   -1.13  496.51     .03  530.61   -1.13  581.74    3.12
  606.72    5.32  650.69    5.67  673.67    1.75  689.66    1.56  703.64    2.84
  731.62   12.53  807.56   11.39  833.54   12.97  851.53   16.13  927.47   16.97
#Mann= 3 , 0 , 0
       0     .08       0  297.19    .045       0  581.74     .12       0
Bank Sta=297.19,581.74
XS Rating Curve= 0 ,0
Exp/Cntr=0.3,0.1

Type RM Length L Ch R = 1 ,22.1303 ,249.37,236.19,233.26
BEGIN DESCRIPTION:
RB05 (RIS 2012)
END DESCRIPTION:
XS GIS Cut Line= 2
612873.2338035985431333.68718309613382.2572035995430530.82688309
#Sta/Elev= 30
       0   18.18   33.99   19.07   42.98   18.03   50.98   15.01  191.92   14.85
  294.88   12.12  301.88    10.7  308.88    5.08  318.22     .69  389.45  -2.208
  420.27  -1.438  439.83     2.4  457.07    2.46  470.81    1.33   494.8     4.1
  541.78    4.46  582.77     .44  603.76     2.9  617.76     .58  694.73       2
  708.72    3.66  731.71   15.91  736.71   16.75   754.7   16.91   766.7   12.99
  780.69   11.89  853.67   12.01  901.65   13.46  926.64   16.46  950.63   17.36
#Mann= 3 , 0 , 0
       0     .08       0  318.22    .045       0  457.07     .12       0
Bank Sta=318.22,457.07
XS Rating Curve= 0 ,0
Exp/Cntr=0.3,0.1

Type RM Length L Ch R = 1 ,21.8941 ,105.81,125.11,172.27
BEGIN DESCRIPTION:
RB06 (RIS 2012)
END DESCRIPTION:
XS GIS Cut Line= 3
613135.5643035985431390.40198309613267.5307035995431172.33648309
613498.9161035995430578.80078309
#Sta/Elev= 30
       0   17.04   11.99   14.82   71.97   15.62  108.95   13.05  122.95   13.05
  126.94   14.44  165.93   12.59  192.92   13.27  202.91   11.22   228.9   10.72
  239.89    7.79  246.89    3.63  256.88     .67  265.21     .43  287.46  -2.259
  318.87  -3.659  383.95     .42  406.66    2.28  472.56    3.19  484.54    2.75
  495.53     .05  557.43     .04  567.42    2.01  594.38    3.52  613.35    9.62
  635.31   11.29  798.07   13.23  818.04   15.27     845    15.2  891.92   17.65
#Mann= 3 , 0 , 0
       0     .08       0  265.21    .045       0  383.95     .12       0
Bank Sta=265.21,383.95
XS Rating Curve= 0 ,0
Exp/Cntr=0.3,0.1

Type RM Length L Ch R = 1 ,21.7690 ,43,38.95,32.98
BEGIN DESCRIPTION:
US of Sir Robert Bond Bridge - RB07A (SEM 2019)
END DESCRIPTION:
XS GIS Cut Line= 4
613170.7010035985431436.82278309613371.7450035985431193.47598309
613518.3642035985430993.90938309613648.5395035995430725.62128309
#Sta/Elev= 30
       0   16.22   30.97   14.48   34.96   15.73   43.95   14.45   76.92   14.51
    87.9   15.69    93.9   13.42  120.87   12.11  141.84    8.85  189.79    8.81
  258.71   12.49  281.69    4.79  315.31    1.89  321.52    1.17  328.33   -1.58
  359.76   -2.73  443.69    -.79  503.57   -1.41  573.26    2.81  580.25    4.67
  587.23    8.29  624.13   11.68  637.09   10.73  678.98   11.45  685.96   12.54
   746.8   12.47  805.64   16.41  847.53   15.88  852.52   17.91   861.5   17.23
#Mann= 3 , 0 , 0
       0     .12       0  315.31    .045       0  503.57     .12       0
Bank Sta=315.31,503.57
XS Rating Curve= 0 ,0
Exp/Cntr=0.3,0.1

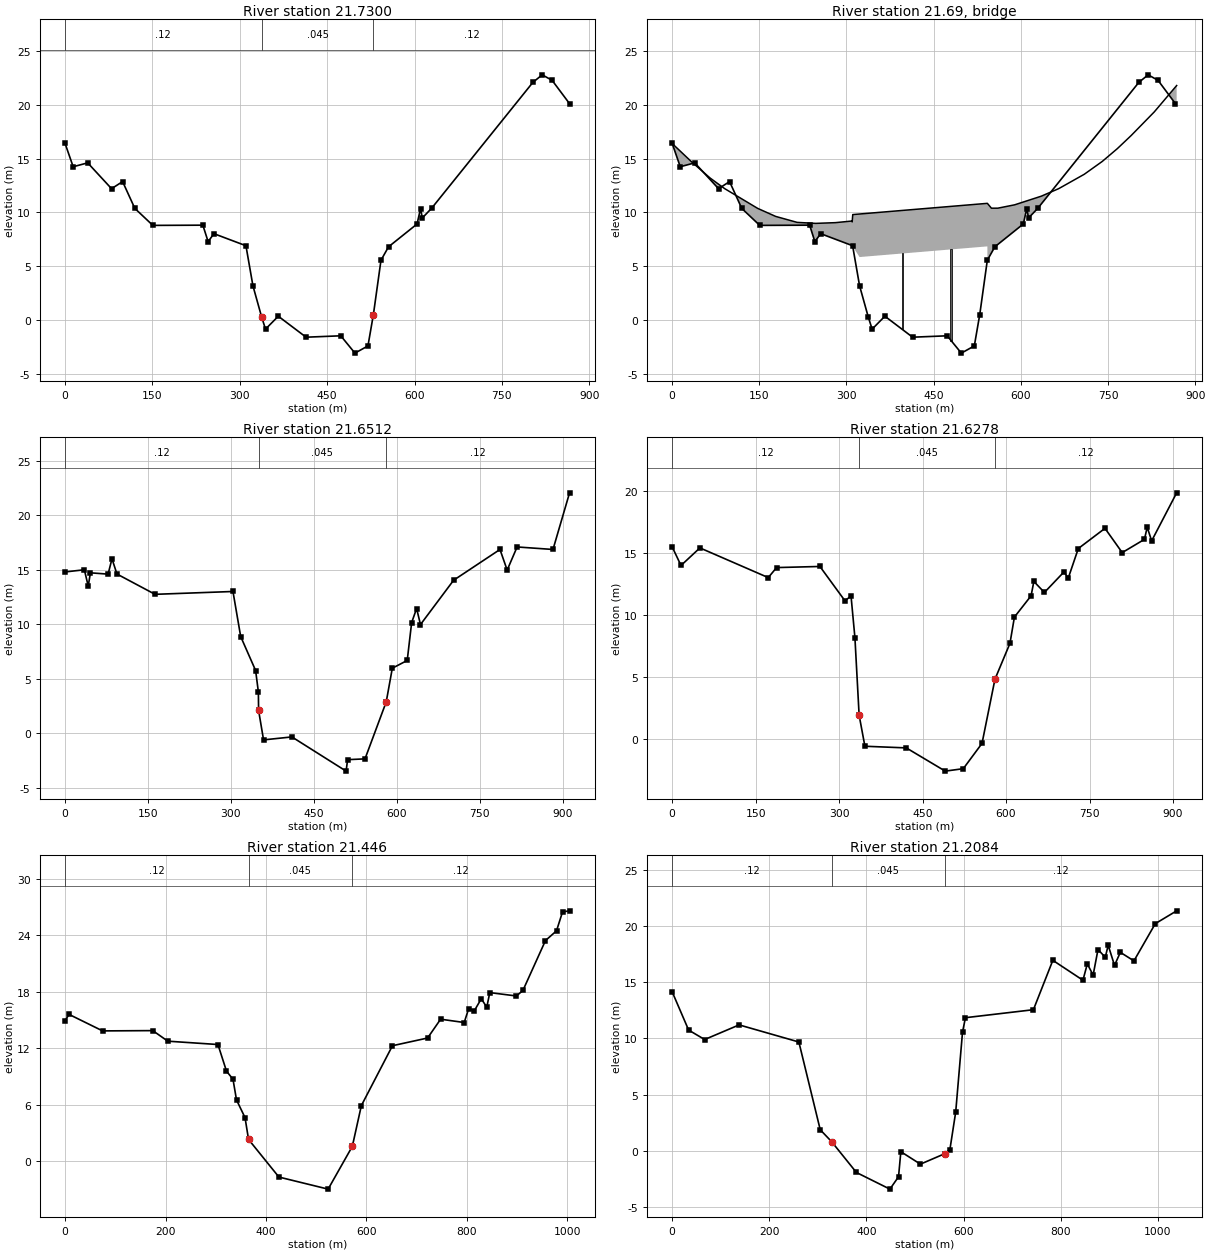
Type RM Length L Ch R = 1 ,21.7300 ,78.07,78.87,72.36
BEGIN DESCRIPTION:
RB07 (RIS 2012)
END DESCRIPTION:
XS GIS Cut Line= 3
613200.4134035995431462.32998309613364.2310035985431277.97318309
613701.7815035985430758.58108309
#Sta/Elev= 30
       0   16.43   13.98   14.25   38.94   14.61   79.88   12.21   98.85   12.87
  119.82   10.38  150.77     8.8  236.64    8.82  245.63    7.29  255.62    8.03
  310.57    6.91  322.56    3.19  337.55     .28  344.16   -.839  366.11    .361
  413.81  -1.589  473.36  -1.459  497.66  -3.069     520  -2.399  529.37     .52
  542.36    5.56  555.35    6.81   604.3    8.93   610.3   10.36   613.3    9.49
  629.28   10.39  803.13   22.09  819.11   22.79   836.1   22.28  866.07   20.11
#Mann= 3 , 0 , 0
       0     .12       0  337.55    .045       0  529.37     .12       0
Bank Sta=337.55,529.37
XS Rating Curve= 0 ,0
Exp/Cntr=0.3,0.1

Type RM Length L Ch R = 3 ,21.69   ,,,
BEGIN DESCRIPTION:
Sir Robert Bond Bridge
END DESCRIPTION:
Bridge Culvert--1,0,-1,-1, 0
Deck Dist Width WeirC Skew NumUp NumDn MinLoCord MaxHiCord MaxSubmerge Is_Ogee
38,11.6,1.4,0, 24, 24, , , 0.98, 0, 3,3,,
       0  32.787  65.573  90.411 147.209 178.157 215.094 247.039 280.947 308.836
 309.832 310.828 542.454 549.443 560.426  589.38 635.314  665.27 709.207 740.162
 766.124 790.089 829.632 868.187
  16.414   14.74  13.192  12.216  10.381   9.635   9.081   8.987   9.055   9.203
   9.127   9.805  10.849  10.398    10.4  10.711  11.516  12.216   13.55  14.743
  15.933   17.16  19.343  21.795
                                                                                
           5.805   6.849
                                
      40  72.787 105.573 130.411 187.209 218.157 255.094 287.039 320.947 348.836
 349.832 350.828 582.454 589.443 600.426  629.38 675.314  705.27 749.207 780.162
 806.124 830.089 869.632 908.187
  16.414   14.74  13.192  12.216  10.381   9.635   9.081   8.987   9.055   9.203
   9.127   9.805  10.849  10.398    10.4  10.711  11.516  12.216   13.55  14.743
  15.933   17.16  19.343  21.795
                                                                                
           5.805   6.849
                                
Pier Skew, UpSta & Num, DnSta & Num=  ,396, 2 ,420, 2 , 0 , 0 , 0 ,,
     2.5     2.5
      -5      10
     2.5     2.5
      -5      10
Pier Skew, UpSta & Num, DnSta & Num=  ,480, 2 ,504, 2 , 0 , 0 , 0 ,,
     2.5     2.5
      -5      10
     2.5     2.5
      -5      10
BR Coef=-1 , 0 , 0 ,, 0 ,,,0.8,-1,,0,
WSPro=,,,, 1 ,,,, 0 ,,,, 0 ,,,,-1 ,-1 ,-1 , 0 , 0 , 0 , 0 , 0
BC Design=,, 0 ,, 0 ,,,,,,
BC HTab HWMax=15
BC Use User HTab Curves=0
BC User HTab FreeFlow(D)= 0

Type RM Length L Ch R = 1 ,21.6512 ,16.66,23.41,27.22
BEGIN DESCRIPTION:
RB08A-1 (SEM 2019 and RIS 2012)
END DESCRIPTION:
XS GIS Cut Line= 4
  613261.6170036 5431501.6170831  613485.5193036 5431225.3765831
  613597.9675036 5431034.8761831  613782.0726036 5430754.4688831
#Sta/Elev= 30
       0    14.8   34.96      15   41.95   13.51   45.95   14.72   77.91    14.6
    84.9   16.01   93.89   14.61  162.81   12.75  303.65   13.01  317.63    8.88
   344.6    5.77  349.59    3.81     350  2.1118358.9584  -.5877410.1924  -.3154
508.2316 -3.4499510.9328  -2.399542.3898 -2.3274  580.79     2.9  591.77    5.98
  618.73    6.69  626.72   10.16   635.7   11.45  642.69    9.98  702.59   14.04
  786.45   16.86  799.43   14.97   817.4   17.09  882.29   16.86  912.24   22.05
#Mann= 3 , 0 , 0
       0     .12       0     350    .045       0  580.79     .12       0
Bank Sta=350,580.79
XS Rating Curve= 0 ,0
Exp/Cntr=0.3,0.1

Type RM Length L Ch R = 1 ,21.6278 ,187,181,169
BEGIN DESCRIPTION:
RB08A-2 (SEM 2019 and RIS 2012)
END DESCRIPTION:
XS GIS Cut Line= 4
  613295.3883036 5431498.2668831  613448.8469036 5431309.0893831
  613619.5035036 5431048.4742831  613802.0664036 5430748.1715831
#Sta/Elev= 30
       0   15.51   15.97      14   49.92   15.42  172.71   13.02  187.69   13.83
  265.56   13.92  310.49   11.15  321.47   11.53  328.46    8.16     336  1.9016
346.3911  -.6066420.7803  -.7397490.7531 -2.6166523.1646 -2.4186556.8192  -.3754
  580.07    4.81  607.03    7.71  615.02    9.83  644.97   11.55  649.96   12.71
  668.93   11.82  703.88   13.47  711.86   12.99  729.84   15.37  777.76      17
  808.71   15.04  848.65   16.11  853.64   17.09  861.63   15.99  906.55   19.87
#Mann= 3 , 0 , 0
       0     .12       0     336    .045       0  580.07     .12       0
Bank Sta=336,580.07
XS Rating Curve= 0 ,0
Exp/Cntr=0.3,0.1

Type RM Length L Ch R = 1 ,21.446  ,246,237,243
BEGIN DESCRIPTION:
RB09 (RIS 2012)
END DESCRIPTION:
XS GIS Cut Line= 2
      613498.937     5431604.995      613968.811     5430717.832
#Sta/Elev= 30
       0 14.92347.983438 15.591774.84473 13.8407174.6377 13.8715204.5756 12.7504
304.3686 12.3962321.3334  9.5776334.3065  8.7119 341.292  6.5208358.2566  4.6434
365.2419  2.3296   425.7   -1.66  523.64   -2.94571.8054  1.5971589.7674  5.9177
651.6743 12.2702721.5691 13.0853  747.53 15.0814794.4594  14.731803.4459 16.2133
814.4294 15.9548828.4083 17.2501839.3918 16.3598845.3828 17.9022898.3032 17.5443
911.2836 18.1267956.2161 23.4223 978.183 24.4555 990.165  26.4641004.144 26.5752
#Mann= 3 , 0 , 0
       0     .12       0365.2419    .045       0571.8054     .12       0
Bank Sta=365.2419,571.8054
XS Rating Curve= 0 ,0
Exp/Cntr=0.3,0.1

Type RM Length L Ch R = 1 ,21.2084 ,182.43,176.82,180.43
BEGIN DESCRIPTION:
RB10 (RIS 2012)
END DESCRIPTION:
XS GIS Cut Line= 2
613687.8244035985431702.24668309614239.1337035985430822.15858309
#Sta/Elev= 30
       0   14.15   33.98   10.74   66.97     9.9  137.93    11.2  260.88    9.68
  304.85    1.88  328.31     .82  379.34  -1.919  448.29  -3.399  466.03  -2.299
  470.78    -.07  511.08  -1.179  561.16    -.25  571.73     .11  583.72    3.46
  597.71   10.55  603.71   11.84  743.65   12.55  783.63   16.94   845.6   15.17
  854.59   16.62  866.59   15.63  876.58    17.9  891.57   17.21  897.57   18.28
  910.57   16.49  922.56   17.65  950.55   16.89  994.53    20.2  1038.5   21.34
#Mann= 3 , 0 , 0
       0     .12       0  328.31    .045       0  561.16     .12       0
Bank Sta=328.31,561.16
XS Rating Curve= 0 ,0
Exp/Cntr=0.3,0.1

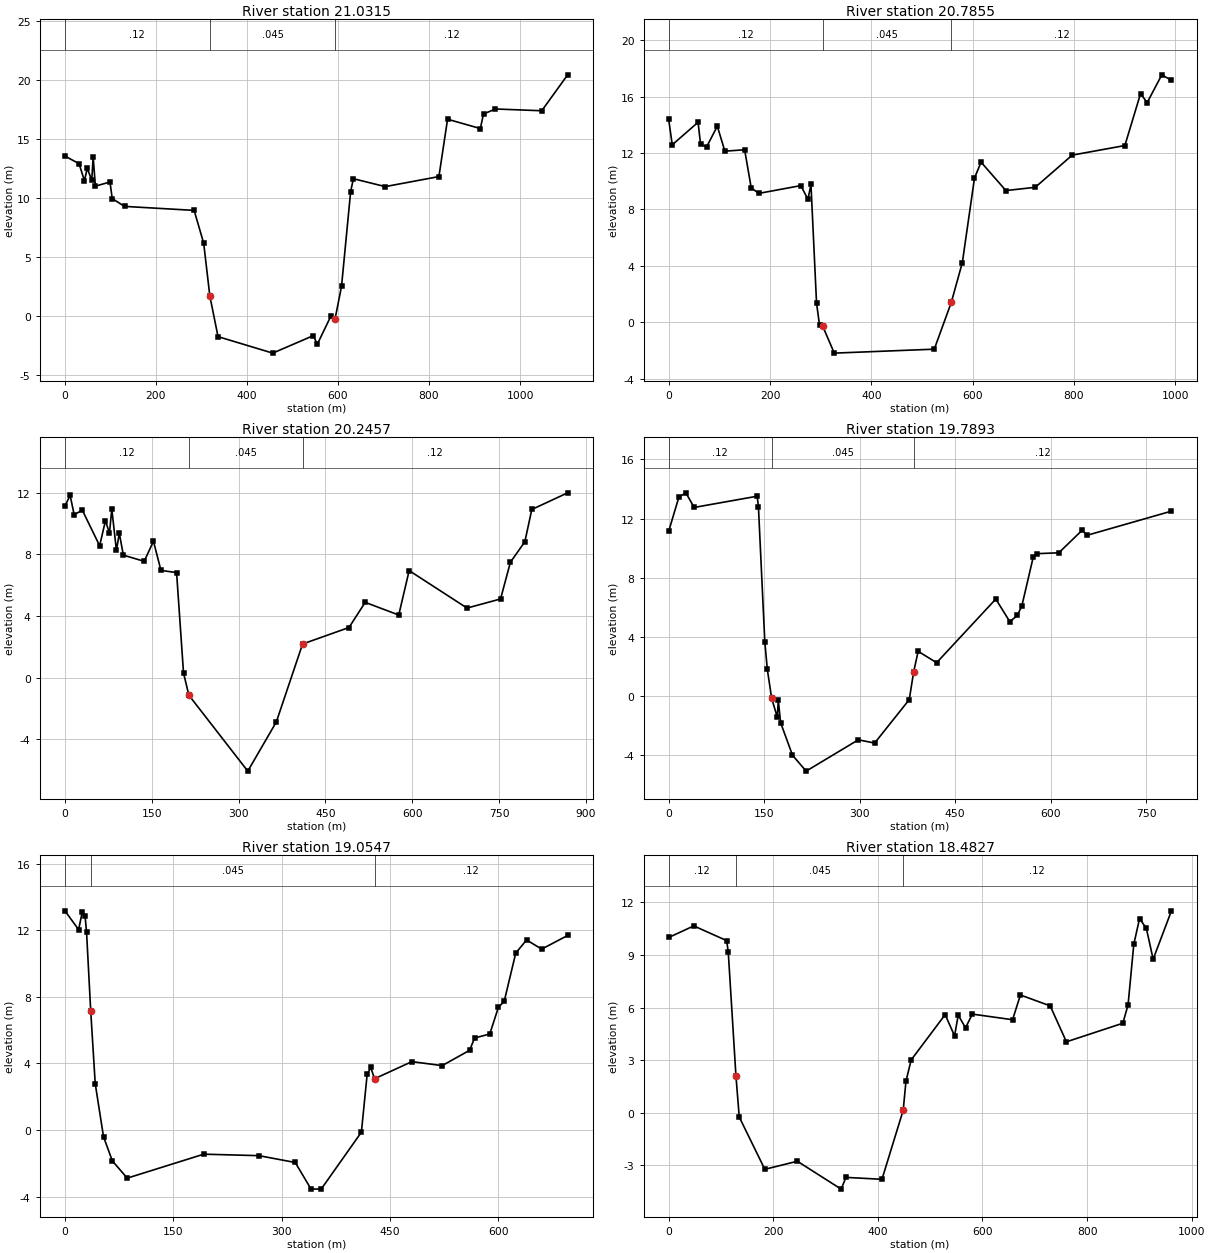
Type RM Length L Ch R = 1 ,21.0315 ,257.5,245.99,235.31
BEGIN DESCRIPTION:
RB11 (RIS 2012)
END DESCRIPTION:
XS GIS Cut Line= 2
613830.8889035985431807.30468309614416.2832035985430870.52988309
#Sta/Elev= 30
       0   13.57   30.99   12.93   42.99   11.47   48.98   12.54   58.98   11.52
   61.98    13.5   66.98   11.02   98.97   11.37  103.97    9.96  130.96     9.3
  283.91    8.96   304.9    6.17  318.36     1.7  336.39  -1.759  456.61  -3.159
  546.03  -1.669  554.37  -2.419  584.81     .02   593.7    -.23   607.8    2.53
   627.8   10.56   633.8   11.65  703.77   10.98  821.74   11.83  840.73    16.7
  912.71   15.91  919.71   17.14   945.7   17.57 1047.67   17.42 1104.65   20.47
#Mann= 3 , 0 , 0
       0     .12       0  318.36    .045       0   593.7     .12       0
Bank Sta=318.36,593.7
XS Rating Curve= 0 ,0
Exp/Cntr=0.3,0.1

Type RM Length L Ch R = 1 ,20.7855 ,545.23,539.81,536.88
BEGIN DESCRIPTION:
RB12 (RIS 2012)
END DESCRIPTION:
XS GIS Cut Line= 2
614081.4162035985431948.71658309614521.7383035985431059.23598309
#Sta/Elev= 30
       0   14.38       7   12.58   57.97   14.18   62.97   12.61   74.96   12.44
   95.95    13.9  110.94   12.13  149.92   12.23  162.92    9.53  177.91    9.14
  260.87    9.69  274.86    8.72  280.86    9.77  291.85    1.37  297.85    -.22
  303.91    -.26  326.89  -2.179  524.29  -1.899  557.93    1.42  579.71    4.24
   603.7   10.23  616.69   11.35  665.67    9.34  723.64    9.57   796.6   11.85
  900.55   12.53  931.53   16.21  944.53   15.57  973.51   17.54   992.5   17.15
#Mann= 3 , 0 , 0
       0     .12       0  303.91    .045       0  557.93     .12       0
Bank Sta=303.91,557.93
XS Rating Curve= 0 ,0
Exp/Cntr=0.3,0.1

Type RM Length L Ch R = 1 ,20.2457 ,458.18,456.43,465.88
BEGIN DESCRIPTION:
RB12A (SEM 2019)
END DESCRIPTION:
XS GIS Cut Line= 2
614588.1294035995432192.95828309614880.6656035995431375.34388309
#Sta/Elev= 30
       0   11.13    8.99   11.81   15.99   10.56   29.98   10.86   59.96    8.55
   69.95   10.17   76.94    9.37   80.94   10.93   88.94    8.25   93.93    9.36
  100.93    7.94   136.9    7.54  152.89    8.84  165.88    6.95  192.86    6.81
  204.85      .3  214.07   -1.14  315.83   -6.06  365.16   -2.87  410.48    2.18
  490.65    3.25  518.63    4.88  576.58    4.06  594.57    6.94   694.5    4.51
  752.45     5.1  769.44    7.48  794.42    8.81  806.41    10.9  868.37   11.98
#Mann= 3 , 0 , 0
       0     .12       0  214.07    .045       0  410.48     .12       0
Bank Sta=214.07,410.48
XS Rating Curve= 0 ,0
Exp/Cntr=0.3,0.1

Type RM Length L Ch R = 1 ,19.7893 ,785.36,734.63,757.01
BEGIN DESCRIPTION:
R32 (RIS 2013)
END DESCRIPTION:
XS GIS Cut Line= 2
615039.1921035985432306.32618309615279.8032035995431553.90208309
#Sta/Elev= 30
       0   11.14      16   13.45      27   13.74      40   12.75  138.99   13.51
  140.99   12.81  150.99    3.67  154.99    1.78  161.78    -.17  170.64   -1.45
  172.22     -.3  175.78   -1.81  194.48   -4.02  215.97    -5.1  297.95   -2.98
   323.6    -3.2  377.98    -.26  384.95    1.63  391.98    3.01  420.98    2.24
  513.97    6.55  535.97    5.02  547.97    5.44  554.97     6.1  572.97    9.42
  577.97    9.62  612.97    9.68  649.97   11.22  656.96   10.86  789.96    12.5
#Mann= 3 , 0 , 0
       0     .12       0  161.78    .045       0  384.95     .12       0
Bank Sta=161.78,384.95
XS Rating Curve= 0 ,0
Exp/Cntr=0.3,0.1

Type RM Length L Ch R = 1 ,19.0547 ,647.22,571.99,516.76
BEGIN DESCRIPTION:
R33 (RIS 2013)
END DESCRIPTION:
XS GIS Cut Line= 2
615792.7878035995432458.06978309615909.7769035995431771.74048309
#Sta/Elev= 30
       0   13.17   18.98   12.04   23.97   13.09   27.97   12.84   29.97   11.87
   35.69    7.17   41.95    2.79   53.43     -.4   65.62   -1.85   86.28   -2.89
  192.27   -1.45  268.74   -1.54  318.95   -1.95  340.74   -3.54  354.86   -3.55
  410.55    -.13  418.54    3.34  423.53    3.76  428.74    3.08  480.47    4.11
  522.42    3.87  560.38    4.79  567.37    5.53  588.35    5.77  600.34    7.38
  608.33    7.73  624.31   10.63  639.29   11.42  660.27   10.87  696.23   11.69
#Mann= 3 , 0 , 0
       0     .12       0   35.69    .045       0  428.74     .12       0
Bank Sta=35.69,428.74
XS Rating Curve= 0 ,0
Exp/Cntr=0.3,0.1

Type RM Length L Ch R = 1 ,18.4827 ,245.29,397.53,532.43
BEGIN DESCRIPTION:
R34 (RIS 2013)
END DESCRIPTION:
XS GIS Cut Line= 2
616475.0278035985432564.42628309616224.8114035995431636.20268309
#Sta/Elev= 30
       0      10   47.97   10.66  110.93    9.82  113.92    9.16  128.56    2.12
  134.91    -.24  183.81  -3.221  246.03  -2.761  329.79  -4.351  338.91  -3.681
  407.82  -3.791  448.43     .15  453.69     1.8  463.69    3.02  528.64     5.6
  546.63    4.39  553.63    5.57  567.62    4.85  580.61    5.63  657.56    5.31
  672.55    6.72  729.51     6.1  760.49    4.05  868.41    5.11  878.41    6.16
   889.4    9.62  900.39   11.08  913.38   10.52  926.37    8.76  961.35   11.52
#Mann= 3 , 0 , 0
       0     .12       0  128.56    .045       0  448.43     .12       0
Bank Sta=128.56,448.43
XS Rating Curve= 0 ,0
Exp/Cntr=0.3,0.1

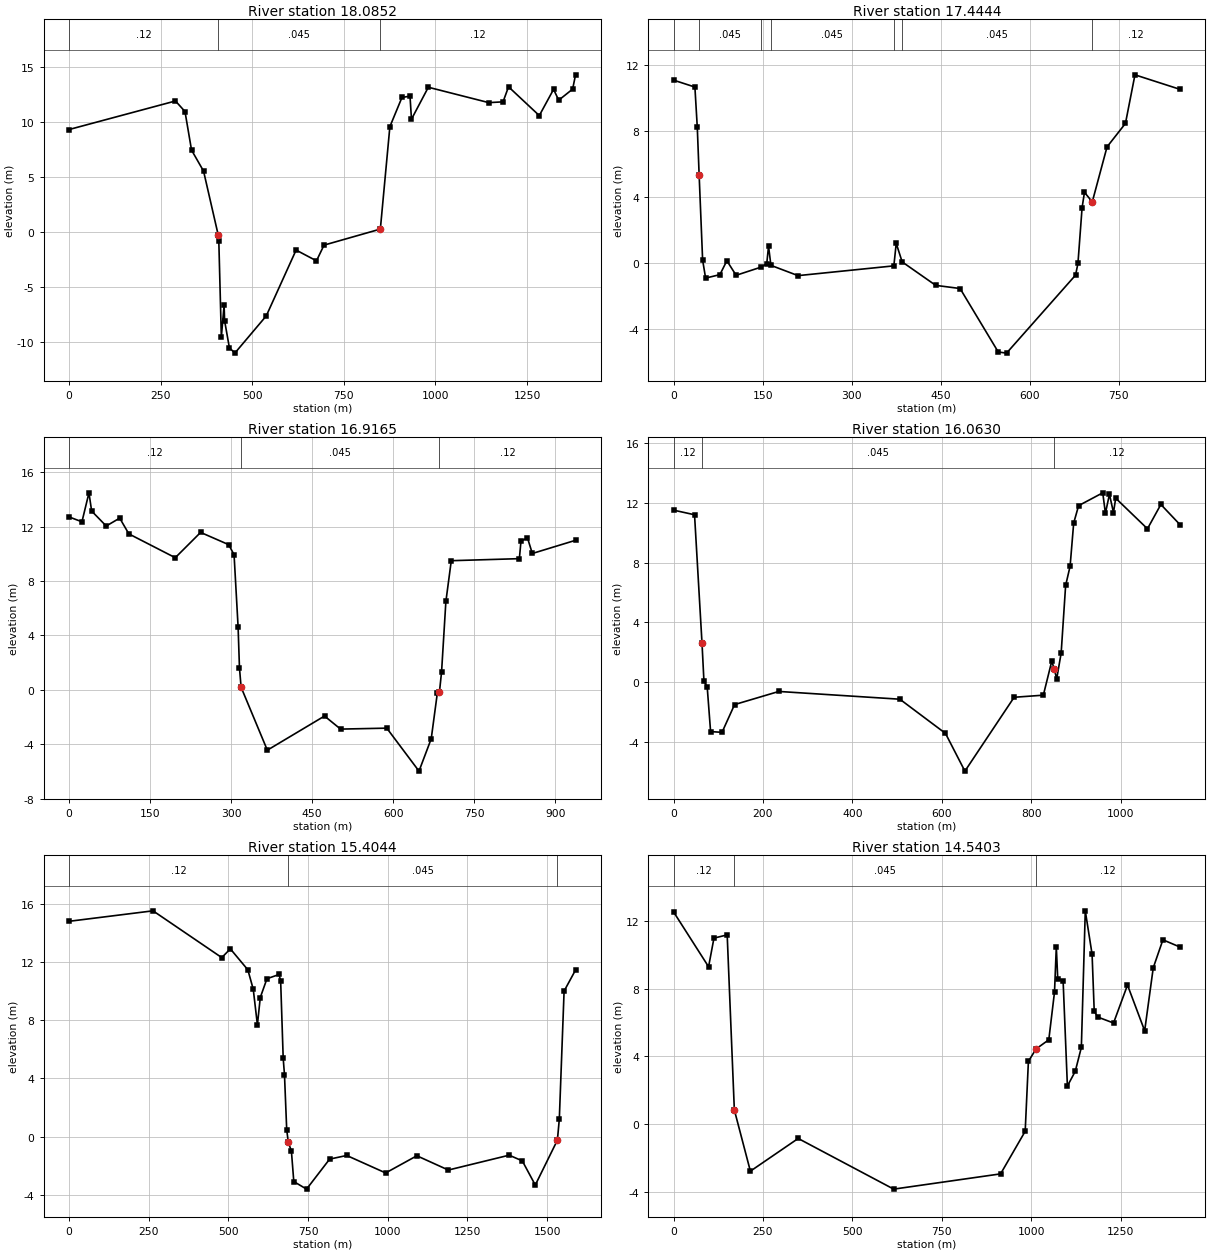
Type RM Length L Ch R = 1 ,18.0852 ,647.41,640.75,696.96
BEGIN DESCRIPTION:
Jumpers Brook - R35 (RIS 2013)
END DESCRIPTION:
XS GIS Cut Line= 5
  616550.8643036 5432633.4600831  616629.3533036 5432326.8587831
  616606.0038036 5432261.3738831  616858.1945036 5431783.3442831
  617170.9606036 5431451.9167831
#Sta/Elev= 30
       0    9.35  290.53   11.95  316.49   10.99  334.36    7.48  367.14    5.57
  407.01    -.23  408.77    -.76   415.7   -9.53  423.24   -6.64  424.58   -8.05
  437.59   -10.5   452.5     -11   538.3   -7.61  619.67   -1.62  675.28    -2.6
  695.85   -1.17  849.56     .29  875.53    9.61   908.5   12.27  930.48   12.39
  934.48   10.29  980.45    13.2 1145.34    11.8 1184.32   11.87 1199.31   13.24
 1283.26   10.62 1322.23   13.01 1336.23   12.02  1374.2   13.03  1382.2   14.33
#Mann= 3 , 0 , 0
       0     .12       0  407.01    .045       0  849.56     .12       0
Bank Sta=407.01,849.56
XS Rating Curve= 0 ,0
Exp/Cntr=0.3,0.1

Type RM Length L Ch R = 1 ,17.4444 ,523.43,527.87,620.32
BEGIN DESCRIPTION:
R36 (RIS 2013)
END DESCRIPTION:
XS GIS Cut Line= 2
616758.7171035995432879.29438309617369.7712035985432284.14078309
#Sta/Elev= 30
       0   11.07      36   10.65      40    8.22   43.12    5.34      49     .18
   54.03   -.911   78.09   -.701   89.79    .139  105.42   -.741     148    -.24
     157    -.03     160    1.02     164    -.14  209.67   -.761     371    -.17
     375    1.19     385     .07  441.52  -1.351  482.53  -1.541  546.77  -5.381
  560.78  -5.451  676.99    -.73  680.99    -.02  687.99    3.36  691.99    4.28
  705.12     3.7  729.99    7.03  760.99    8.45  776.99   11.39  852.99   10.51
#Mann= 7 ,-1 , 0
       0     .12       0   43.12    .045       0     148     .12       0
     164    .045       0     371     .12       0     385    .045       0
  705.12     .12       0
Bank Sta=43.12,705.12
XS Rating Curve= 0 ,0
Exp/Cntr=0.3,0.1

Type RM Length L Ch R = 1 ,16.9165 ,1014.1,853.51,802.13
BEGIN DESCRIPTION:
R37 (RIS 2013)
END DESCRIPTION:
XS GIS Cut Line= 3
  616965.9082036 5433251.0869831  617228.0941036 5433090.5394831
  617767.6872036 5432765.6038831
#Sta/Elev= 30
       0   12.71   23.96   12.35   36.93   14.48   41.92   13.14   68.87   12.04
   93.83   12.62   110.8   11.46  196.64    9.71  243.55   11.57  295.46   10.67
  305.44    9.93  312.87    4.64  315.43    1.61  318.43     .19  366.98  -4.442
   472.8  -1.932  502.52  -2.892     588  -2.822  647.62  -5.982  670.25  -3.602
  681.59   -.232  685.36     -.2  689.36     1.3  697.36    6.49  707.35    9.49
  833.33    9.64  836.33   10.93  848.33   11.17  857.32   10.02  937.31   10.99
#Mann= 3 , 0 , 0
       0     .12       0  318.43    .045       0  685.36     .12       0
Bank Sta=318.43,685.36
XS Rating Curve= 0 ,0
Exp/Cntr=0.3,0.1

Type RM Length L Ch R = 1 ,16.0630 ,751.89,658.58,575.09
BEGIN DESCRIPTION:
R38 (RIS 2013)
END DESCRIPTION:
XS GIS Cut Line= 2
617160.0942035985434061.37518309618116.3002035985433453.83388309
#Sta/Elev= 30
       0   11.52      47   11.21   63.65    2.63   67.99     .08   75.36   -.342
    82.9  -3.322  108.46  -3.372  136.54  -1.512  235.51   -.632  506.19  -1.152
  608.19  -3.442  651.65  -5.972  761.73  -1.022  827.07   -.882  845.92     1.4
  851.82     .84  856.91     .21  866.91    1.94  876.91    6.47  886.91    7.76
  894.91   10.65  905.91   11.82   959.9   12.68   965.9   11.31   974.9   12.58
   983.9   11.36   988.9   12.32 1059.89   10.27 1089.89    11.9 1132.89   10.54
#Mann= 3 , 0 , 0
       0     .12       0   63.65    .045       0  851.82     .12       0
Bank Sta=63.65,851.82
XS Rating Curve= 0 ,0
Exp/Cntr=0.3,0.1

Type RM Length L Ch R = 1 ,15.4044 ,907.64,864.13,870.73
BEGIN DESCRIPTION:
R39 (RIS 2013)
END DESCRIPTION:
XS GIS Cut Line= 3
  617147.8096036 5435063.4864831  617579.2289036 5434707.7550831
  618310.3579036 5433982.0282831
#Sta/Elev= 30
       0   14.78  263.61    15.5  479.29   12.29  506.25   12.89  561.17   11.45
  578.15   10.11  591.14    7.67  600.13    9.55  621.12   10.84  659.08   11.13
  664.08   10.68  672.07    5.37  676.07    4.26  683.06     .48  688.06    -.39
  697.81   -.993   705.3  -3.083  745.35  -3.603  817.71  -1.543  871.38  -1.293
  993.54  -2.493 1091.36  -1.313 1190.16  -2.293 1381.04  -1.273 1422.18  -1.663
 1462.98  -3.323 1532.38    -.24 1538.38    1.21 1553.36    9.99 1589.33   11.44
#Mann= 3 , 0 , 0
       0     .12       0  688.06    .045       0 1532.38     .12       0
Bank Sta=688.06,1532.38
XS Rating Curve= 0 ,0
Exp/Cntr=0.3,0.1

Type RM Length L Ch R = 1 ,14.5403 ,930.8,944.63,980.79
BEGIN DESCRIPTION:
R40 (RIS 2013)
END DESCRIPTION:
XS GIS Cut Line= 2
618260.4525035985435323.05038309619155.9164035985434226.32078309
#Sta/Elev= 30
       0   12.53   97.99    9.29  112.99   10.98  149.99   11.17  169.98     .84
  214.81  -2.773  348.47   -.843  615.41  -3.833  914.18  -2.933   982.9    -.42
   991.9    3.71 1013.35    4.44 1048.89    4.98 1064.89     7.8 1069.89   10.47
 1073.89    8.58 1088.89    8.47 1100.89    2.25 1122.88    3.12 1139.88    4.53
 1150.88   12.59 1169.88   10.03 1175.88    6.66 1185.88    6.32 1229.87    5.97
 1268.87    8.21 1316.86    5.51 1340.86    9.23 1367.86   10.88 1415.86   10.45
#Mann= 3 , 0 , 0
       0     .12       0  169.98    .045       0 1013.35     .12       0
Bank Sta=169.98,1013.35
XS Rating Curve= 0 ,0
Exp/Cntr=0.3,0.1