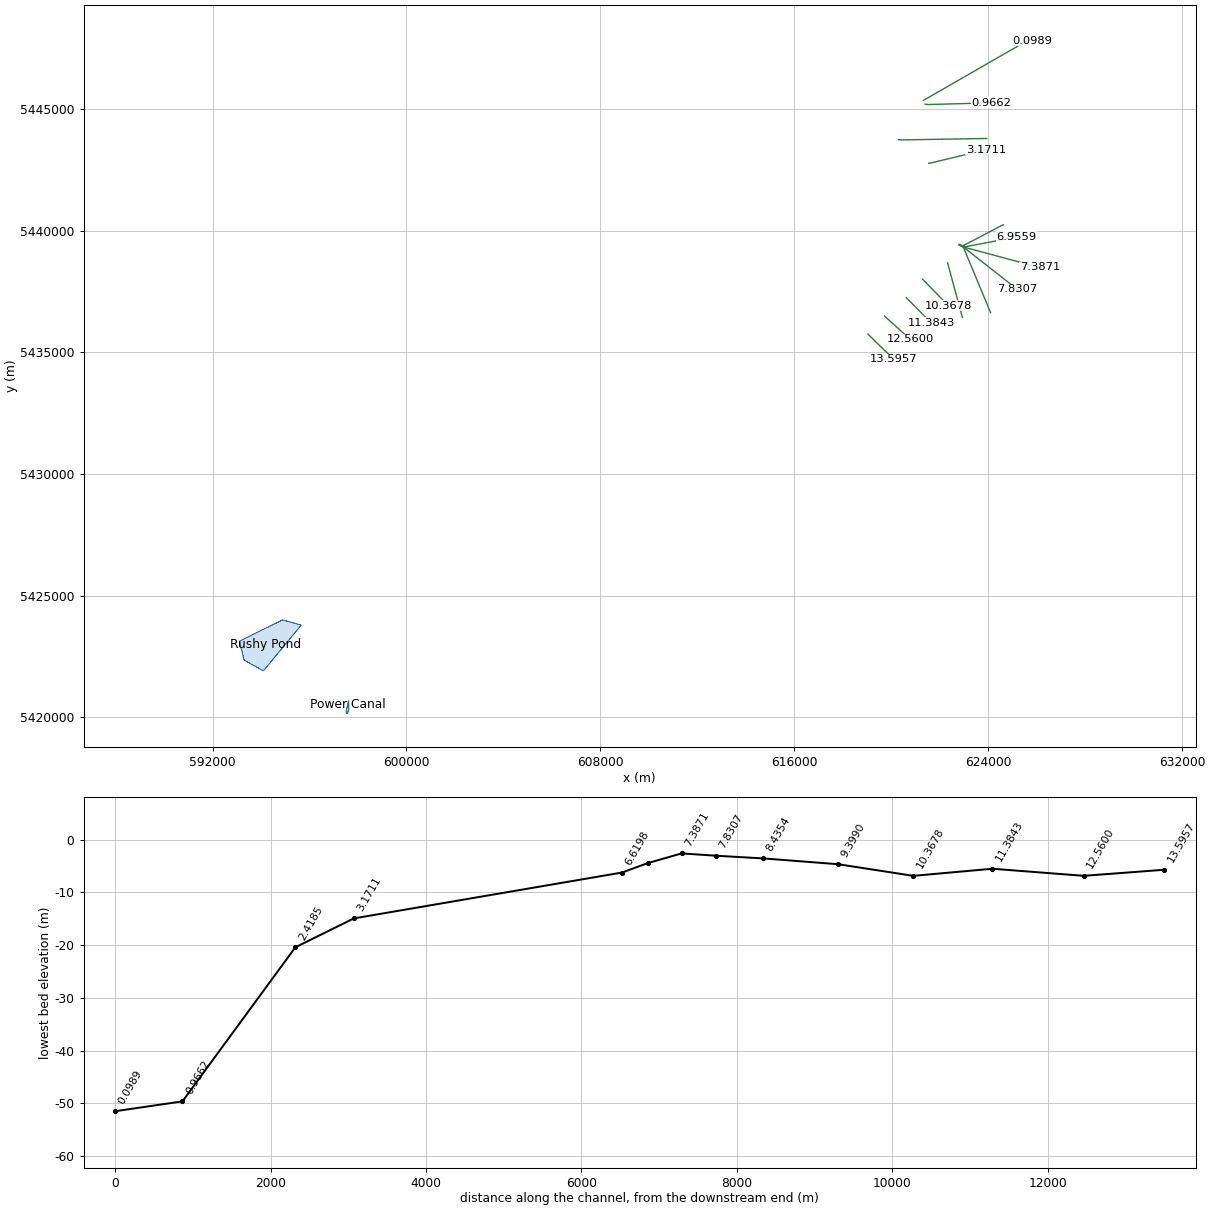
HEC-RAS study Unsteady_RAS.prj: Unsteady_RAS

--- Unsteady_RAS.g01 (geometry) --- (continued)

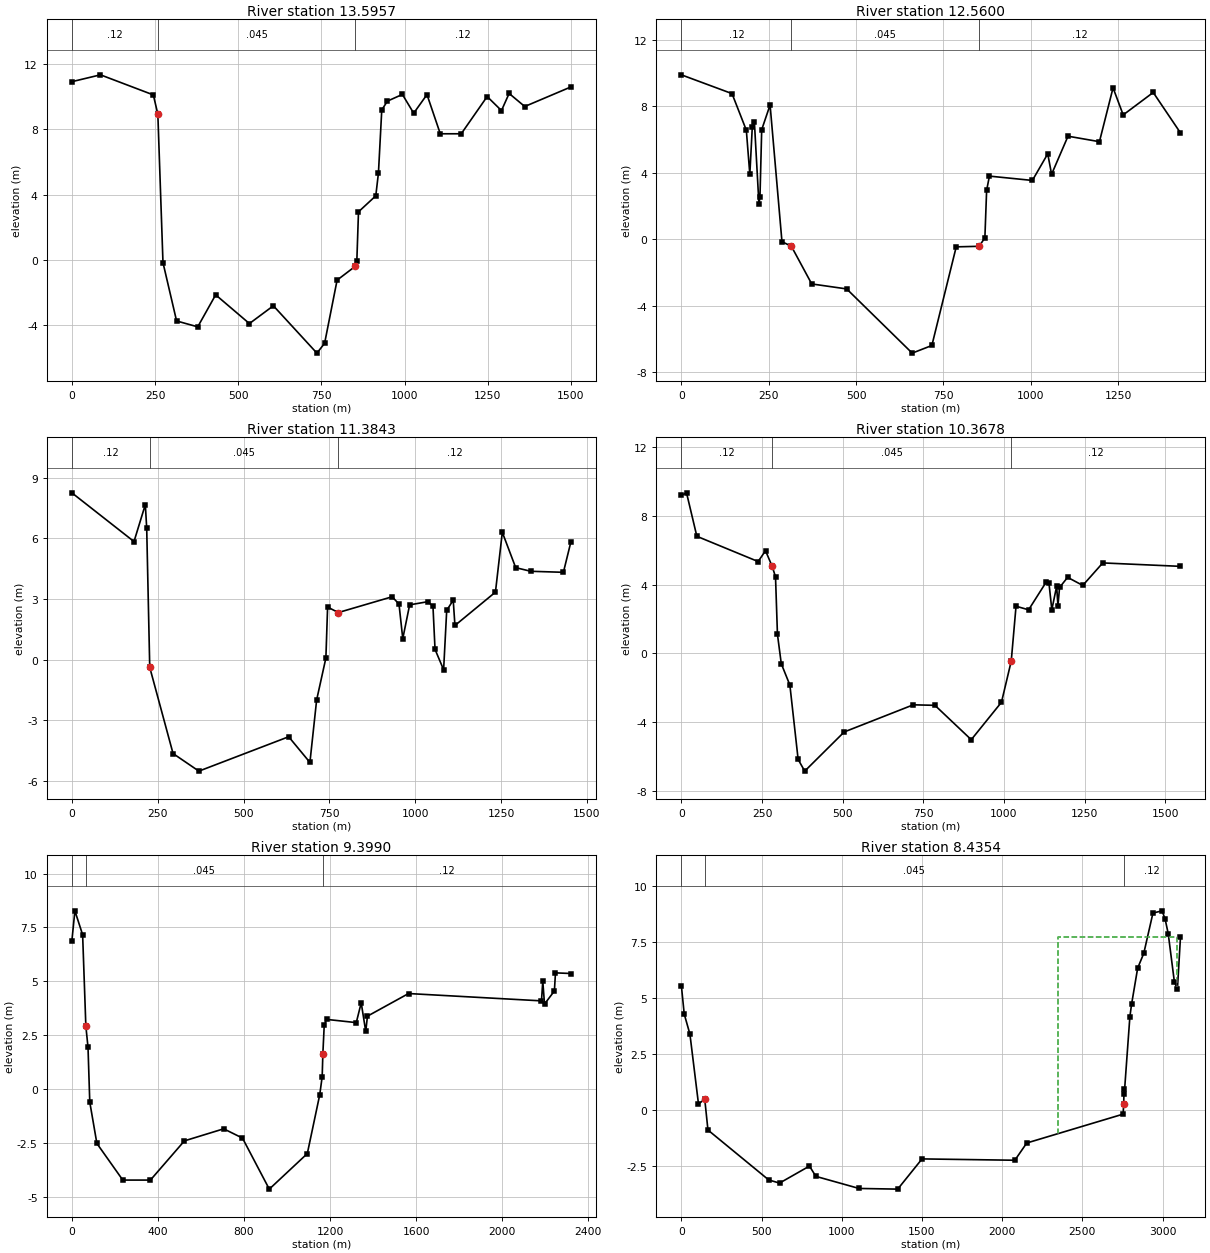
Type RM Length L Ch R = 1 ,13.5957 ,1026.18,1035.67,1099.38
BEGIN DESCRIPTION:
R41 (RIS 2013)
END DESCRIPTION:
XS GIS Cut Line= 2
619029.9852035995435751.21118309620104.7006035985434704.47138309
#Sta/Elev= 30
       0   10.92   85.96   11.34  244.87   10.11  258.41    8.93  273.86    -.16
  314.76  -3.733  378.34  -4.093  432.23  -2.133  533.66  -3.893  605.71  -2.803
  736.52  -5.703  759.68  -5.103  797.25  -1.233   852.2    -.38  856.56    -.07
  861.56    2.95  913.53    3.93  921.53    5.33  931.52    9.19  948.51    9.73
  993.49   10.14 1027.47    8.99 1067.45   10.13 1107.43    7.73  1170.4    7.73
 1248.35   10.01 1291.33    9.15 1314.32    10.2 1361.29     9.4 1500.22    10.6
#Mann= 3 , 0 , 0
       0     .12       0  258.41    .045       0   852.2     .12       0
Bank Sta=258.41,852.2
XS Rating Curve= 0 ,0
Exp/Cntr=0.3,0.1

Type RM Length L Ch R = 1 ,12.5600 ,1171.27,1175.67,1176.86
BEGIN DESCRIPTION:
R42 (RIS 2013)
END DESCRIPTION:
XS GIS Cut Line= 2
619716.0507035985436490.46238309620776.3559035985435533.48708309
#Sta/Elev= 30
       0    9.88  144.93    8.75  185.91    6.55   195.9    3.89   202.9    6.72
   208.9    7.07  221.89    2.14  224.89    2.51  229.89    6.58  253.88    8.07
  287.86    -.15  314.85    -.43  373.03  -2.693  473.12  -2.993   660.6  -6.853
  716.86  -6.393  786.56   -.463  852.06    -.43  868.57     .08  873.57    2.93
  881.56    3.79  1004.5    3.53 1048.48    5.13 1059.48     3.9 1106.45    6.19
 1196.41    5.86 1235.39     9.1 1264.37    7.47 1350.33    8.82 1428.29    6.39
#Mann= 3 , 0 , 0
       0     .12       0  314.85    .045       0  852.06     .12       0
Bank Sta=314.85,852.06
XS Rating Curve= 0 ,0
Exp/Cntr=0.3,0.1

Type RM Length L Ch R = 1 ,11.3843 ,1031.75,1016.52,1068.63
BEGIN DESCRIPTION:
R43 (RIS 2013)
END DESCRIPTION:
XS GIS Cut Line= 2
620621.5247035995437243.18888309621640.5493035985436206.30378309
#Sta/Elev= 30
       0    8.25  180.98    5.84  213.97    7.67  217.97     6.5  226.83    -.38
  294.73  -4.642  369.99  -5.512  631.54  -3.812  693.39  -5.082  712.99  -1.992
   739.9     .08   744.9     2.6  776.19    2.33  932.87    3.11  952.87    2.75
  963.87    1.04  983.86    2.71 1037.86    2.87 1051.85    2.63 1057.85     .51
 1082.85     -.5 1091.85    2.44 1110.84    2.94 1115.84    1.69 1233.82    3.34
 1253.82     6.3 1292.81    4.55 1336.81    4.37 1431.79    4.32 1453.79    5.84
#Mann= 3 , 0 , 0
       0     .12       0  226.83    .045       0  776.19     .12       0
Bank Sta=226.83,776.19
XS Rating Curve= 0 ,0
Exp/Cntr=0.3,0.1

Type RM Length L Ch R = 1 ,10.3678 ,1291.42,968.8,733.55
BEGIN DESCRIPTION:
R43A (SEM 2019)
END DESCRIPTION:
XS GIS Cut Line= 2
621280.7425035985438011.19808309622364.1722035995436906.36678309
#Sta/Elev= 30
       0    9.19   15.99    9.34   47.98    6.81  237.91    5.34   260.9    5.97
  281.53    5.06  291.89    4.45  297.89     1.1   309.8    -.61  336.42   -1.85
  362.03   -6.18  382.47   -6.86  504.83   -4.58  719.03      -3  786.19   -3.03
  898.77   -5.03  992.49   -2.85 1022.72    -.46 1037.61    2.74  1076.6    2.53
 1130.58    4.13 1139.57    4.11 1148.57    2.54 1163.56     3.9 1167.56    2.76
 1172.56    3.83 1197.55    4.42 1244.53    3.95 1306.51    5.26 1547.42    5.06
#Mann= 3 , 0 , 0
       0     .12       0  281.53    .045       0 1022.72     .12       0
Bank Sta=281.53,1022.72
XS Rating Curve= 0 ,0
Exp/Cntr=0.3,0.1

Type RM Length L Ch R = 1 ,9.3990  ,991.28,963.65,1694.22
BEGIN DESCRIPTION:
Beatons Point - R43B (SEM 2019)
END DESCRIPTION:
XS GIS Cut Line= 2
622322.3468035985438673.13068309622931.2769035995436434.97468309
#Sta/Elev= 30
       0    6.87      14    8.27   49.99    7.16   64.99    2.91   74.98    1.94
    83.2    -.61  116.28   -2.53  236.71   -4.23  365.03   -4.23     523   -2.41
  705.63   -1.85  792.85   -2.28   917.5   -4.65  1094.2      -3  1151.9    -.27
 1163.29     .57 1166.44    1.63 1172.75    2.95 1183.75    3.23 1321.72    3.08
 1344.71       4 1365.71    2.67 1373.71    3.38 1564.66    4.43 2182.53    4.09
 2188.52    5.01 2196.52    3.94 2242.51    4.55 2247.51    5.39 2319.49    5.36
#Mann= 3 , 0 , 0
       0     .12       0   64.99    .045       0 1166.44     .12       0
Bank Sta=64.99,1166.44
XS Rating Curve= 0 ,0
Exp/Cntr=0.3,0.1

Type RM Length L Ch R = 1 ,8.4354  ,6.88,604.64,1333.08
BEGIN DESCRIPTION:
Rattling Brook - R43C (SEM 2019)
END DESCRIPTION:
XS GIS Cut Line= 3
     622801.7995    5439411.2536     622973.3818    5439317.1031
      624096.175    5436625.8682
#Sta/Elev= 30
       0   5.537   17.79    4.27   53.38    3.37  106.75     .25  145.67     .47
  165.74    -.91   544.7   -3.14  612.15   -3.28  798.68   -2.52  838.52   -2.98
  1107.6   -3.52 1348.87   -3.55 1500.56    -2.2 2079.24   -2.26 2153.45   -1.49
 2754.48     -.2 2757.73     .26 2760.41     .91 2761.33     .68 2796.32    4.14
 2806.83     4.7 2844.94    6.32 2883.06    6.98 2940.24    8.78 2997.42    8.88
 3016.48     8.5 3035.54    7.86 3073.66    5.72 3092.72    5.37 3111.84   7.697
#Mann= 3 , 0 , 0
       0      .1       0  145.67    .045       0 2757.73     .12       0
#XS Ineff= 1 ,-1
 2350.253087.929   7.697
Permanent Ineff=
       F
Bank Sta=145.67,2757.73
XS Rating Curve= 0 ,0
Exp/Cntr=0.3,0.1

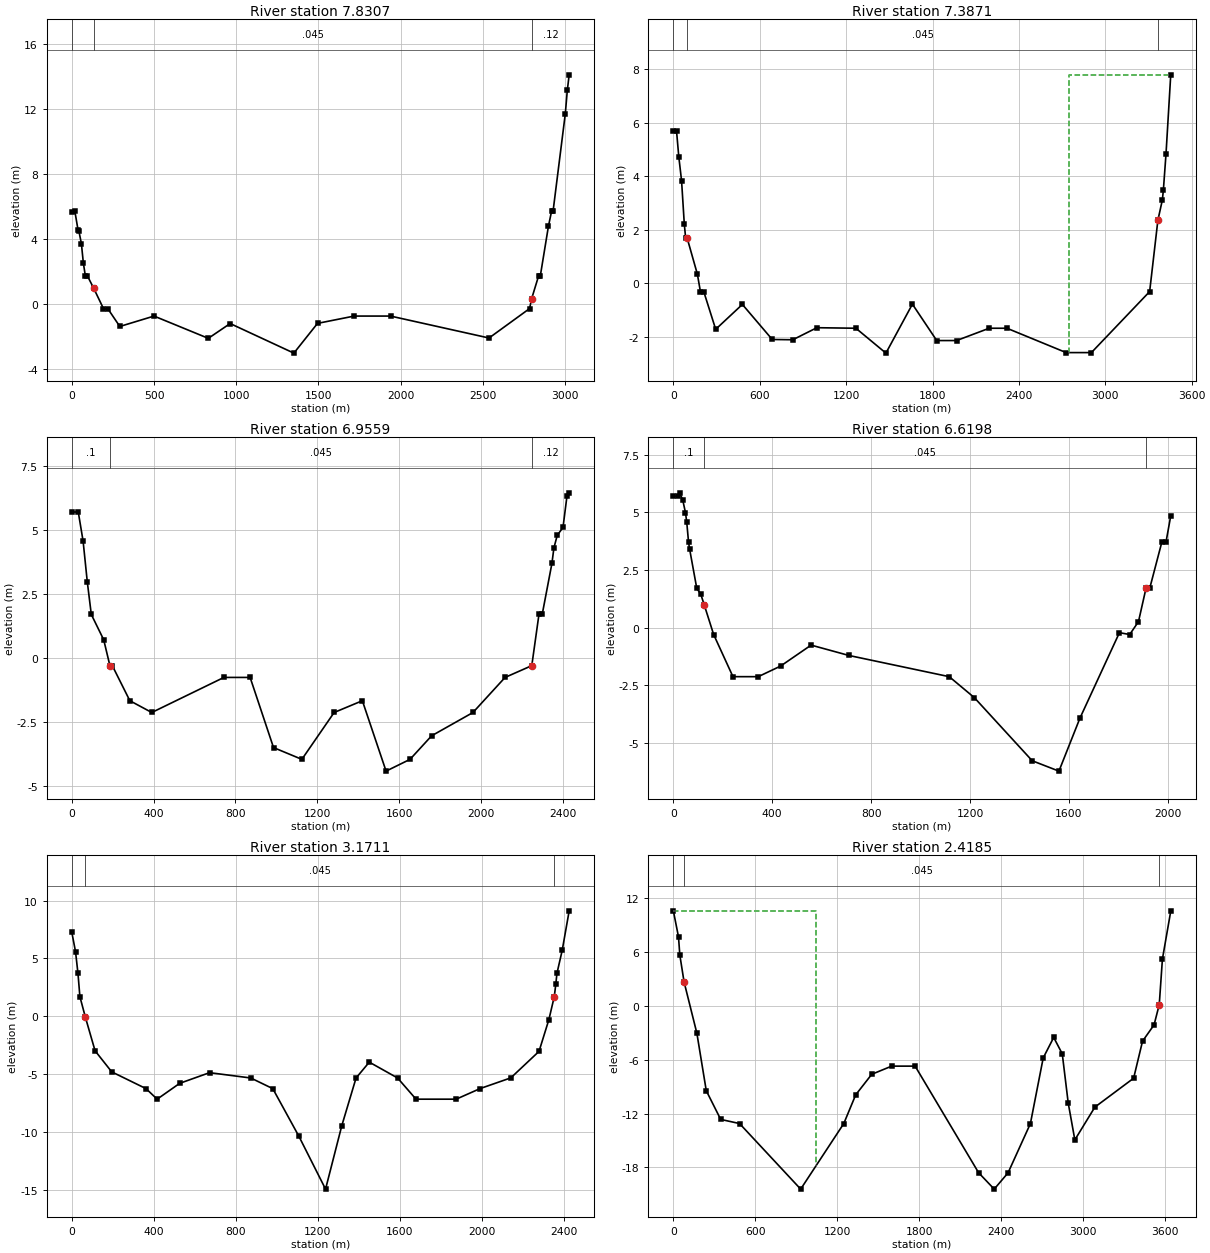
Type RM Length L Ch R = 1 ,7.8307  ,6.81,443.64,1256.91
XS GIS Cut Line= 4
      622800.583    5439417.0572     622897.9524    5439369.6848
     622994.6865    5439306.8048     625201.4618    5437581.8264
#Sta/Elev= 30
       0   5.617   18.48   5.697   38.46   4.507   43.16   4.467   58.41   3.697
   70.28   2.507   82.62   1.697    95.5   1.697  132.28    .967  192.59   -.303
     222   -.353  292.07  -1.403  500.16   -.763  830.18  -2.133  963.03  -1.223
 1350.48  -3.043 1494.29  -1.213 1717.19   -.763 1938.18   -.763 2537.25  -2.113
 2783.76   -.303 2796.44    .307 2838.37   1.697 2848.94   1.6972898.679   4.777
 2917.83   5.697 2926.76   5.697 3001.22  11.697 3013.22  13.127 3024.62  14.077
#Mann= 3 , 0 , 0
       0      .1       0  132.28    .045       0 2796.44     .12       0
Bank Sta=132.28,2796.44
XS Rating Curve= 0 ,0
Exp/Cntr=0.3,0.1

Type RM Length L Ch R = 1 ,7.3871  ,10.05,431.1,1773.96
BEGIN DESCRIPTION:
Norris Arm
END DESCRIPTION:
XS GIS Cut Line= 3
     622802.6863    5439421.3447     622990.5081    5439322.6188
     626122.7197    5438484.0725
#Sta/Elev= 30
       0   5.698   22.11   5.698    37.8   4.738   57.12   3.838   75.95   2.228
   85.37   1.698   95.91   1.698  166.88    .348  187.96   -.302  211.16   -.302
  294.09  -1.712  479.31   -.782  686.77  -2.092  829.84  -2.102  996.93  -1.652
 1267.92  -1.672  1476.4  -2.602 1660.35   -.772 1829.41  -2.132 1967.22  -2.132
  2193.9  -1.672 2316.96  -1.672 2728.21  -2.582 2903.69  -2.5823308.159   -.302
 3365.26   2.3583396.621   3.1283403.741   3.508 3421.91   4.848 3454.71   7.798
#Mann= 3 , 0 , 0
       0      .1       0   95.91    .045       0 3365.26     .12       0
#XS Ineff= 1 ,-1
 2748.79 3454.71   7.794
Permanent Ineff=
       F
Bank Sta=95.91,3365.26
XS Rating Curve= 0 ,0
Exp/Cntr=0.3,0.1

Type RM Length L Ch R = 1 ,6.9559  ,29.88,336.16,697.08
XS GIS Cut Line= 5
     622800.7667     5439428.139     622942.1973    5439356.9893
     623066.2609    5439337.9875     624867.5565    5439681.5371
     625173.0415    5439751.8944
#Sta/Elev= 30
       0   5.698   31.73   5.698   55.36   4.558   75.66   2.978   95.35   1.698
  156.02    .708   186.3   -.302  198.03   -.302  283.75  -1.672  390.98  -2.132
  743.58   -.762  871.59   -.762  985.99  -3.502 1124.49  -3.962 1282.15  -2.132
 1420.21  -1.672 1536.08  -4.422 1653.16  -3.962 1758.73  -3.042 1960.77  -2.132
 2117.71   -.762 2248.27   -.302 2283.28   1.698 2299.17   1.698 2346.82   3.698
  2356.4   4.298 2372.74   4.788 2400.88   5.098  2420.2   6.318 2431.03   6.448
#Mann= 3 , 0 , 0
       0      .1       0   186.3    .045       0 2248.27     .12       0
Bank Sta=186.3,2248.27
XS Rating Curve= 0 ,0
Exp/Cntr=0.3,0.1

Type RM Length L Ch R = 1 ,6.6198  ,4100.58,3448.62,3290.4
BEGIN DESCRIPTION:
Wigwam Point
END DESCRIPTION:
XS GIS Cut Line= 4
     622817.1442     5439429.015     622926.7432    5439383.8938
     622971.1688      5439385.55     624611.4961    5440239.6075
#Sta/Elev= 30
       0   5.698    20.4   5.698   25.28   5.848   37.76   5.548   49.02   4.988
   54.05   4.588   61.57   3.698   65.61   3.418   94.83   1.698  110.61   1.458
  125.11    .978     163   -.302  241.14  -2.132  343.44  -2.132  433.91  -1.672
  557.33   -.762  710.43  -1.212 1116.18  -2.132 1217.71  -3.042 1451.86  -5.782
 1559.95  -6.232 1644.98  -3.932  1804.7   -.222 1846.26   -.302 1881.81    .258
 1912.08   1.698 1927.15   1.698    1976   3.698  1992.9   3.698 2012.33   4.848
#Mann= 3 , 0 , 0
       0      .1       0  125.11    .045       0 1912.08     .12       0
Bank Sta=125.11,1912.08
XS Rating Curve= 0 ,0
Exp/Cntr=0.3,0.1

Type RM Length L Ch R = 1 ,3.1711  ,1686.56,752.56,484.08
BEGIN DESCRIPTION:
Peterview
END DESCRIPTION:
XS GIS Cut Line= 3
     621541.6013    5442763.4222     621610.2179    5442776.2373
      623902.104    5443322.4026
#Sta/Elev= 30
       0   7.268   18.36   5.568   30.18   3.698   39.53   1.698   66.12   -.072
  113.56  -2.982  194.76  -4.802  362.16  -6.252  416.28  -7.162   526.4  -5.792
  671.96  -4.872  873.04  -5.332  980.33  -6.252  1107.5 -10.362 1237.65 -14.932
 1316.85  -9.452 1386.46  -5.332  1450.9  -3.962 1589.02  -5.332 1678.84  -7.162
 1874.72  -7.162 1992.07  -6.242 2141.14  -5.322 2278.77  -3.032 2326.97   -.282
 2353.18   1.698 2360.87   2.808 2366.08   3.698 2391.89   5.698 2425.85   9.108
#Mann= 3 , 0 , 0
       0      .1       0   66.12    .045       0 2353.18     .12       0
Bank Sta=66.12,2353.18
XS Rating Curve= 0 ,0
Exp/Cntr=0.3,0.1

Type RM Length L Ch R = 1 ,2.4185  ,2000.72,1452.32,1476
BEGIN DESCRIPTION:
Peters Arm
END DESCRIPTION:
XS GIS Cut Line= 3
     620293.4317    5443741.0135     620423.0615    5443729.0557
     623935.6074    5443787.8188
#Sta/Elev= 30
       0  10.608   37.79   7.698   47.26   5.698   78.44   2.688  172.36  -3.042
  241.13  -9.442  346.74 -12.642  484.88 -13.102  932.59 -20.412 1248.43 -13.102
 1335.68  -9.902 1453.13  -7.612 1599.28  -6.702 1770.81  -6.702 2235.89 -18.582
 2350.21 -20.412 2451.78 -18.592  2615.4 -13.102 2709.03  -5.792 2785.96  -3.502
  2848.7  -5.332 2892.29 -10.812 2940.83 -14.9223087.569 -11.2723371.329  -8.052
 3436.62  -3.9223521.129  -2.102 3559.18    .1583582.241   5.228 3643.28  10.568
#Mann= 3 , 0 , 0
       0      .1       0   78.44    .045       0 3559.18     .12       0
#XS Ineff= 1 ,-1
       0 1043.37  10.607
Permanent Ineff=
       F
Bank Sta=78.44,3559.18
XS Rating Curve= 0 ,0
Exp/Cntr=0.3,0.1

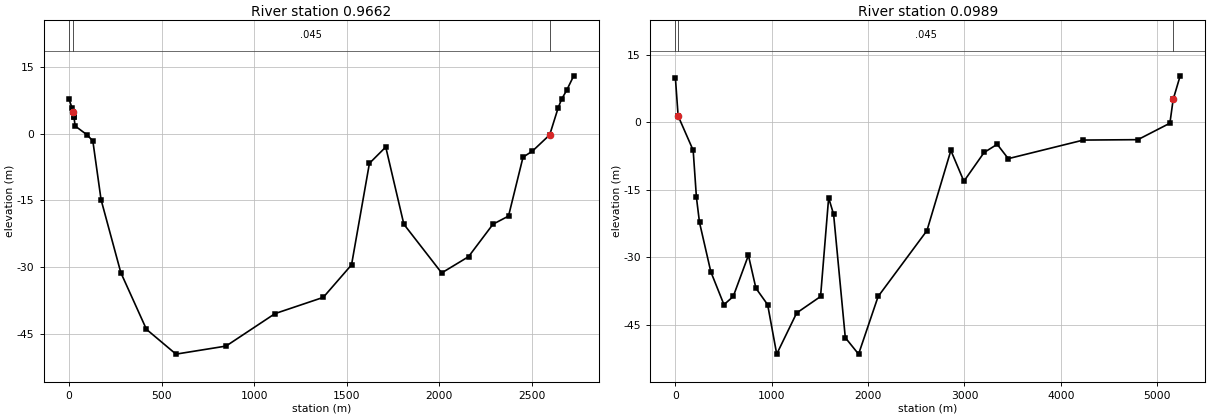
Type RM Length L Ch R = 1 ,0.9662  ,218.7,867.35,3368.7
BEGIN DESCRIPTION:
Botwood
END DESCRIPTION:
XS GIS Cut Line= 3
     621395.0795      5445201.46     621491.9061    5445181.5799
     624116.8066    5445253.2794
#Sta/Elev= 30
       0   7.779   17.43   5.699   21.51   4.739    26.1   3.699   27.44   3.699
   33.38   1.699   97.66   -.291  129.15  -1.661  173.51 -14.881   280.1 -31.291
  418.54 -44.061  577.92 -49.641  848.05 -47.831 1112.65 -40.521 1372.96 -36.871
 1525.54 -29.551 1622.15  -6.701 1710.17  -3.041 1807.93 -20.411 2012.06 -31.371
  2156.9 -27.721 2289.15 -20.401 2372.86 -18.581 2451.13  -5.331 2501.92  -3.961
 2595.18   -.301 2640.26   5.699 2659.15   7.699 2686.44   9.699 2724.76  12.979
#Mann= 3 , 0 , 0
       0      .1       0   21.51    .045       0 2595.18     .12       0
Bank Sta=21.51,2595.18
XS Rating Curve= 0 ,0
Exp/Cntr=0.3,0.1

Type RM Length L Ch R = 1 ,0.0989  ,99.07,98.93,174.17
BEGIN DESCRIPTION:
Mill Point
END DESCRIPTION:
XS GIS Cut Line= 4
     621321.3996    5445350.9679     621353.5718    5445369.5816
     625777.0176    5447903.8337     625825.8527    5447812.4137
#Sta/Elev= 30
       0   9.959   28.56   1.429  184.74  -6.211  218.54 -16.691   250.4 -22.231
  367.65 -33.191  504.33 -40.521  600.51 -38.691  757.96 -29.551  835.88 -36.861
  957.58 -40.521 1051.74 -51.501 1258.79 -42.361 1506.77 -38.701 1590.62 -16.761
 1641.97 -20.421 1763.47 -47.851 1901.34 -51.511 2104.07 -38.701 2610.64 -24.061
 2859.05  -6.241 2994.15 -13.0913203.881  -6.691 3339.87  -4.8713454.689  -8.061
4233.849  -3.931 4799.78  -3.841 5132.14   -.181 5166.14   5.109 5238.79  10.349
#Mann= 3 , 0 , 0
       0      .1       0   28.56    .045       0 5166.14     .12       0
Bank Sta=28.56,5166.14
XS Rating Curve= 0 ,0
Exp/Cntr=0.3,0.1

Storage Area=Power Canal     ,597586.238936,5420427.4297862
Storage Area Surface Line= 6
      597612.744     5420686.532
      597623.839     5420345.664
       597568.66     5420156.037
      597515.861     5420167.781
      597512.842     5420256.632
      597612.744     5420686.532
Storage Area Type= 1
Storage Area Vol Elev= 19
  28.566       0  29.706    .013  31.706     .14  33.706    .449  35.706   1.056
  37.706   2.121  39.706   3.858  41.706   9.498  43.706  28.171  45.706  56.916
  47.706   93.98  49.706 135.666  51.706 182.023  53.706 233.813  55.706 293.774
  57.706 360.483  59.706 430.815  61.706 505.199  63.706 585.183
Storage Area Is2D=0
Storage Area Point Generation Data=0,0,,
Storage Area 2D Points= 0
Storage Area Mannings=0.06
2D Cell Volume Filter Tolerance=0.003
2D Face Profile Filter Tolerance=0.003
2D Face Area Elevation Profile Filter Tolerance=0.003
2D Face Area Elevation Conveyance Ratio=0.02

Storage Area=Rushy Pond      ,594383.0576103,5423085.068073
Storage Area Surface Line= 6
594098.9557714025421905.39894033
595656.3854902385423783.78545933
594893.4553914845423999.51052174
593115.0390233545423126.08709834
593299.1945644335422347.37223892
594098.9557714025421905.39894033
Storage Area Type= 1
Storage Area Vol Elev= 10
   66.75       0      67664.0372      683320.186      695976.335      708632.484
      7111288.63      7213944.78      7316600.93      7419257.08      7521913.23
Storage Area Is2D=0
Storage Area Point Generation Data=0,0,,
Storage Area 2D Points= 0
Storage Area Mannings=0.06
2D Cell Volume Filter Tolerance=0.003
2D Face Profile Filter Tolerance=0.003
2D Face Area Elevation Profile Filter Tolerance=0.003
2D Face Area Elevation Conveyance Ratio=0.02
LCMann Table=0

Chan Stop Cuts=-1
CM Template=5w1_25d,False, 0 , 1
 CM Simple Trapezoid=1.25,5,0.25,
CM Template=80w1_25d,False, 0 , 1
 CM Simple Trapezoid=1.25,80,3,
CM Template=50w1_25d,False, 0 , 1
 CM Simple Trapezoid=1.25,50,3,
CM Template=60w1_25d,False, 0 , 1
 CM Simple Trapezoid=1.25,60,3,
Use User Specified Reach Order=0
Composite Channel Slope=5